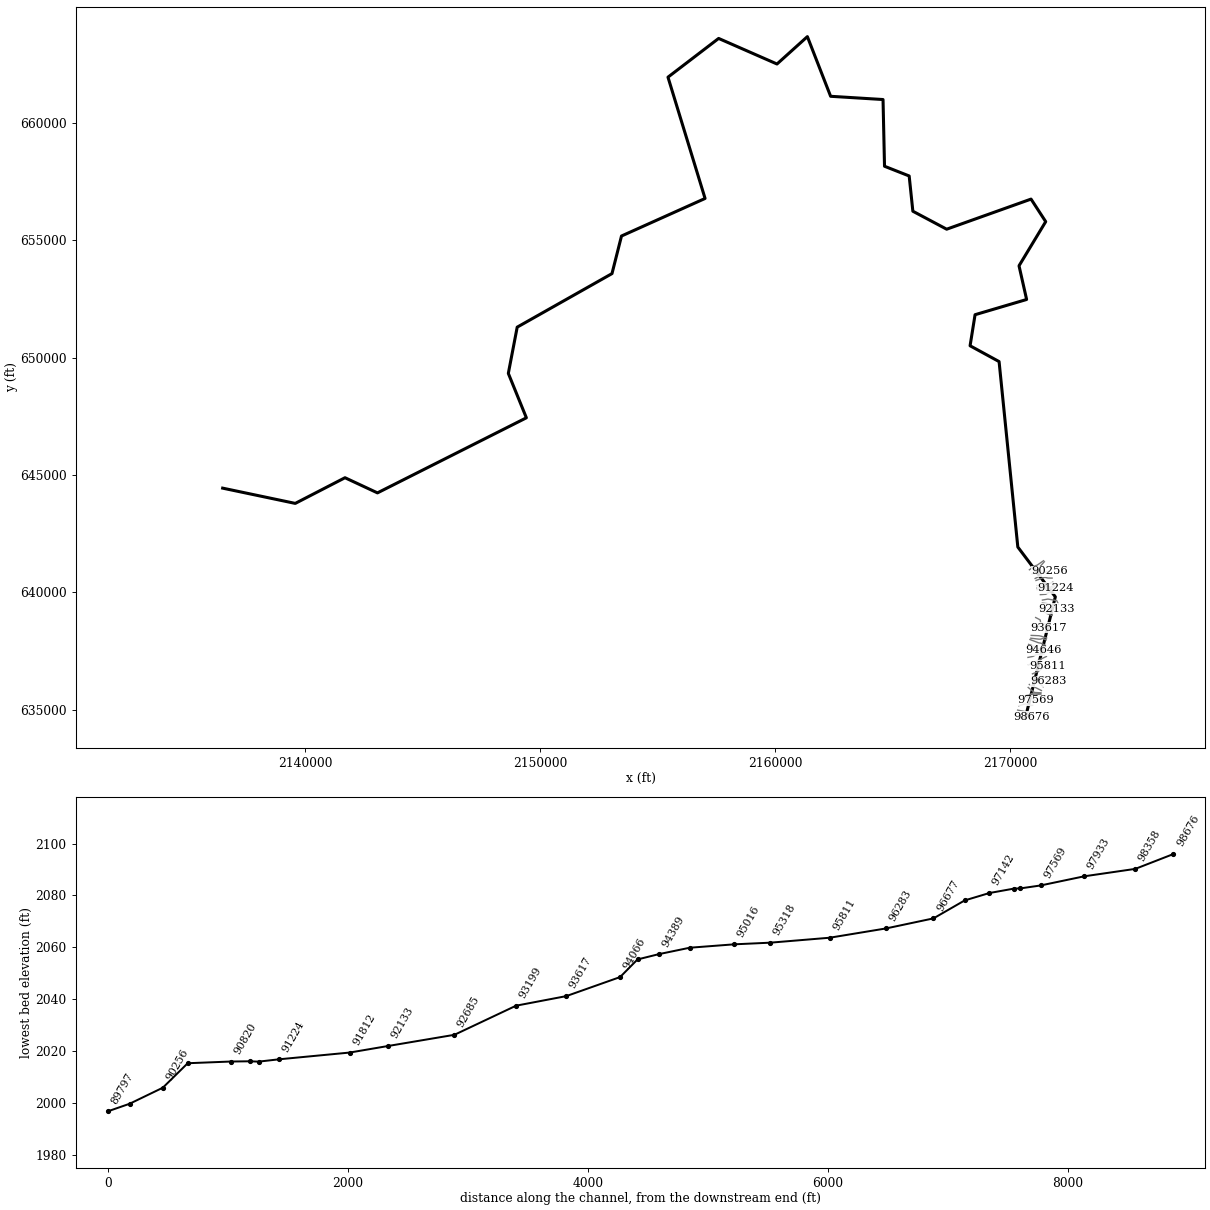
--- LIKANARV.prj (project) ---

Proj Title=LIKANARV
Current Plan=p01
Default Exp/Contr=0,0
English Units
Geom File=g01
Flow File=f01
Plan File=p01
BEGIN DESCRIPTION:
---------- MODELED AS PART OF WVEMD CTP PROGRAM, 2023----------
Stream Name: Little Kanawha River
Flood Zone:  AFH
Upshur County, WV
HEC-RAS Version: RAS 6.3
Vertical Datum: NAVD88
Projection: NAD 1983 StatePlane West Virginia S FIPS 4702 (US Feet)
Terrain: 1-meter LIDAR (FEMA Region III 3DEP collected 2016-2018)
Land Use: 2019 NLCD
Hydrologic Method:
WV SIR2010-5033 regression equations
Additional Model Notes:
None
END DESCRIPTION:
DSS Export Rating Curves= 0
DSS Export Rating Curve Sorted= 0
DSS Export Volume Flow Curves= 0
DXF OffsetX= 0
DXF OffsetY= 0
DXF ScaleX= 0
DXF ScaleY= 0

--- LIKANARV.p01 (plan) ---

Plan Title=Floodplain
Program Version=6.20
Short Identifier=Floodplain
Geom File=g01
Flow File=f01
Subcritical Flow
K Sum by GR= 0
Std Step Tol= 0.01
Critical Tol= 0.01
Num of Std Step Trials= 20
Max Error Tol= 0.3
Flow Tol Ratio= 0.001
Split Flow NTrial= 30
Split Flow Tol= 0.02
Split Flow Ratio= 0.02
Log Output Level= 0
Friction Slope Method= 1
Unsteady Friction Slope Method= 2
Unsteady Bridges Friction Slope Method= 1
Parabolic Critical Depth
Global Vel Dist= 0 , 0 , 0
Global Log Level= 0
CheckData=True
Encroach Param=-1 ,0,0, 0
Mapping Interval=1HOUR
Computation Time Step Use Courant=        0
Computation Time Step Use Time Series=    0
Computation Time Step Count To Double=0
Computation Time Step Max Doubling=0
Computation Time Step Max Halving=0
Computation Time Step Residence Courant=0
Run HTab= 0
Run UNet= 0
Run Sediment= 0
Run PostProcess= 0
Run WQNet= 0
Run RASMapper=-1
UNET Theta= 0
UNET Theta Warmup= 0
UNET ZTol= 0
UNET ZSATol= 0
UNET MxIter= 0
UNET Max Iter WO Improvement= 0
UNET MaxInSteps= 0
UNET DtIC= 0
UNET DtMin= 0
UNET MaxCRTS= 0
UNET WFStab= 0
UNET SFStab= 0
UNET WFX= 1
UNET SFX= 1
UNET Gravity=32.174
UNET 1D Methodology=Finite Difference
UNET DSS MLevel= 1
UNET Pardiso=0
UNET DZMax Abort= 0
UNET Use Existing IB Tables= 0
UNET Froude Reduction=False
UNET Froude Limit= 0
UNET Froude Power= 0
UNET D1 Cores= 0
UNET WindReference=Eulerian
UNET WindDragFormulation=Hsu (1988)
UNET D2 Coriolis=0
UNET D2 Cores= 0
UNET D2 Theta= 1
UNET D2 Theta Warmup= 1
UNET D2 Z Tol= 0.01
UNET D2 Volume Tol= 0.01
UNET D2 Max Iterations= 20
UNET D2 Equation= 0
UNET D2 RampUpFraction=0.1
UNET D2 TimeSlices= 1
UNET D2 Turbulence Formulation=Non-Conservative (original)
UNET D2 Eddy Viscosity=0.3
UNET D2 Transverse Eddy Viscosity=0.1
UNET D2 Smagorinsky Mixing=0
UNET D2 BCVolumeCheck=0
UNET D2 Cores=0
UNET D2 SolverType=PARDISO (Direct)
UNET D2 Minimum Iterations= 2147483647
UNET D2 Maximum Iterations= 2147483647
UNET D2 Restart Number= 10
UNET D2 Relaxation Coeff=1.3
UNET D2 SOR Precondition Iterations= 10
UNET D2 ILUT Maximum Fill= 8
UNET D2 ILUT Tolerance=1E-08
UNET D1D2 MaxIter= 0
UNET D1D2 ZTol=0.01
UNET D1D2 QTol=0.1
UNET D1D2 MinQTol=1
Write IC File= 0
Write IC File at Fixed DateTime=0
Write IC File at Sim End=0
Echo Input=False
Echo Parameters=False
Echo Output=False
Write Detailed= 0
HDF Write Warmup=0
HDF Write Time Slices=0
HDF Flush=0
HDF Compression= 1
HDF Chunk Size= 1
HDF Spatial Parts= 1
HDF Use Max Rows=0
HDF Fixed Rows= 1
Calibration Method= 0
Calibration Iterations= 20
Calibration Max Change=0.05
Calibration Tolerance=0.2
Calibration Maximum=1.5
Calibration Minimum=0.5
Calibration Optimization Method= 1
WQ AD Non Conservative
WQ ULTIMATE=-1
WQ Max Comp Step=1HOUR
WQ Output Interval=15MIN
WQ Output Selected Increments= 0
WQ Output face flow=0
WQ Output face velocity=0
WQ Output face area=0
WQ Output face dispersion=0
WQ Output cell volume=0
WQ Output cell surface area=0
WQ Output cell continuity=0
WQ Output cumulative cell continuity=0
WQ Output face conc=0
WQ Output face dconc_dx=0
WQ Output face courant=0
WQ Output face peclet=0
WQ Output face adv mass=0
WQ Output face disp mass=0
WQ Output cell mass=0
WQ Output cell source sink temp=0
WQ Output nsm pathways=0
WQ Output nsm derived pathways=0
WQ Create Restart=0
WQ Fixed Restart=0
WQ System Summary=0
WQ Write To DSS=0
Sorting and Armoring Iterations= 10
XS Update Threshold= 0.02
Bed Roughness Predictor= 0
Hydraulics Update Threshold= 0.02
Energy Slope Method= 1
Volume Change Method= 1
Sediment Retention Method= 0
Sediment TS Multiplier= 1
Warm Up Method= 0
XS Weighting Method= 0
Number of US Weighted Cross Sections= 1
Number of DS Weighted Cross Sections= 1
Upstream XS Weight=0
Main XS Weight=1
Downstream XS Weight=0
Number of DS XS's Weighted with US Boundary= 1
Upstream Boundary Weight= 1
Weight of XSs Associated with US Boundary= 0
Number of US XS's Weighted with DS Boundary= 1
Downstream Boundary Weight= 0.5
Weight of XSs Associated with DS Boundary= 0.5
Percentile Method= 0
Sediment Output Level= 3
Mass or Volume Output= 0
Output Increment Type= 1
Profile and TS Output Increment= 1
Transport Output Increment 1
XS Output Flag= 0
XS Output Increment= 10
Read HDF5 Sediment Hotstart= 0
Sediment Hotstart Type= 0
Write Gradation File= 0
Read Gradation Hotstart= 0
Write HDF5 File= 1
Write Binary Output= 1
Write DSS Sediment File= 0
DSS Sediment Output Type= 1
SV Curve= 0
Specific Gage Flag= 0
Subcell Erosion Methods= 0
Subcell Deposition Methods= 0
Advection Scheme= 1
Matrix Solver= 0
Implicit Weighting Factor= 1
Maximum Outer Loop Convergence Iterations= 5
Convergence Maximum Absolute= 0.001
Convergence RMSE= 0.0001
Grain Fractions Max Abs Error= 0.001
Max Subgrid Regions= 1
Max Subgrid Length Scale= 3.402823E+38
Initial Layer Thickness= 3.402823E+38
Min Layer Thickness= 3.402823E+38
Max Layer Thickness= 3.402823E+38
Number of Layers= 5

--- LIKANARV.f01 (steady flow) ---

Flow Title=Flows
Program Version=6.31
Number of Profiles= 1
Profile Names=01pct
River Rch & RM=LIKANARV,Main            ,98676
     624
River Rch & RM=LIKANARV,Main            ,95811
     925
River Rch & RM=LIKANARV,Main            ,91812
    1120
River Rch & RM=LIKANARV,Main            ,87652
    1270
River Rch & RM=LIKANARV,Main            ,81064
    1770
River Rch & RM=LIKANARV,Main            ,79916
    1970
River Rch & RM=LIKANARV,Main            ,67196
    2530
River Rch & RM=LIKANARV,Main            ,66102
    2990
River Rch & RM=LIKANARV,Main            ,58518
    3330
River Rch & RM=LIKANARV,Main            ,46813
    4320
River Rch & RM=LIKANARV,Main            ,39362
    4840
River Rch & RM=LIKANARV,Main            ,34443
    5990
River Rch & RM=LIKANARV,Main            ,16765
    6790
Boundary for River Rch & Prof#=LIKANARV,Main            , 1
Up Type= 0
Dn Type= 3
Dn Slope=0.00689
DSS Import GetInterval= 0
DSS Import GetPeak= 0
DSS Import FillOption= 0

--- LIKANARV.g01 (geometry) ---

Geom Title=Geometry
Program Version=6.31

River Reach=LIKANARV        ,Main
Reach XY= 30
2170664.61471695634673.175310725     2171937.704      639815.152
     2170340.738      641935.026     2169542.627      649832.262
     2168308.002      650505.262     2168519.992      651828.054
     2170715.355      652476.359     2170391.761      653910.898
     2171528.175      655791.109     2170903.823      656751.246
     2167310.721      655469.118     2165870.944       656234.95
     2165714.041      657735.851      2164664.22      658149.758
     2164601.092      660990.907     2162369.414      661128.609
     2161379.488      663669.373     2160085.741       662503.57
     2157600.264      663592.5662155443.59838868661942.983639038
2157023.30289177656778.235385569     2153464.252      655179.177
     2153059.502      653578.404     2149023.017      651298.165
2148645.02640332 649329.41432383     2149413.946      647438.043
     2143072.726       644241.02     2141690.268       644886.52
     2139572.255      643793.2592136480.72453524644443.055498973

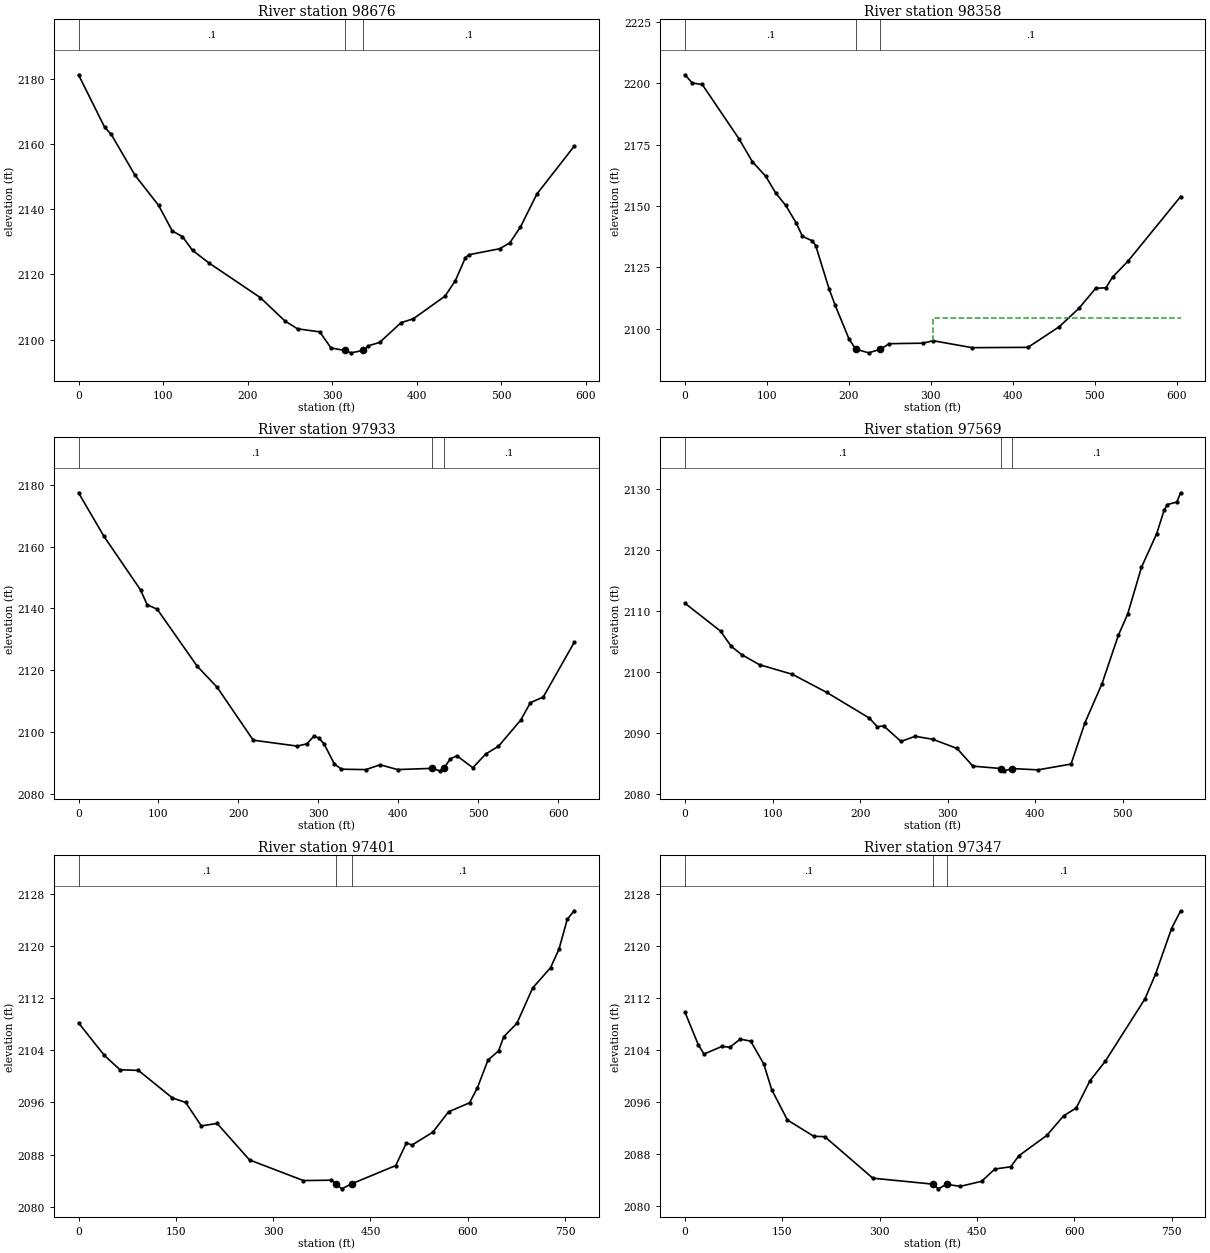
Type RM Length L Ch R = 1 ,98676   ,318.2,318,297
XS GIS Cut Line= 4
2170337.41340997634664.3981757012170598.96743077634653.659532787
2170732.72448205634717.3987837532170907.99604219 634699.14940716
#Sta/Elev= 30
       0 2181.24    30.8  2165.2    38.8 2162.93    66.8 2150.44    94.8 2141.16
   110.9 2133.34   122.9 2131.62   134.9 2127.37   154.9 2123.42   214.9 2112.93
   244.2 2105.72     259 2103.34   285.3  2102.4   298.6 2097.47  314.892096.706
   322.3 2095.97  336.632096.705   342.9 2098.13   356.2 2099.18   381.5 2105.22
     396 2106.42   433.5 2113.36   445.6 2118.08   457.6 2125.16   461.7 2126.06
   497.9 2127.88   509.9 2129.64   522.6 2134.52   542.1 2144.67   586.2 2159.33
#Mann= 3 ,-1,0
       0      .1       0  314.89    .045       0  336.63      .1       0
Bank Sta=314.89,336.63
XS Rating Curve= 0 ,0
Exp/Cntr=0.3,0.1

Type RM Length L Ch R = 1 ,98358   ,422,425.2,409.2
XS GIS Cut Line= 3
2170331.44643964634991.708785219 2170595.4001757634940.034112629
2170920.33624168634854.564836263
#Sta/Elev= 30
       0 2203.43     8.9 2200.07    21.1 2199.48      66 2177.32    82.3 2168.04
    98.6  2162.1   110.8 2155.27     123 2150.24   135.7 2143.16   143.4 2137.67
   155.6 2135.79   159.6 2133.86     176 2116.17   183.4 2109.56   200.4 2095.74
  208.582091.748   224.3 2090.25  238.65 2091.75   249.4 2093.98   290.4 2094.18
   302.9 2095.18   350.5 2092.35   418.7 2092.49   456.9  2100.9   480.7 2108.32
   501.4 2116.54   513.8 2116.72   522.1 2121.16   540.5 2127.47     605 2153.87
#Mann= 3 ,-1,0
       0      .1       0  208.58    .045       0  238.65      .1       0
#XS Ineff= 2 , 0
                          302.44         2104.44
Permanent Ineff=
       F       F
Bank Sta=208.58,238.65
XS Rating Curve= 0 ,0
Exp/Cntr=0.3,0.1

Type RM Length L Ch R = 1 ,97933   ,361.2,363.7,358.9
XS GIS Cut Line= 4
2170377.62718835635177.3544240982170666.03007923 635260.16609982
2170817.74132022635191.4121655982170970.82160845635195.754341183
#Sta/Elev= 30
       0 2177.44    31.8 2163.34    77.6 2145.97    85.9 2141.16    98.4 2139.74
   148.3 2121.31   173.3 2114.47   218.5 2097.31   273.5 2095.41   285.6 2096.14
     294 2098.53   300.1 2098.12     307 2096.13     320 2089.59   328.8 2087.92
   359.5 2087.79   377.1 2089.36     399  2087.8   442.22088.193   451.7 2087.39
  456.74  2088.2   464.9 2091.26   473.1 2092.26   493.1  2088.4   509.1 2092.82
   525.1 2095.33   553.1 2103.87   565.1 2109.48   581.1 2111.28   619.8 2128.97
#Mann= 3 ,-1,0
       0      .1       0   442.2    .045       0  456.74      .1       0
Bank Sta=442.2,456.74
XS Rating Curve= 0 ,0
Exp/Cntr=0.3,0.1

Type RM Length L Ch R = 1 ,97569   ,160.6,168.4,177.5
XS GIS Cut Line= 3
2170563.93833672    635517.337932170851.93680036635557.653866979
2171077.77559656635400.632742021
#Sta/Elev= 30
       0 2111.27    40.6 2106.71    52.7 2104.24    64.9 2102.85    85.1 2101.22
   122.6 2099.65   161.8 2096.69   210.3 2092.51   219.7 2091.06   226.8 2091.22
   246.6 2088.67   262.8 2089.51     283 2089.02   310.6 2087.52   328.7 2084.63
  361.162084.232   364.2 2083.86   373.9 2084.23   403.1 2084.02   440.8 2084.97
   456.7 2091.74   476.2 2098.14   494.8 2106.03   505.5 2109.53   521.2 2117.16
   538.5 2122.62   547.1 2126.52   550.9 2127.42   561.5 2127.82   565.9 2129.34
#Mann= 3 ,-1,0
       0      .1       0  361.16    .045       0   373.9      .1       0
Bank Sta=361.16,373.9
XS Rating Curve= 0 ,0
Exp/Cntr=0.3,0.1

Type RM Length L Ch R = 1 ,97401   ,53.6,53.6,53.9
XS GIS Cut Line= 6
2170584.96371679635537.1928304452170825.73260881  635573.6729656
 2170918.1489512635633.257186352  2170987.461208 635656.36127195
  2171072.442801635675.9793919682171319.25414775635636.162468556
#Sta/Elev= 30
       0 2108.24    39.7 2103.25    63.9 2101.03    92.3 2100.93   144.8 2096.69
   165.1 2096.01   189.3  2092.4   213.6 2092.78   263.6 2087.17   346.7    2084
   389.9 2084.06   396.82083.505   405.7 2082.73   421.5 2083.52   488.9 2086.31
   505.4  2089.8   513.8 2089.45     546 2091.43   570.3 2094.57   602.7 2095.95
   614.9  2098.3   631.1 2102.52   647.3 2103.92   655.4 2106.11   675.6 2108.16
     700 2113.61   727.5 2116.71   740.5 2119.56   753.3 2124.16   763.9 2125.46
#Mann= 3 ,-1,0
       0      .1       0   396.8    .045       0   421.5      .1       0
Bank Sta=396.8,421.5
XS Rating Curve= 0 ,0
Exp/Cntr=0.3,0.1

Type RM Length L Ch R = 1 ,97347   ,211,205.4,192.6
XS GIS Cut Line= 6
 2170580.0115537635591.9940571452170820.78044572  635628.4741923
2170913.19678811635688.058413052 2170982.5090449635711.162498649
 2171067.4906379635730.7806186682171314.30198465635690.963695256
#Sta/Elev= 30
       0 2109.85    20.4 2104.87    29.3 2103.41    57.4  2104.6    68.9 2104.44
    85.1  2105.7   101.3  2105.4   121.5 2101.86   133.7 2097.92   157.9 2093.25
   198.4 2090.75   215.5 2090.68   289.5 2084.29   382.4 2083.37   390.4 2082.65
   403.1 2083.35   424.2 2083.03   457.1 2083.81   477.6  2085.7   502.2 2086.05
   514.5 2087.74   557.7 2090.88   583.4 2093.88   603.1 2095.11   623.9 2099.25
     648 2102.33     709 2111.92   725.2 2115.71   749.9 2122.74   763.9 2125.47
#Mann= 3 ,-1,0
       0      .1       0   382.4    .045       0   403.1      .1       0
Bank Sta=382.4,403.1
XS Rating Curve= 0 ,0
Exp/Cntr=0.3,0.1

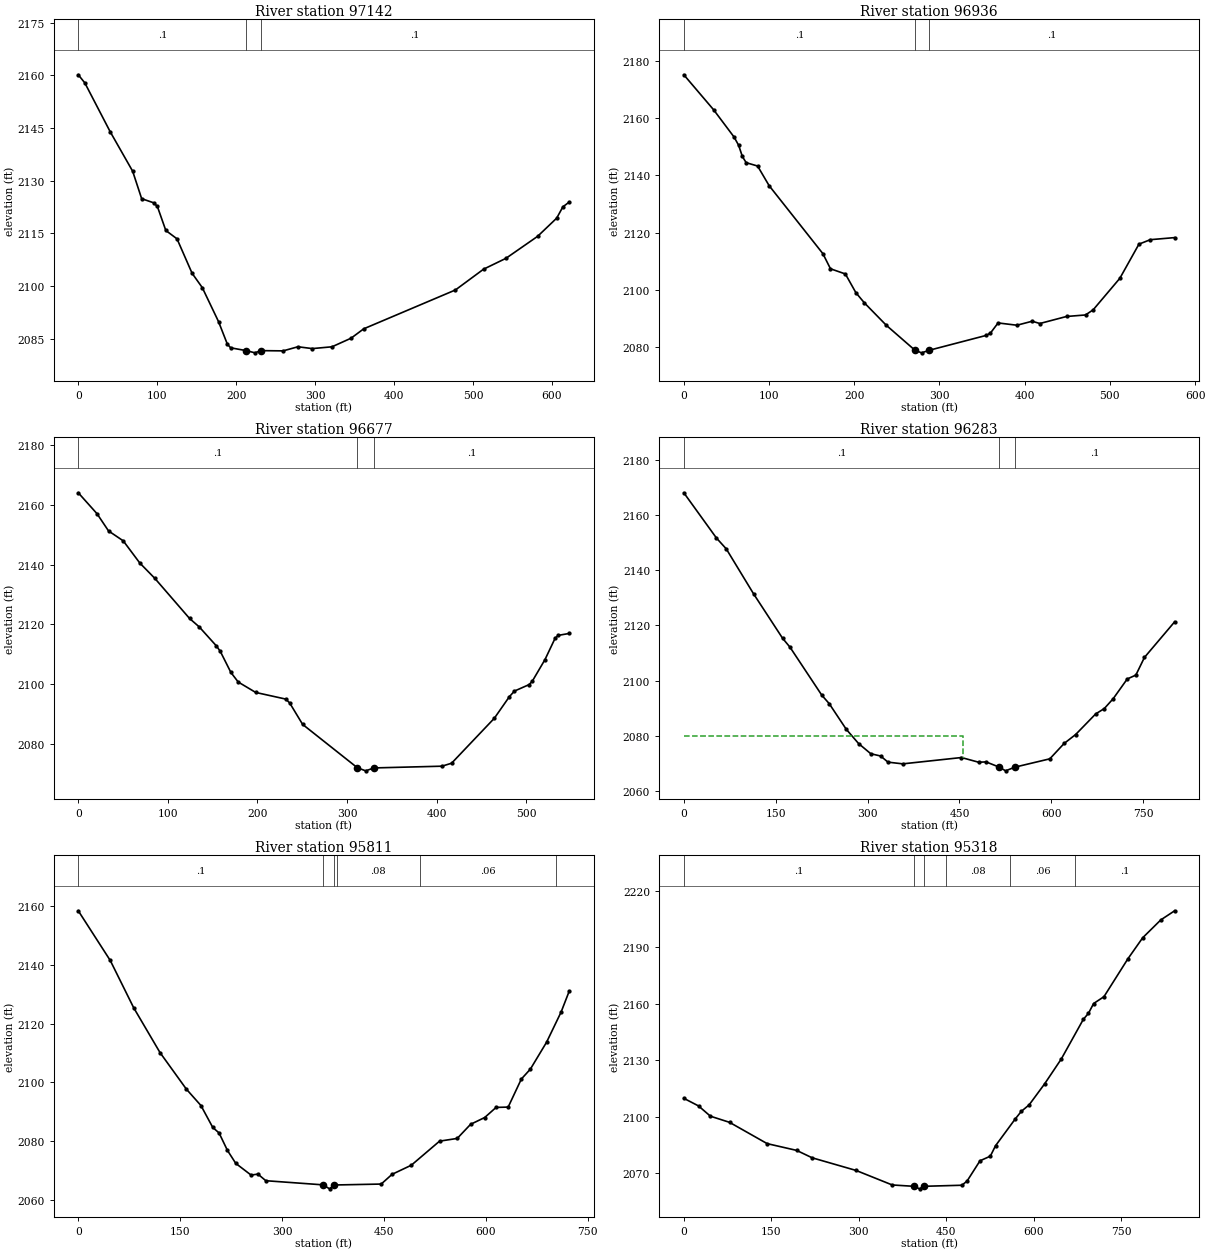
Type RM Length L Ch R = 1 ,97142   ,200.8,205.3,205.2
XS GIS Cut Line= 3
2170781.70749557635955.5555810222171047.06148205635742.205891877
2171327.99881529635728.259279319
#Sta/Elev= 30
       0 2160.14     8.3 2157.83    40.4 2143.93    68.9 2132.67    80.3 2124.85
    95.6 2123.67   100.2 2122.64   110.9 2115.79   125.1 2113.41   144.2  2103.6
   157.1 2099.52   177.7 2089.83   188.9 2083.39   193.1 2082.37  212.982081.562
   223.9 2080.94   231.1 2081.57   259.5  2081.5   278.3 2082.67   296.5 2082.15
   321.4 2082.66   345.6 2085.11   361.6 2087.78   477.8 2098.85   513.4 2104.76
   541.8 2107.86   581.9 2114.12   606.1 2119.31   613.9 2122.52   621.8 2123.86
#Mann= 3 ,-1,0
       0      .1       0  212.98    .045       0   231.1      .1       0
Bank Sta=212.98,231.1
XS Rating Curve= 0 ,0
Exp/Cntr=0.3,0.1

Type RM Length L Ch R = 1 ,96936   ,261.8,259.7,257.2
XS GIS Cut Line= 2
2170830.72567442636082.7509740382171345.64088156635824.597691183
#Sta/Elev= 30
       0 2175.07      35 2162.85    58.9 2153.38    64.3 2150.51    68.7 2146.57
    73.2 2144.41    86.6 2143.24   100.1  2136.4   163.2 2112.68   172.1 2107.41
   189.6  2105.6   201.9 2099.08   211.9 2095.52   237.7 2087.68   271.2 2079.01
     279 2078.09  288.282079.009   355.1 2084.19   359.9 2085.01   368.8 2088.52
   390.9 2087.72   408.8 2089.11   417.8 2088.32   449.1 2090.77   471.4  2091.3
   480.4  2093.1   511.7 2104.09   534.1    2116   547.5 2117.56     576 2118.28
#Mann= 3 ,-1,0
       0      .1       0   271.2    .045       0  288.28      .1       0
Bank Sta=271.2,288.28
XS Rating Curve= 0 ,0
Exp/Cntr=0.3,0.1

Type RM Length L Ch R = 1 ,96677   ,385.8,393.3,401.1
XS GIS Cut Line= 3
2170964.72093046 636270.825875142171215.42803214636171.744026572
2171421.09792992635984.089010346
#Sta/Elev= 30
       0 2163.93    20.9 2156.96    33.8  2151.2    50.2  2147.9    68.7  2140.5
    85.4 2135.41   124.2 2122.02   135.1 2119.18   154.3 2112.82   158.6 2111.01
   170.4    2104   178.6  2100.8   198.1 2097.33   231.7 2095.11     236 2093.84
   250.5 2086.67   311.6 2072.21   320.9 2071.18   330.1 2072.15     406 2072.73
   416.8 2073.72   464.5 2088.71   481.4 2095.95     487 2097.79   503.4 2099.95
   506.9 2101.07   521.1  2108.3   532.4 2115.42   535.9 2116.37     548    2117
#Mann= 3 ,-1,0
       0      .1       0   311.6    .045       0   330.1      .1       0
Bank Sta=311.6,330.1
XS Rating Curve= 0 ,0
Exp/Cntr(USF)=0,0
Exp/Cntr=0.3,0.1

Type RM Length L Ch R = 1 ,96283   ,465.3,472.3,481.3
XS GIS Cut Line= 4
2170962.88688837636402.1508155032171417.72349364636400.801944186
 2171555.7314432636392.9919586892171663.90948093636215.040879997
#Sta/Elev= 30
       0 2168.04    53.3 2151.64    69.3 2147.72   113.9 2131.43   161.3 2115.32
   173.3 2112.12   225.3 2094.71   237.3 2091.68   265.1  2082.4   285.3 2077.21
   305.2 2073.52   321.3 2072.69   333.3 2070.47   357.4 2069.85   453.3 2072.14
   481.3 2070.44   493.4 2070.56  515.032068.657   525.4 2067.32   540.2 2068.64
   597.5 2071.67   620.9 2077.24   639.7 2080.48   672.4 2087.94   686.4 2089.87
     701 2093.46   723.9 2100.59     738 2102.01     752  2108.4   801.3  2121.3
#Mann= 3 ,-1,0
       0      .1       0  515.03    .045       0   540.2      .1       0
#XS Ineff= 2 , 0
          456.51 2079.88
Permanent Ineff=
       F       F
Bank Sta=515.03,540.2
XS Rating Curve= 0 ,0
Exp/Cntr=0.3,0.1

Type RM Length L Ch R = 1 ,95811   ,487.1,493.3,484.3
XS GIS Cut Line= 4
2170964.38286117 636535.675574612171196.97315606636628.391718074
2171381.44508289636769.8579196272171594.67113467636879.451693351
#Sta/Elev= 30
       0 2158.48    47.1 2141.54    81.6 2125.42   120.3 2110.17   159.1 2097.71
   180.6 2092.11     198 2084.64   207.3 2082.76   219.6 2076.82   231.9 2072.39
   254.4 2068.41   264.5 2068.74   276.1 2066.49   360.3 2065.08     370 2063.72
   376.6 2065.03     446 2065.35     462 2068.67   490.3 2071.77   531.9 2079.97
   557.9  2080.9   577.6 2085.71   598.4 2088.03   615.1 2091.47   632.9 2091.58
   652.3 2101.14   665.6 2104.52   689.4 2113.67   710.8 2123.95   722.6 2130.98
#Mann= 6 ,-1,0
       0      .1       0   360.3    .045       0   376.6      .1       0
  380.39     .08       0  502.86     .06       0  702.86      .1       0
Bank Sta=360.3,376.6
XS Rating Curve= 0 ,0
Exp/Cntr=0.3,0.1

Type RM Length L Ch R = 1 ,95318   ,294.3,301.7,297.7
XS GIS Cut Line= 2
2170797.38429428636913.6116467722171557.64229428637274.386646772
#Sta/Elev= 30
       0  2109.9    25.2 2105.86    45.6  2100.4    78.4 2097.14   142.9 2085.83
   193.5 2082.23     220 2078.31   295.3 2071.59   357.3 2063.88   395.1 2063.15
   404.1 2061.82  411.792063.172   476.8 2063.73   485.7 2065.99   507.8 2076.72
   525.5 2079.17   534.4  2084.7   568.1  2098.9   578.7 2102.99     592  2106.4
   618.5 2117.54   647.2 2130.81   684.9 2151.82   693.8 2155.07   702.6 2160.25
   720.3 2163.87   761.4 2184.02   786.8  2195.2   817.8 2204.66   841.5  2209.5
#Mann= 6 ,-1,0
       0      .1       0   395.1    .045       0  411.79      .1       0
     450     .08       0     560     .06       0     670      .1       0
Bank Sta=395.1,411.79
XS Rating Curve= 0 ,0
Exp/Cntr=0.3,0.1

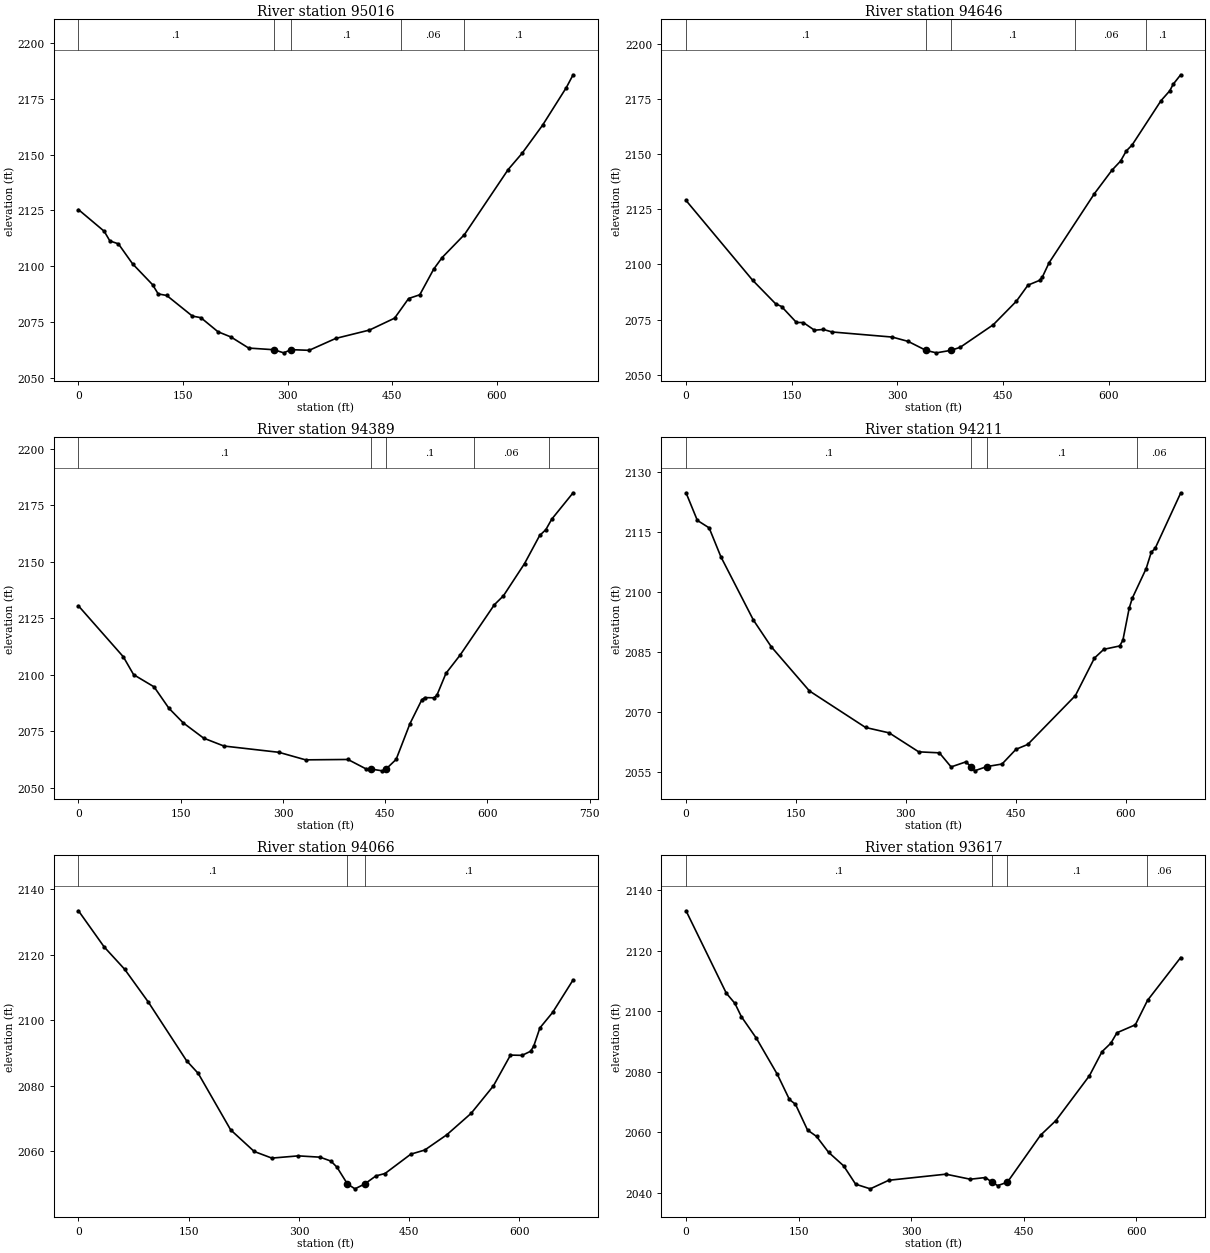
Type RM Length L Ch R = 1 ,95016   ,380.9,370.1,347.4
XS GIS Cut Line= 4
2170772.00800933637235.4857376922170981.32271854637276.803790946
 2171130.1088217637358.4798740832171455.66024238637375.461829323
#Sta/Elev= 30
       0 2125.36    36.9 2115.66      45 2111.34    57.3 2110.01    77.6 2101.06
   106.2 2091.73   114.3 2087.59   126.6 2086.88   163.3 2077.65   175.5 2076.93
     200 2070.63   218.7 2068.27     244 2063.32   280.3 2062.57   294.2 2061.18
   304.92062.608   330.7 2062.31   368.9 2067.65   417.2 2071.39   453.2 2076.72
   473.3 2085.52   489.3  2087.2   509.3 2098.71   521.3 2103.87   553.4  2114.2
     616 2143.32     636 2150.61   665.3 2163.17   699.4 2180.06   709.1 2185.78
#Mann= 5 ,-1,0
       0      .1       0   280.3    .045       0   304.9      .1       0
  463.08     .06       0  553.08      .1       0
Bank Sta=280.3,304.9
XS Rating Curve= 0 ,0
Exp/Cntr=0.3,0.1

Type RM Length L Ch R = 1 ,94646   ,247.6,257.1,260.1
XS GIS Cut Line= 4
 2170800.5108905 637790.076253552171083.65742118637689.375604565
2171174.88036202637608.8150853762171447.36447104 637546.02526895
#Sta/Elev= 30
       0 2129.07    94.4 2092.87     127 2082.18   135.5 2080.91   156.7 2073.65
   166.4 2073.63   182.2 2070.15   194.9 2070.49   207.1 2069.35   292.6 2067.03
   315.2 2065.06   340.7 2060.94   355.2 2059.87   375.9 2061.01   388.9 2062.37
   435.9 2072.63   468.7 2083.32   485.1 2090.61   501.5 2092.77   505.6 2094.33
   515.1 2100.79   579.5 2132.22   604.2 2142.78   616.5 2146.96   624.7  2151.6
   632.9 2154.26   673.9  2174.4   686.3 2178.87   691.1 2181.83   701.8 2186.15
#Mann= 5 ,-1,0
       0      .1       0   340.7    .045       0   375.9      .1       0
  552.22     .06       0  652.22      .1       0
Bank Sta=340.7,375.9
XS Rating Curve= 0 ,0
Exp/Cntr(USF)=0,0
Exp/Cntr=0.3,0.1

Type RM Length L Ch R = 1 ,94389   ,175.2,178,178.5
XS GIS Cut Line= 4
2170856.45626605637996.4264286532171223.88896189637857.580715095
2171319.82598047637842.0203105162171532.37320688637740.384482982
#Sta/Elev= 30
       0 2130.39    65.8 2107.86    80.9 2099.95   110.9 2094.56   132.6 2085.12
   153.6 2078.65   183.6 2071.87   213.3 2068.38     294  2065.6   333.2 2062.26
   395.3 2062.43   421.4 2058.33   429.6 2058.16   445.8  2057.4   451.22058.203
     466 2062.46   486.3 2078.29   503.7 2088.85   508.1  2089.8   521.4 2089.71
   525.8 2090.84   539.1 2100.54   559.9 2108.63   610.1 2130.89   623.4 2134.84
   654.4 2149.11   676.6 2161.55   685.5 2164.06   694.3 2168.76   725.6 2180.42
#Mann= 5 ,-1,0
       0      .1       0   429.6    .045       0   451.2      .1       0
  579.98     .06       0  689.98      .1       0
Bank Sta=429.6,451.2
XS Rating Curve= 0 ,0
Exp/Cntr=0.3,0.1

Type RM Length L Ch R = 1 ,94211   ,146.6,145,140.3
XS GIS Cut Line= 5
2170892.91854486638053.0826544312171240.03960548638011.617681319
2171309.93770301638012.8023948372171401.16064386638041.235519256
2171549.24983354637980.815129865
#Sta/Elev= 30
       0 2124.88    15.4 2117.98    31.5 2116.11    47.6 2108.86    91.9 2093.06
   116.1 2086.43   168.4 2075.33     245  2066.2   277.2 2064.85   317.5 2060.11
   345.7 2059.86   361.7 2056.34   381.7 2057.59   388.8 2056.43   393.7 2055.36
  410.53 2056.43   431.2 2057.06   450.3 2060.75   466.3 2061.96   531.3 2074.17
   557.3 2083.55   570.1 2085.74   591.7 2086.58   596.1 2087.99   604.7    2096
     609 2098.54   627.9 2105.93   634.9 2110.04   640.1 2110.96     675 2124.82
#Mann= 4 ,-1,0
       0      .1       0   388.8    .045       0  410.53      .1       0
  615.05     .06       0
Bank Sta=388.8,410.53
XS Rating Curve= 0 ,0
Exp/Cntr(USF)=0,0
Exp/Cntr=0.3,0.1

Type RM Length L Ch R = 1 ,94066   ,437.1,448.9,441.7
XS GIS Cut Line= 4
2170909.30399014638172.7632559962171236.11164171638159.073483846
2171339.43762065 638137.234935812171566.94091609638059.808024556
#Sta/Elev= 30
       0 2133.33    34.9 2122.33    62.9 2115.49      95 2105.52     147 2087.65
     163 2083.74   207.1 2066.54   239.1 2059.96   263.1 2057.94   299.1 2058.62
   328.7 2058.22   343.5 2057.03   351.7 2055.18   365.9 2050.07   376.2 2048.57
   389.5 2050.06   404.8 2052.52   417.1 2053.24   452.2 2059.14   471.2  2060.4
   501.1 2065.04   534.2 2071.57   564.5 2079.93   587.8 2089.34   603.6 2089.26
   615.2 2090.51   619.4 2092.05   627.8 2097.62   645.2 2102.36     673 2112.26
#Mann= 3 ,-1,0
       0      .1       0   365.9    .045       0   389.5      .1       0
Bank Sta=365.9,389.5
XS Rating Curve= 0 ,0
Exp/Cntr=0.3,0.1

Type RM Length L Ch R = 1 ,93617   ,418.4,417.8,374.8
XS GIS Cut Line= 3
2170986.68059707638572.6260558752171339.41658382638551.116426045
2171639.57296049638494.096248304
#Sta/Elev= 30
       0 2133.18    53.6 2105.94    65.1 2102.56    73.6 2098.21    93.7 2091.02
   121.7 2079.04   137.7 2070.78   145.8 2069.17   161.8 2060.68   173.8 2058.56
   189.8 2053.32   209.9 2048.83   225.9 2042.76   245.4 2041.22     270 2044.05
   346.1 2046.07   378.6  2044.4   398.9 2044.96  407.772043.344   415.2 2042.29
   428.1 2043.43   472.2 2058.95   492.6 2063.78   537.4 2078.65   554.1 2086.58
   565.9  2089.4     574 2092.84   598.5 2095.47   614.7 2103.54   658.9 2117.72
#Mann= 4 ,-1,0
       0      .1       0  407.77    .045       0   428.1      .1       0
  613.39     .06       0
Bank Sta=407.77,428.1
XS Rating Curve= 0 ,0
Exp/Cntr=0.3,0.1

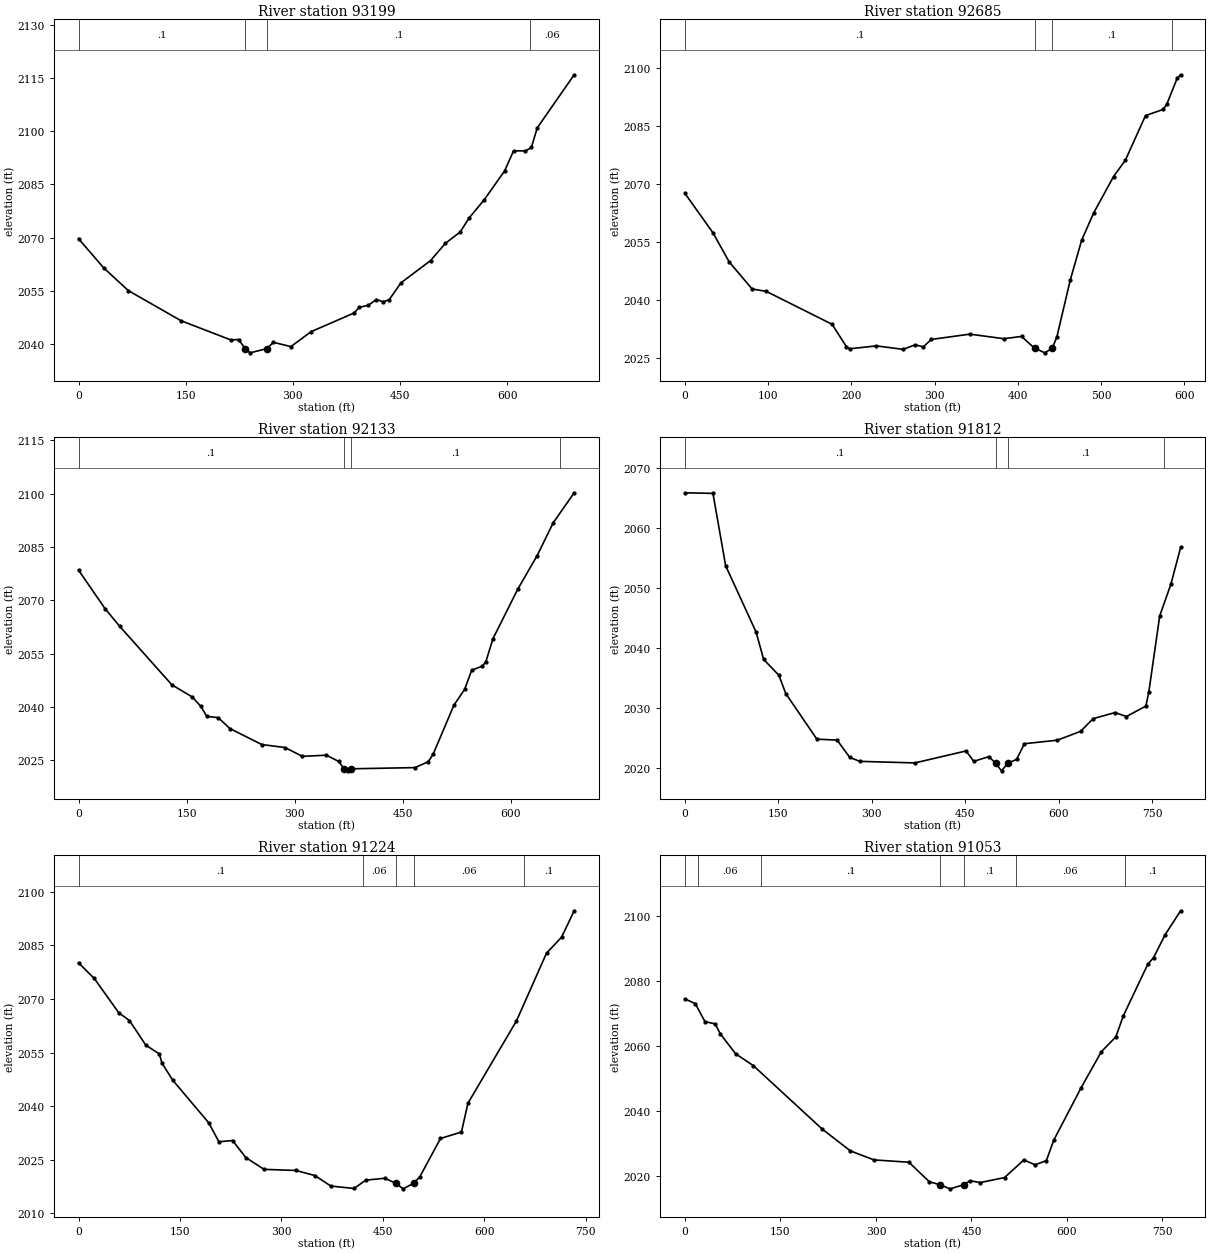
Type RM Length L Ch R = 1 ,93199   ,489.8,513.8,512.5
XS GIS Cut Line= 4
2171100.84700336 638933.384359212171291.69428135638833.947613846
2171314.88823554638709.1268713072171653.90525438638615.420057872
#Sta/Elev= 30
       0 2069.71    35.3 2061.47    69.7 2055.09   143.6 2046.58   213.2 2041.18
   224.1 2041.29   233.4 2038.73   240.3 2037.54  263.522038.726   272.9  2040.5
   297.3  2039.3   325.8 2043.52   385.4 2048.73   393.3 2050.38   405.7 2050.94
     417 2052.57   426.5 2051.93   434.8 2052.47   451.4 2057.26   492.9 2063.55
   513.6  2068.4   534.4 2071.61   546.8 2075.55   567.6 2080.57   596.6 2088.83
   609.1 2094.48   625.7 2094.44     634 2095.41   642.2 2100.94   693.9  2115.9
#Mann= 4 ,-1,0
       0      .1       0   233.4    .045       0  263.52      .1       0
  632.16     .06       0
Bank Sta=233.4,263.52
XS Rating Curve= 0 ,0
Exp/Cntr=0.3,0.1

Type RM Length L Ch R = 1 ,92685   ,543.8,552.5,542.6
XS GIS Cut Line= 3
2171280.50453475639305.5624302972171564.41549889639109.550756499
2171799.84178623639023.756793699
#Sta/Elev= 30
       0 2067.54    33.6 2057.38    53.1 2049.84    80.6 2042.85    97.8  2042.2
   176.7 2033.71     194 2027.92   197.8 2027.37   230.1 2028.12   262.1 2027.22
   276.7 2028.39   286.4 2027.88   296.1 2029.79   342.2 2031.15   383.1 2029.98
   404.4 2030.56     420 2027.53   432.5 2026.32  441.322027.515   446.9 2030.45
   462.9 2045.09   476.7 2055.47   491.3 2062.58     515 2071.92   529.2 2076.14
   553.4 2087.68   574.6 2089.26   578.9 2090.59   591.4 2097.31   595.6 2098.23
#Mann= 4 ,-1,0
       0      .1       0     420    .045       0  441.32      .1       0
     585     .06       0
Bank Sta=420,441.32
XS Rating Curve= 0 ,0
Exp/Cntr=0.3,0.1

Type RM Length L Ch R = 1 ,92133   ,312.4,320.5,321.1
XS GIS Cut Line= 3
 2171383.5016716 639548.492324432171719.11891502639510.796184769
2172003.89957201639307.290491063
#Sta/Elev= 30
       0 2078.49    36.9 2067.63      57 2062.71   129.5 2046.22   157.7 2042.81
   169.7 2040.15   177.8 2037.36   193.9 2036.97   209.9 2033.92   254.3 2029.41
   286.5 2028.57   310.6 2026.09   343.9 2026.41   361.1 2024.64   368.5 2022.59
   373.4 2022.01   378.32022.584   466.9 2022.92     485 2024.55   491.9 2026.62
   520.9  2040.5   535.7 2044.93   545.5 2050.31   560.3 2051.48   565.2 2052.74
     575 2059.18   609.4 2073.12   636.3 2082.55   658.6 2091.79   687.7 2100.25
#Mann= 4 ,-1,0
       0      .1       0   368.5    .045       0   378.3      .1       0
  667.73     .06       0
Bank Sta=368.5,378.3
XS Rating Curve= 0 ,0
Exp/Cntr=0.3,0.1

Type RM Length L Ch R = 1 ,91812   ,570.7,588.6,588.8
XS GIS Cut Line= 4
2171388.00103154639676.8588152882171621.83855461639719.948959658
2171996.88431086639653.9076981542172074.99822511639495.105526958
#Sta/Elev= 30
       0 2065.85    44.9 2065.75    65.3 2053.68   114.1 2042.63   126.3 2038.06
   150.7 2035.42   161.8 2032.37   211.7 2024.76   244.2 2024.61   264.5 2021.71
   280.8 2021.06   369.1  2020.8   451.3  2022.8   463.5 2021.06   487.9 2021.86
  498.562020.736   508.2 2019.48  518.012020.737   532.3 2021.39   544.8    2024
   597.6 2024.59   635.1 2026.07   655.1 2028.18   690.3  2029.2   708.6 2028.54
   739.8 2030.28   744.6 2032.68     762  2045.3     780 2050.62   795.6 2056.73
#Mann= 4 ,-1,0
       0      .1       0  498.56    .045       0  518.01      .1       0
  768.59     .06       0
Bank Sta=498.56,518.01
XS Rating Curve= 0 ,0
Exp/Cntr=0.3,0.1

Type RM Length L Ch R = 1 ,91224   ,176.2,170.5,165.7
XS GIS Cut Line= 4
2171300.95064015639906.4404127022171530.64038001 639922.95405413
2171793.35740273640085.0879881522171955.49133675 640191.67603737
#Sta/Elev= 30
       0  2080.1    23.3 2075.73    59.4 2066.15    75.4 2063.94    99.5 2057.07
   119.5 2054.62   123.5    2052   139.6 2047.21   192.6 2035.34   207.6 2030.05
   227.8 2030.39   247.5 2025.62   274.4 2022.33   321.4 2022.02   349.6  2020.6
   373.1 2017.66   407.4 2016.98   424.8 2019.31     453 2019.84  469.45 2018.42
   480.1 2016.88  495.552018.452   504.7 2020.22   535.3 2030.96   566.3 2032.78
   575.9 2040.82   647.7 2063.86   692.1  2082.8   714.4 2087.26     733 2094.65
#Mann= 5 ,-1,0
       0      .1       0  420.28     .06       0  469.45    .045       0
  495.55     .06       0     659      .1       0
Bank Sta=469.45,495.55
XS Rating Curve= 0 ,0
Exp/Cntr(USF)=0,0
Exp/Cntr=0.3,0.1

Type RM Length L Ch R = 1 ,91053   ,74.1,71.7,72.6
XS GIS Cut Line= 6
2171180.79081853 640125.850259952171500.55496618 640121.34653956
2171576.45403019640126.4936238782171655.18269955640151.371342157
2171716.73354488640148.3688618982171925.52714539 640262.00553518
#Sta/Elev= 30
       0  2074.5    16.2 2073.02    31.4  2067.5    47.4  2066.8    55.4 2063.77
    79.4 2057.61   107.4 2053.93   215.4 2034.41   259.8 2027.67   296.8  2024.9
   351.7 2024.17   383.8 2018.16   400.1 2017.27   416.3 2015.98   437.8 2017.25
   447.6 2018.47   463.9 2017.92   501.9 2019.45   532.2 2024.88   549.8 2023.39
   567.6 2024.67   579.3    2031   622.1 2047.09     654 2058.23   676.8 2062.82
   688.4 2069.24   726.9 2085.16     736 2087.22   754.2 2094.29   778.5 2101.64
#Mann= 7 ,-1,0
       0      .1       0      20     .06       0     120      .1       0
   400.1    .045       0   437.8      .1       0  519.14     .06       0
  690.81      .1       0
Bank Sta=400.1,437.8
XS Rating Curve= 0 ,0
Exp/Cntr=0.3,0.1

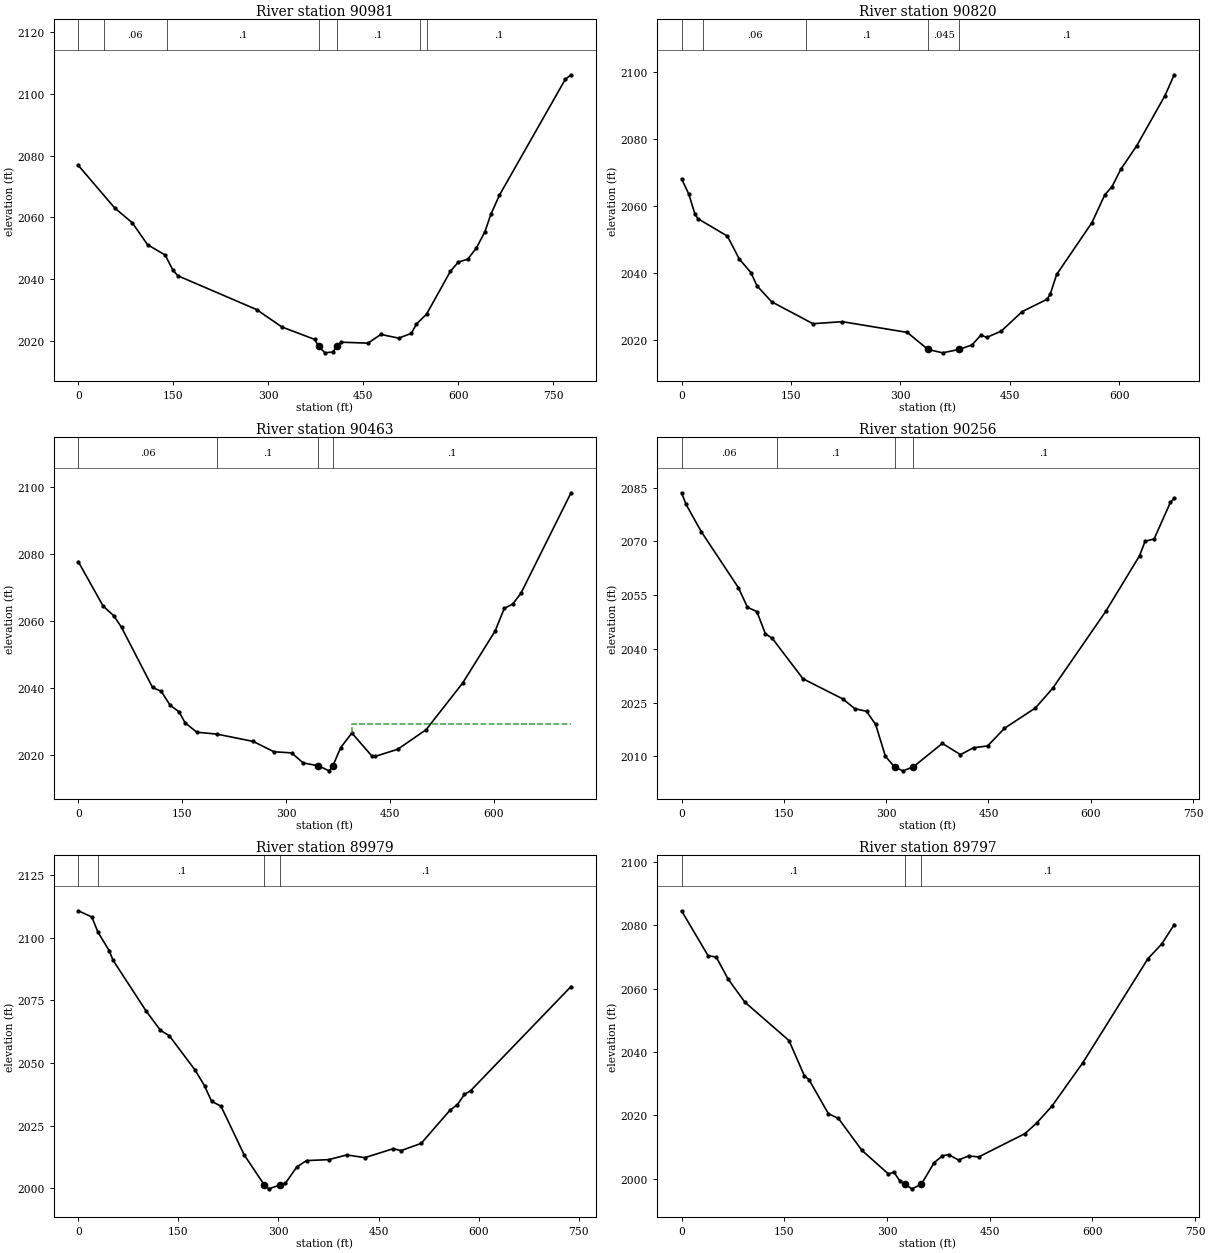
Type RM Length L Ch R = 1 ,90981   ,158.9,161.4,155.6
XS GIS Cut Line= 6
 2171162.8365482 640190.174797242171482.60069586640185.671076851
2171558.49975987640190.8181611682171637.22842923640215.695879447
2171698.77927455640212.6933991882171907.57287507 640326.33007247
#Sta/Elev= 30
       0 2076.82    57.3 2063.07    85.3 2058.23   109.3 2051.17   137.3 2047.78
   149.3 2042.93   157.3 2041.08   281.5 2030.15   321.6  2024.5   373.7 2020.45
  379.582018.193   389.8 2016.12   402.3 2016.41  408.232018.194   415.2 2019.57
   457.7 2019.26     478 2022.09   506.1 2020.88   526.1 2022.43   534.3 2025.46
   550.2 2028.65   587.9 2042.55   600.4 2045.52   615.3 2046.46   628.9 2050.07
   642.5  2055.4   651.7 2060.94   665.4 2067.21   769.3 2104.69   778.5  2106.2
#Mann= 7 ,-1,0
       0      .1       0      40     .06       0     140      .1       0
  379.58    .045       0  408.23      .1       0  539.14     .06       0
  550.81      .1       0
Bank Sta=379.58,408.23
XS Rating Curve= 0 ,0
Exp/Cntr=0.3,0.1

Type RM Length L Ch R = 1 ,90820   ,347.9,356.8,353.8
XS GIS Cut Line= 3
 2171177.8489495640292.2591260692171652.24083053640358.313691781
2171830.88840598640439.380658792
#Sta/Elev= 30
       0 2068.01      10 2063.37    18.5 2057.34    22.5 2056.07    62.9 2050.85
    79.1 2044.03    95.2 2039.93   103.3 2036.04   123.5 2031.25   180.1 2024.72
   220.4 2025.32   309.3 2022.12   337.6 2017.04   357.7 2016.02  380.522017.046
   398.1 2018.39   410.2 2021.32   418.3 2020.64     438 2022.49   466.8 2028.34
   500.9 2032.01   505.3  2033.6     514 2039.42   562.4 2054.91   579.9 2063.16
   589.9 2065.64   601.9 2070.82   623.9  2077.9   662.4 2092.79   675.1 2099.03
#Mann= 5 ,-1,0
       0      .1       0      30     .06       0     170      .1       0
   337.6    .045       0  380.52      .1       0
Bank Sta=337.6,380.52
XS Rating Curve= 0 ,0
Exp/Cntr(USF)=0,0
Exp/Cntr=0.3,0.1

Type RM Length L Ch R = 1 ,90463   ,194.8,207.4,215.3
XS GIS Cut Line= 5
2171116.22784532640510.9394440252171397.03000846640618.028234242
2171490.48164467640646.0311579232171625.21850819640615.025753983
2171800.52287831640613.688783122
#Sta/Elev= 30
       0 2077.73    35.8 2064.51    51.3 2061.62    62.4 2058.14   107.1 2040.27
   119.8 2039.06   132.7  2034.9   145.5 2032.98   154.1  2029.7   171.2 2026.89
     200 2026.33   252.5 2024.15   282.5 2021.06     308 2020.73   324.7 2017.74
  346.55 2016.87   362.3 2015.37  367.692016.869     379 2022.33   395.1 2026.65
   424.5 2019.67   428.6 2019.67   461.4 2021.81   502.4 2027.65   555.3 2041.61
     602 2057.06   615.3 2063.85   627.3  2065.1   639.3 2068.33   711.7 2098.32
#Mann= 4 ,-1,0
       0     .06       0     200      .1       0  346.55    .045       0
  367.69      .1       0
#XS Ineff= 2 , 0
                          395.11         2029.29
Permanent Ineff=
       F       F
Bank Sta=346.55,367.69
XS Rating Curve= 0 ,0
Exp/Cntr=0.3,0.1

Type RM Length L Ch R = 1 ,90256   ,280.4,276.9,269.3
XS GIS Cut Line= 4
2171078.27762406640596.2664011752171311.76680255 640718.14105558
2171363.89775326640825.196265486 2171693.4691829640908.402008013
#Sta/Elev= 30
       0 2083.58     6.7 2080.32    28.8 2072.76    83.4 2057.08    96.7 2051.59
   110.4 2050.42     123 2044.19     133 2042.95   178.1 2031.64   236.3 2026.03
   254.1  2023.3   271.2 2022.55   284.6 2018.89   298.9 2010.03   312.4    2007
   324.6 2005.94  339.81 2007.04   382.4  2013.6     409 2010.47   428.1 2012.39
   448.8 2012.89   473.5 2017.81   518.9  2023.5   544.1 2028.97     622 2050.46
   671.5 2065.98   679.8 2070.08   692.9 2070.67   716.9 2080.95   722.4 2082.01
#Mann= 4 ,-1,0
       0     .06       0     140      .1       0   312.4    .045       0
  339.81      .1       0
Bank Sta=312.4,339.81
XS Rating Curve= 0 ,0
Exp/Cntr=0.3,0.1

Type RM Length L Ch R = 1 ,89979   ,186,181.8,176.2
XS GIS Cut Line= 3
     2170944.855640790.9649767482171221.36347701641028.908213632
2171469.05007247641308.733213632
#Sta/Elev= 30
       0 2110.68    20.2 2108.19    29.5 2102.08    46.3 2094.73    51.9 2090.99
   101.5 2070.71   123.1 2062.97   136.3 2060.84   175.1 2047.08   189.1 2040.86
   199.6 2034.72   213.8 2032.71   248.7 2013.24  278.842001.253   285.5 1999.75
  301.712001.251   310.3 2001.95   327.3 2008.45   342.1 2011.03   375.1 2011.39
   402.5 2013.29   429.4 2012.19     472 2015.77   483.7 2014.99   513.9 2017.89
   556.8 2031.04   568.2 2033.37   578.8 2037.44     588  2038.9   738.5 2080.46
#Mann= 4 ,-1,0
       0     .06       0      30      .1       0  278.84    .045       0
  301.71      .1       0
Bank Sta=278.84,301.71
XS Rating Curve= 0 ,0
Exp/Cntr=0.3,0.1

Type RM Length L Ch R = 1 ,89797   ,222.9,229.9,233.9
XS GIS Cut Line= 4
2170832.49815547640966.2931939142171077.73385359641138.076653949
2171160.66379981641161.7709242982171435.51733587641351.325087095
#Sta/Elev= 30
       0 2084.55    38.7  2070.4    50.7 2069.93    67.8 2063.08    92.4 2055.74
   156.9 2043.62   179.3 2032.54   186.3 2031.21   214.5 2020.52   229.1 2019.05
   263.3 2008.99     302 2001.55   310.4 2002.06   318.6 1999.36   326.5 1998.25
   336.3 1996.83  350.16 1998.25   368.9  2005.1     381 2007.23   389.9 2007.64
   404.5 2005.92   419.4 2007.22   433.9 2006.89   501.7 2014.27   518.5 2017.57
   540.6 2022.83   586.2 2036.67   681.1 2069.43   701.2 2074.07   719.5 2080.17
#Mann= 3 ,-1,0
       0      .1       0   326.5    .045       0  350.16      .1       0
Bank Sta=326.5,350.16
XS Rating Curve= 0 ,0
Exp/Cntr(USF)=0,0
Exp/Cntr=0.3,0.1