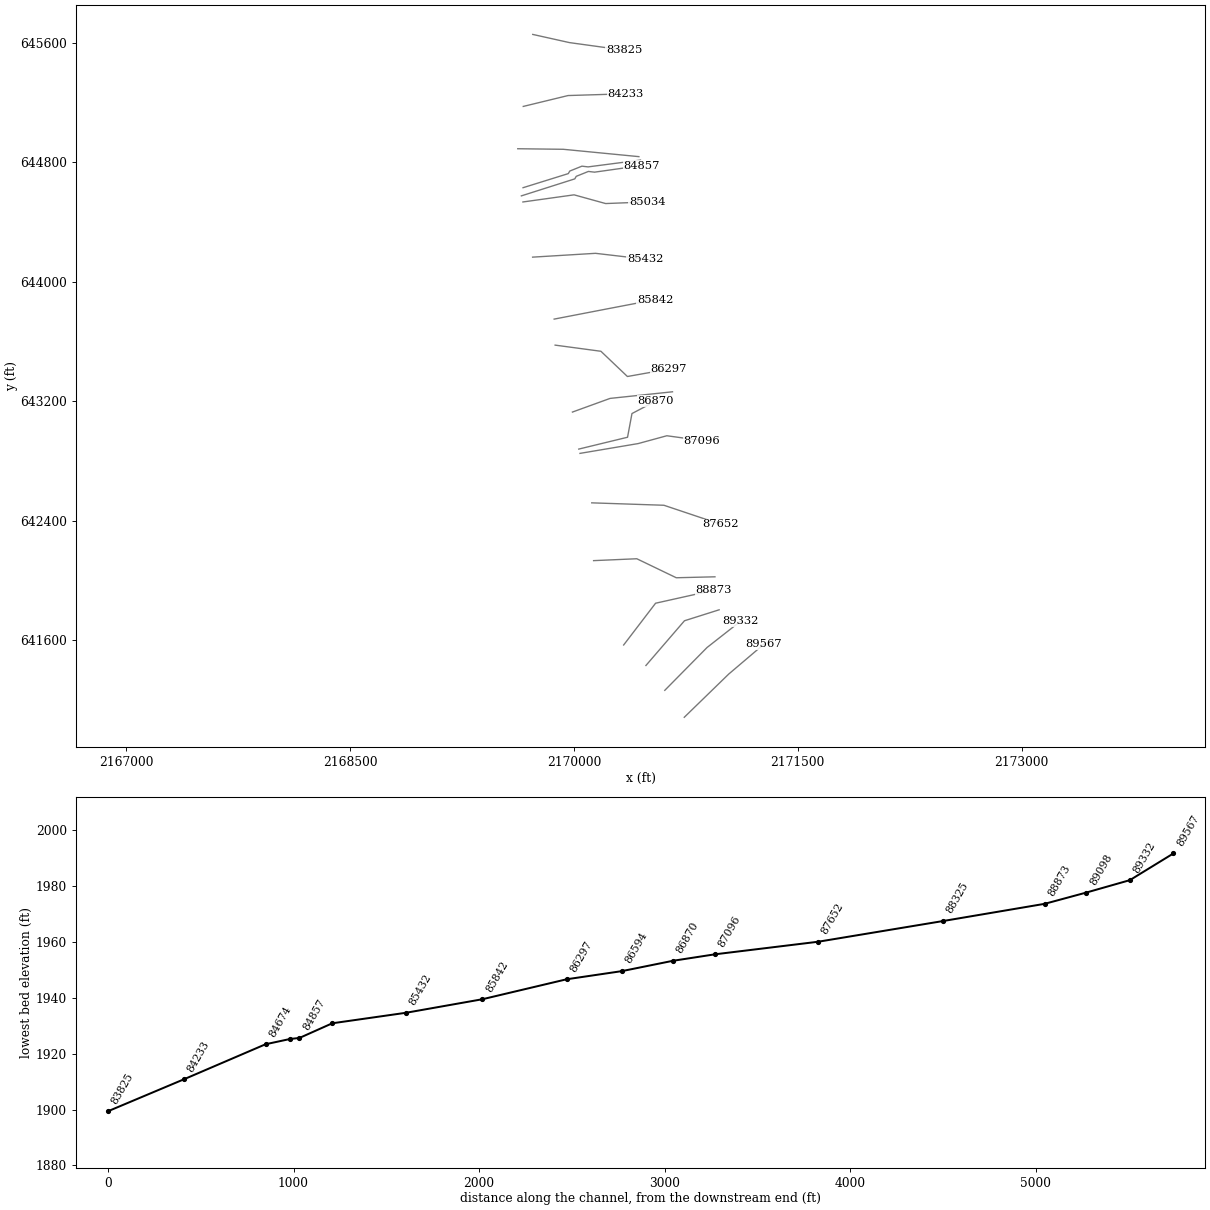
HEC-RAS study LIKANARV.prj: LIKANARV

--- LIKANARV.g01 (geometry) --- (continued)

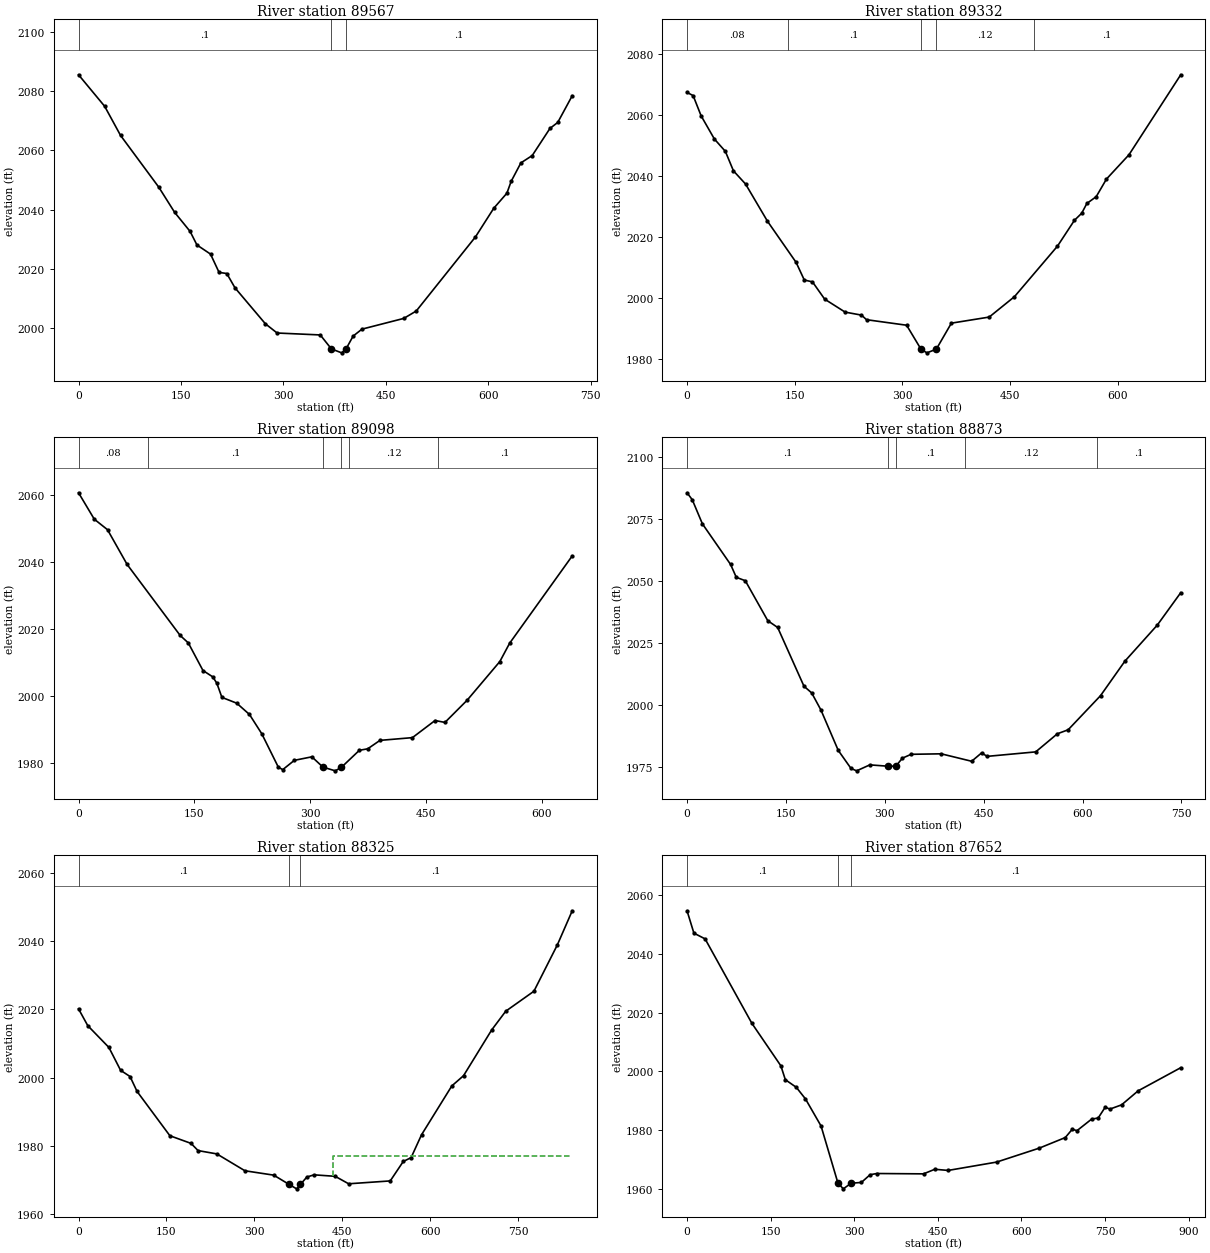
Type RM Length L Ch R = 1 ,89567   ,233.3,235.1,234.3
XS GIS Cut Line= 3
2170739.86652299641082.4577631162171037.80251649641372.069049218
2171272.16638507641571.086131425
#Sta/Elev= 30
       0 2085.47    38.3 2074.82    61.5 2065.01   117.6 2047.51   140.7 2039.05
   163.4  2032.6   173.4 2028.03   193.3 2024.95   205.8 2018.78   217.1  2018.4
   229.1 2013.57   273.6 2001.44   290.8 1998.32     354 1997.67  370.281992.959
   385.3 1991.63  391.791992.959   402.1 1997.28   415.1 1999.63   476.3 2003.25
   494.6 2005.75   581.3 2030.76   608.1 2040.43   627.3  2045.5   633.6 2049.52
   647.8 2055.73   664.4 2058.21   690.4 2067.37   701.8 2069.39     723  2078.4
#Mann= 3 ,-1,0
       0      .1       0  370.28    .045       0  391.79      .1       0
Bank Sta=370.28,391.79
XS Rating Curve= 0 ,0
Exp/Cntr=0.3,0.1

Type RM Length L Ch R = 1 ,89332   ,231.7,233.7,233.6
XS GIS Cut Line= 3
2170609.42395403 641263.146295842170892.67983234 641550.16509519
 2171116.7219113641725.850401298
#Sta/Elev= 30
       0 2067.32     8.5 2066.27    19.7 2059.61    38.1 2052.06    53.4 2048.02
    64.7 2041.63    81.5 2037.34   112.1 2025.14     152 2011.67   163.4  2005.9
   174.8 2005.29   191.8 1999.64   220.3 1995.39   243.1 1994.41   250.1 1992.91
     306  1991.1     3261983.258   334.3 1982.06  347.391983.258   368.4 1991.78
   421.1 1993.77   456.3 2000.45   516.2 2016.98   539.9 2025.46     550 2027.76
   557.2 2030.97   570.2 2033.18   584.5 2038.95   615.9 2046.91     688 2073.09
#Mann= 5 ,-1,0
       0     .08       0     140      .1       0     326    .045       0
  347.39     .12       0  483.25      .1       0
Bank Sta=326,347.39
XS Rating Curve= 0 ,0
Exp/Cntr=0.3,0.1

Type RM Length L Ch R = 1 ,89098   ,223.7,225.3,225.4
XS GIS Cut Line= 3
2170483.00766781641429.5161792492170741.27521462641729.248699171
2170973.47906405641802.700937255
#Sta/Elev= 30
       0 2060.79    20.4 2052.89    37.5 2049.75    62.9 2039.36   131.6 2018.12
   142.1  2015.9   161.1 2007.64   173.8 2005.74   179.1 2003.82   185.6 1999.61
   204.8 1997.87   221.3  1994.5   237.2 1988.75   258.7 1978.73   264.4    1978
   279.4 1980.78   302.1 1981.83   316.4 1978.76   332.4 1977.64  340.43 1978.71
   363.6 1983.78   374.4 1984.23   390.3 1986.75   432.3 1987.57   461.6 1992.69
   474.4 1992.12   503.1 1998.75   545.5 2010.33   558.1 2015.78   639.2 2041.91
#Mann= 6 ,-1,0
       0     .08       0      90      .1       0   316.4    .045       0
  340.43      .1       0     350     .12       0  465.65      .1       0
Bank Sta=316.4,340.43
XS Rating Curve= 0 ,0
Exp/Cntr(USF)=0,0
Exp/Cntr=0.3,0.1

Type RM Length L Ch R = 1 ,88873   ,555,548.1,536.7
XS GIS Cut Line= 3
2170333.76135533641566.9070129832170547.67787831641846.784884804
2170934.87687507641933.055276365
#Sta/Elev= 30
       0 2085.47     7.9 2082.69    23.3 2072.97    66.1 2056.62    74.7 2051.46
    88.4 2050.08   122.5    2034   137.5 2031.27   177.4 2007.64   189.1 2004.94
   203.1 1998.09   229.4 1981.82   248.7 1974.57   257.3 1973.59   277.3 1975.99
  304.431975.462  316.721975.456   326.7 1978.68   339.9 1980.24   385.6 1980.44
   431.8 1977.44     447 1980.83   455.2 1979.41     529 1981.22   561.8  1988.5
   578.2 1990.11   627.3 2003.83   664.2 2017.69   713.4 2032.22     749 2045.27
#Mann= 5 ,-1,0
       0      .1       0  304.43    .045       0  316.72      .1       0
  422.27     .12       0  622.27      .1       0
Bank Sta=304.43,316.72
XS Rating Curve= 0 ,0
Exp/Cntr=0.3,0.1

Type RM Length L Ch R = 1 ,88325   ,658,673.3,662.5
XS GIS Cut Line= 4
2170132.40564792642132.1469805252170421.82442012642144.789446282
2170686.26117091642017.4719642962170945.55395727642023.753510534
#Sta/Elev= 30
       0 2020.12    15.8  2015.2    51.8 2008.84    71.8 2002.13    87.9 2000.32
    99.9 1995.95   155.9 1982.98     192 1980.74     204 1978.63     236 1977.66
     284 1972.72   333.1 1971.44  359.561968.708   372.2 1967.43  378.611968.709
   389.7 1970.89     402 1971.53     438  1971.1     461 1968.91     532 1969.75
   554.2 1975.44   567.6 1976.57   585.4 1983.26   637.1 1997.57   657.1 2000.56
   705.1 2013.95   729.1 2019.44   777.2 2025.29   817.2 2038.86   842.6 2048.85
#Mann= 3 ,-1,0
       0      .1       0  359.56    .045       0  378.61      .1       0
#XS Ineff= 2 , 0
                          434.61         1976.91
Permanent Ineff=
       F       F
Bank Sta=359.56,378.61
XS Rating Curve= 0 ,0
Exp/Cntr=0.3,0.1

Type RM Length L Ch R = 1 ,87652   ,549.4,555.4,553.2
XS GIS Cut Line= 3
2170119.84240779642519.3873028622170603.62968091642503.180615462
2170984.76668091642375.404322868
#Sta/Elev= 30
       0 2054.69    12.3 2047.08    32.4 2045.12   116.4 2016.36   168.4  2001.9
   176.4 1997.18   196.1 1994.58   212.5 1990.65   240.5 1981.42  270.871961.943
   280.5 1960.02  294.431961.941   312.8 1962.19   328.5 1964.82   340.5 1965.24
   424.4 1965.12   444.6 1966.68   468.6 1966.29   555.6 1969.13   632.3 1973.89
   678.8 1977.48   691.4 1980.32   699.8 1979.82   726.2 1983.78   737.8 1984.12
   750.4  1987.8   758.9 1987.17   779.8 1988.61   809.5 1993.38     886 2001.26
#Mann= 3 ,-1,0
       0      .1       0  270.87    .045       0  294.43      .1       0
Bank Sta=270.87,294.43
XS Rating Curve= 0 ,0
Exp/Cntr=0.3,0.1

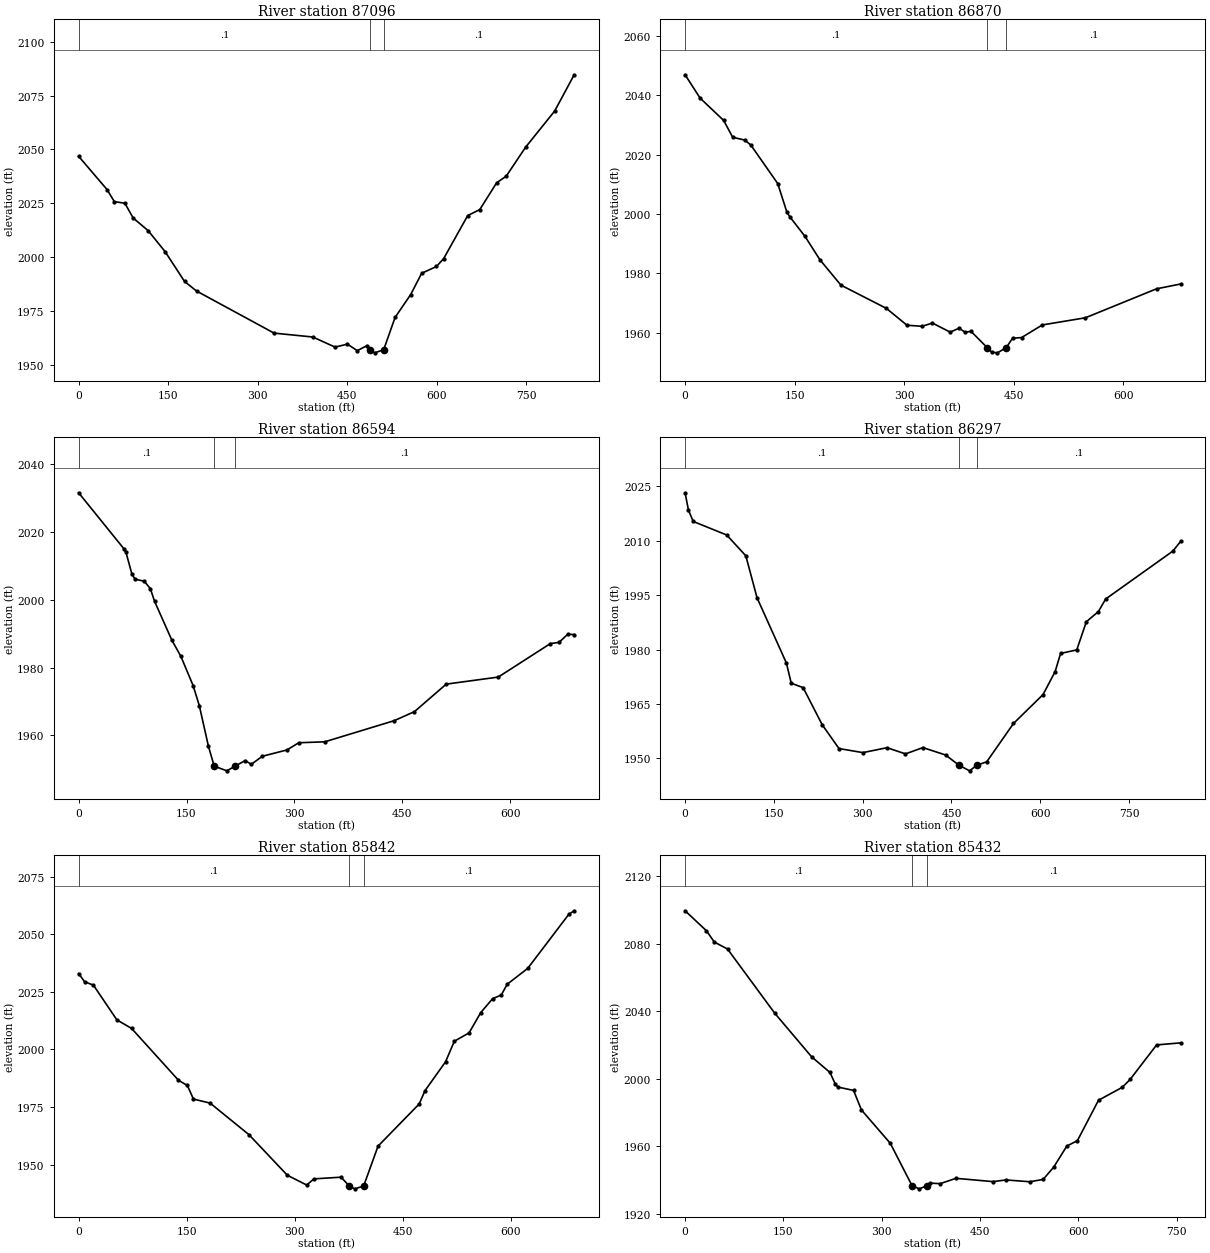
Type RM Length L Ch R = 1 ,87096   ,209.8,226.6,236.1
XS GIS Cut Line= 4
2170041.18260195642850.8443683092170430.88499026642916.518559221
2170622.99059751642968.9702775592170856.85391779642937.029865329
#Sta/Elev= 30
       0 2046.79    47.7 2031.31    59.8 2025.75    77.5    2025    91.4 2018.13
   116.6 2012.24     145 2002.48   177.5 1988.67   197.7 1984.21   327.5 1964.69
   392.4 1962.88   429.7  1958.2   450.4 1959.56     467 1956.54   483.6 1958.93
  489.061956.937     496 1955.53  511.141956.951   530.3 1971.97   556.4 1982.58
   574.8 1992.46   599.6 1995.62   611.7 1999.28     652 2019.27   672.2 2022.04
   700.5  2034.5   716.6 2037.57   748.9 2050.98   797.7 2067.79   830.4 2084.64
#Mann= 3 ,-1,0
       0      .1       0  489.06    .045       0  511.14      .1       0
Bank Sta=489.06,511.14
XS Rating Curve= 0 ,0
Exp/Cntr=0.3,0.1

Type RM Length L Ch R = 1 ,86870   ,282,275.3,251.3
XS GIS Cut Line= 4
2170032.81653117642879.6055246442170359.79746199642958.981330315
2170389.41529993643117.7329416582170549.35162479643201.847601399
#Sta/Elev= 30
       0 2046.96    20.6 2039.08    52.8 2031.57    65.2 2025.89    81.7 2024.94
    89.9 2023.31   126.9 2010.28   139.3 2000.72   143.4 1999.08     164 1992.55
   184.6 1984.61   213.4 1976.04   275.7  1968.2   303.9 1962.51   324.5 1962.17
   338.8 1963.25   363.1 1960.18   375.3 1961.54   383.5 1960.14   391.6 1960.46
   413.8 1954.96   420.1 1953.42   427.8 1953.21  439.79 1954.96   448.6 1958.16
   460.8 1958.35   489.3 1962.62   548.3 1965.03   645.7  1974.8   678.7 1976.42
#Mann= 3 ,-1,0
       0      .1       0   413.8    .045       0  439.79      .1       0
Bank Sta=413.8,439.79
XS Rating Curve= 0 ,0
Exp/Cntr(USF)=0,0
Exp/Cntr=0.3,0.1

Type RM Length L Ch R = 1 ,86594   ,307.9,297.5,275.1
XS GIS Cut Line= 3
2169990.47806157643127.6853290432170242.71412164643219.208279319
2170661.03369365643263.555779248
#Sta/Elev= 30
       0 2031.58      63 2015.04    65.6 2014.18    74.1 2007.57    78.4 2006.09
    91.2 2005.47    99.7  2003.3   105.5 1999.58   129.5 1988.13   142.2 1983.28
   159.2 1974.67   167.8 1968.75   180.5 1956.74  188.451950.906   206.1 1949.51
  217.631950.909   231.6 1952.54   240.1 1951.43   255.4 1953.81   289.9 1955.69
     306  1957.8   342.2 1958.08   438.7 1964.31   466.9 1966.98   511.1  1975.1
   583.5 1977.19   655.9 1987.07     668 1987.43   680.1 1989.83     689 1989.73
#Mann= 3 ,-1,0
       0      .1       0  188.45    .045       0  217.63      .1       0
Bank Sta=188.45,217.63
XS Rating Curve= 0 ,0
Exp/Cntr=0.3,0.1

Type RM Length L Ch R = 1 ,86297   ,431.3,454.6,461.5
XS GIS Cut Line= 4
2169874.51600451643576.2538963812170181.40836027643535.029189216
2170358.92742663643366.0222120532170637.00759003643415.491986485
#Sta/Elev= 30
       0 2023.18     5.7 2018.37    13.8 2015.28    70.3 2011.55   102.6 2005.82
   121.6 1994.24   171.2 1976.27   179.3 1970.73   199.4 1969.52   231.7 1959.28
     260 1952.74   300.3 1951.62   341.1 1952.97   372.3 1951.27   401.8    1953
     440 1950.97  462.911948.128   480.6  1946.6  492.721948.127   509.6 1949.09
   554.8 1959.64   604.8 1967.62   625.1 1973.91   634.4 1978.93   661.7 1979.91
   677.9 1987.67   698.2 1990.45   710.5 1993.92     824 2007.11   837.2 2009.79
#Mann= 3 ,-1,0
       0      .1       0  462.91    .045       0  492.72      .1       0
Bank Sta=462.91,492.72
XS Rating Curve= 0 ,0
Exp/Cntr=0.3,0.1

Type RM Length L Ch R = 1 ,85842   ,411.2,410.5,407.2
XS GIS Cut Line= 3
2169868.05209461643750.6040225262170219.05099099643818.343698155
2170543.43379727643880.477333237
#Sta/Elev= 30
       0 2033.01     8.3 2029.44    20.5 2027.97    53.1 2012.87    73.5 2009.16
   138.6 1986.63   150.9 1984.36   159.4 1978.44   182.5 1976.71   236.4 1962.99
   289.7 1945.35   316.5 1941.12   326.7 1943.78   364.3 1944.52  375.741940.647
   383.1 1939.45  395.561940.643   415.6 1958.02   472.7 1976.34   480.8 1982.14
   509.3 1994.67   521.5  2003.6   541.9 2007.22   558.2 2016.06   574.5 2022.06
   586.7 2023.69   594.8 2028.35   623.3 2035.24   680.4 2058.76   687.8 2060.28
#Mann= 3 ,-1,0
       0      .1       0  375.74    .045       0  395.56      .1       0
Bank Sta=375.74,395.56
XS Rating Curve= 0 ,0
Exp/Cntr=0.3,0.1

Type RM Length L Ch R = 1 ,85432   ,398.6,398.3,391.5
XS GIS Cut Line= 3
2169723.62418021644165.8191261442170144.86324328644191.379126144
 2170476.6329099644152.692590031
#Sta/Elev= 30
       0 2099.39    32.6 2087.53    44.6 2080.84    64.7 2076.74   136.8 2038.67
   192.9  2012.9     221 2003.59     229 1996.82     233 1994.92     257 1992.96
     269 1981.38   313.1 1961.58  346.171936.517   357.2 1934.62  369.271936.517
   373.2 1937.99   389.3 1937.71   413.3 1940.85   469.6  1938.9   489.8 1939.89
     526 1938.82   546.2  1940.2   562.3 1947.44   582.4 1959.99   598.5 1963.17
   630.7 1987.11     667 1994.78   679.1 1999.53   719.3  2019.9     756 2021.12
#Mann= 3 ,-1,0
       0      .1       0  346.17    .045       0  369.27      .1       0
Bank Sta=346.17,369.27
XS Rating Curve= 0 ,0
Exp/Cntr=0.3,0.1

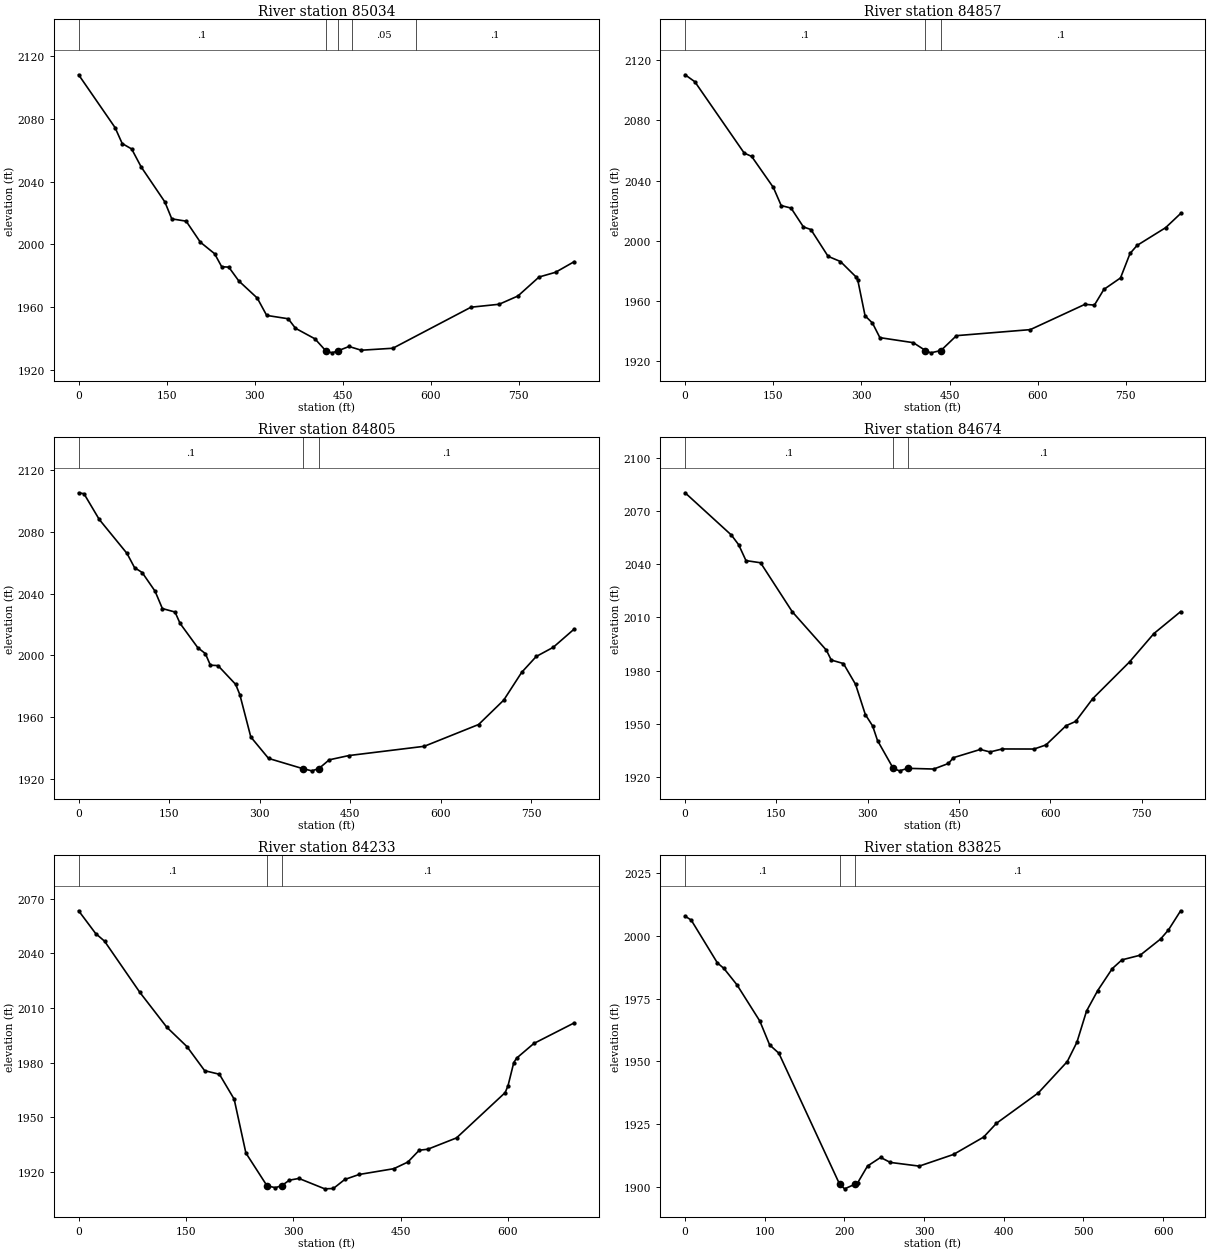
Type RM Length L Ch R = 1 ,85034   ,168.2,176.7,184.6
XS GIS Cut Line= 4
      2169658.63      644535.4762170001.55566662644583.289959454
2170213.00688601644524.874505463     2170491.959      644535.746
#Sta/Elev= 30
       0 2108.23    62.1 2074.54    74.3 2064.35    90.4 2060.91   106.6 2049.46
     147 2027.12   158.8 2016.31   183.3 2014.85   207.5 2001.44   231.8 1994.09
   243.9 1985.78     256 1985.52     273 1976.74   304.5  1965.8   320.6 1954.73
   357.3 1952.59   369.7 1946.52   402.9 1939.78  421.421932.121     432 1930.85
  441.87 1932.12     461  1934.9   481.8 1932.52   535.7 1933.78   668.9 1959.96
   716.9 1961.84   748.9 1967.11   784.9 1979.22     813 1982.23   844.8    1989
#Mann= 5 ,-1,0
       0      .1       0  421.42    .045       0  441.87      .1       0
  466.24     .05       0  575.61      .1       0
Bank Sta=421.42,441.87
XS Rating Curve= 0 ,0
Exp/Cntr=0.3,0.1

Type RM Length L Ch R = 1 ,84857   ,51.6,51.8,48.7
XS GIS Cut Line= 6
     2169648.337      644576.3622170006.28612014644690.251118164
2170016.01415618644707.2751812362170097.48645802644740.107302875
 2170138.8306112644735.2432848552170453.48902253644779.734774743
#Sta/Elev= 30
       0 2110.21    16.6 2105.58   100.6 2058.21   113.2 2056.03   150.2 2035.38
   163.5 2023.39   180.3  2021.7   201.3  2009.2     214 2007.47   243.3 1989.67
   264.3 1986.24   290.3 1976.21   293.7 1974.09   306.2 1950.21   318.8 1945.38
   331.4  1935.7   388.2 1932.36  408.881927.162   418.1 1925.61  435.311927.163
   461.7 1937.02   587.3 1941.02   680.2  1957.8   696.4  1957.3   712.5 1967.72
   740.8 1975.34     757 1991.57   768.9  1996.9   817.5 2008.69   843.1 2018.12
#Mann= 3 ,-1,0
       0      .1       0  408.88    .045       0  435.31      .1       0
Bank Sta=408.88,435.31
XS Rating Curve= 0 ,0
Exp/Cntr=0.3,0.1

Type RM Length L Ch R = 1 ,84805   ,135.8,131.4,124.1
XS GIS Cut Line= 6
2169659.64631611644631.1248884732169962.87523351644725.557934555
2169972.60326955644742.581997627 2170054.0755714644775.414119266
2170095.41972457644770.5501012462170446.55827106644816.257595639
#Sta/Elev= 30
       0 2105.39     8.9 2104.76    34.1 2088.15    80.2 2066.08    92.7 2056.87
   105.3 2053.73   126.7 2041.62   138.8 2030.37   159.8 2028.12   168.1 2020.78
   197.5 2005.02     210 2001.22   218.4 1993.68     231 1993.41   260.3 1981.24
   267.2 1974.59   285.4 1947.16   314.8 1933.28  371.131926.694   386.5 1925.22
  398.211926.695   415.4 1932.36   447.9 1935.12   572.9 1941.12     663 1955.24
   704.6 1971.02   734.4 1989.04   758.5 1999.31   786.7 2005.26   821.4 2017.08
#Mann= 3 ,-1,0
       0      .1       0  371.13    .045       0  398.21      .1       0
Bank Sta=371.13,398.21
XS Rating Curve= 0 ,0
Exp/Cntr=0.3,0.1

Type RM Length L Ch R = 1 ,84674   ,434.6,440.8,441.6
XS GIS Cut Line= 3
2169624.13666163644892.2120657372169929.67783631644888.459852504
2170435.86597263644839.230908057
#Sta/Elev= 30
       0  2080.4      76 2056.53      88 2051.06     100 2042.09     124 2040.87
   176.1 2013.18   232.1  1991.5   240.1 1985.92   260.1 1983.94   280.1 1972.16
   296.1 1955.13   308.1  1948.7   316.1 1940.46     3421924.704   352.3 1923.34
  365.661924.759   408.5 1924.36   432.7 1927.51   440.7 1930.77   484.9 1935.41
     501 1934.01   521.1  1935.7   573.3 1935.66   592.9 1937.97   625.8 1948.82
   641.6 1951.25   669.7 1964.12   730.1 1984.85   770.2 2000.89   814.1 2013.28
#Mann= 3 ,-1,0
       0      .1       0     342    .045       0  365.66      .1       0
Bank Sta=342,365.66
XS Rating Curve= 0 ,0
Exp/Cntr=0.3,0.1

Type RM Length L Ch R = 1 ,84233   ,411.4,408.1,403.1
XS GIS Cut Line= 3
2169661.04328935645175.7445657122169961.31608221645248.631842077
2170344.52055598645260.389634937
#Sta/Elev= 30
       0 2063.43    23.8 2050.94    36.2 2046.75    85.5 2018.66     123 1999.59
   151.4 1988.85   176.1 1975.64   196.7 1973.69   217.3 1960.03   233.7 1930.45
   263.2 1912.46   274.9 1911.41  283.961912.562   294.4 1915.53   307.8 1916.49
   343.9 1910.78   355.9 1910.97   371.9 1915.93   391.9 1918.66   440.4 1921.84
     460 1925.48   475.9 1931.97   487.9 1932.53     528 1938.74     596 1963.62
     600 1967.43     608  1980.1     612 1982.54     636 1990.57   692.4 2001.87
#Mann= 3 ,-1,0
       0      .1       0   263.2    .045       0  283.96      .1       0
Bank Sta=263.2,283.96
XS Rating Curve= 0 ,0
Exp/Cntr=0.3,0.1

Type RM Length L Ch R = 1 ,83825   ,322.8,319.2,315.2
XS GIS Cut Line= 3
2169724.66053597645658.1901119512169970.98672363645603.309477014
2170337.12715792645552.889036235
#Sta/Elev= 30
       0 2007.77     7.7 2006.19    40.5 1989.19    48.7 1986.99    65.1 1980.47
    93.8 1966.07   106.1 1956.59   117.7 1953.28  194.021901.163   200.3 1899.38
  212.791901.162   216.7 1901.83     229 1908.46   245.4 1911.86   257.6 1909.88
   293.9 1908.41   336.9 1913.05   374.7 1919.95   390.8 1925.43   443.3 1937.49
   479.7 1949.96   491.8 1957.65   503.9 1970.06   517.9 1978.19   536.2 1986.92
   548.3 1990.39   571.2 1992.24   596.8 1998.67   606.7 2002.28     622  2009.9
#Mann= 3 ,-1,0
       0      .1       0  194.02    .045       0  212.79      .1       0
Bank Sta=194.02,212.79
XS Rating Curve= 0 ,0
Exp/Cntr=0.3,0.1