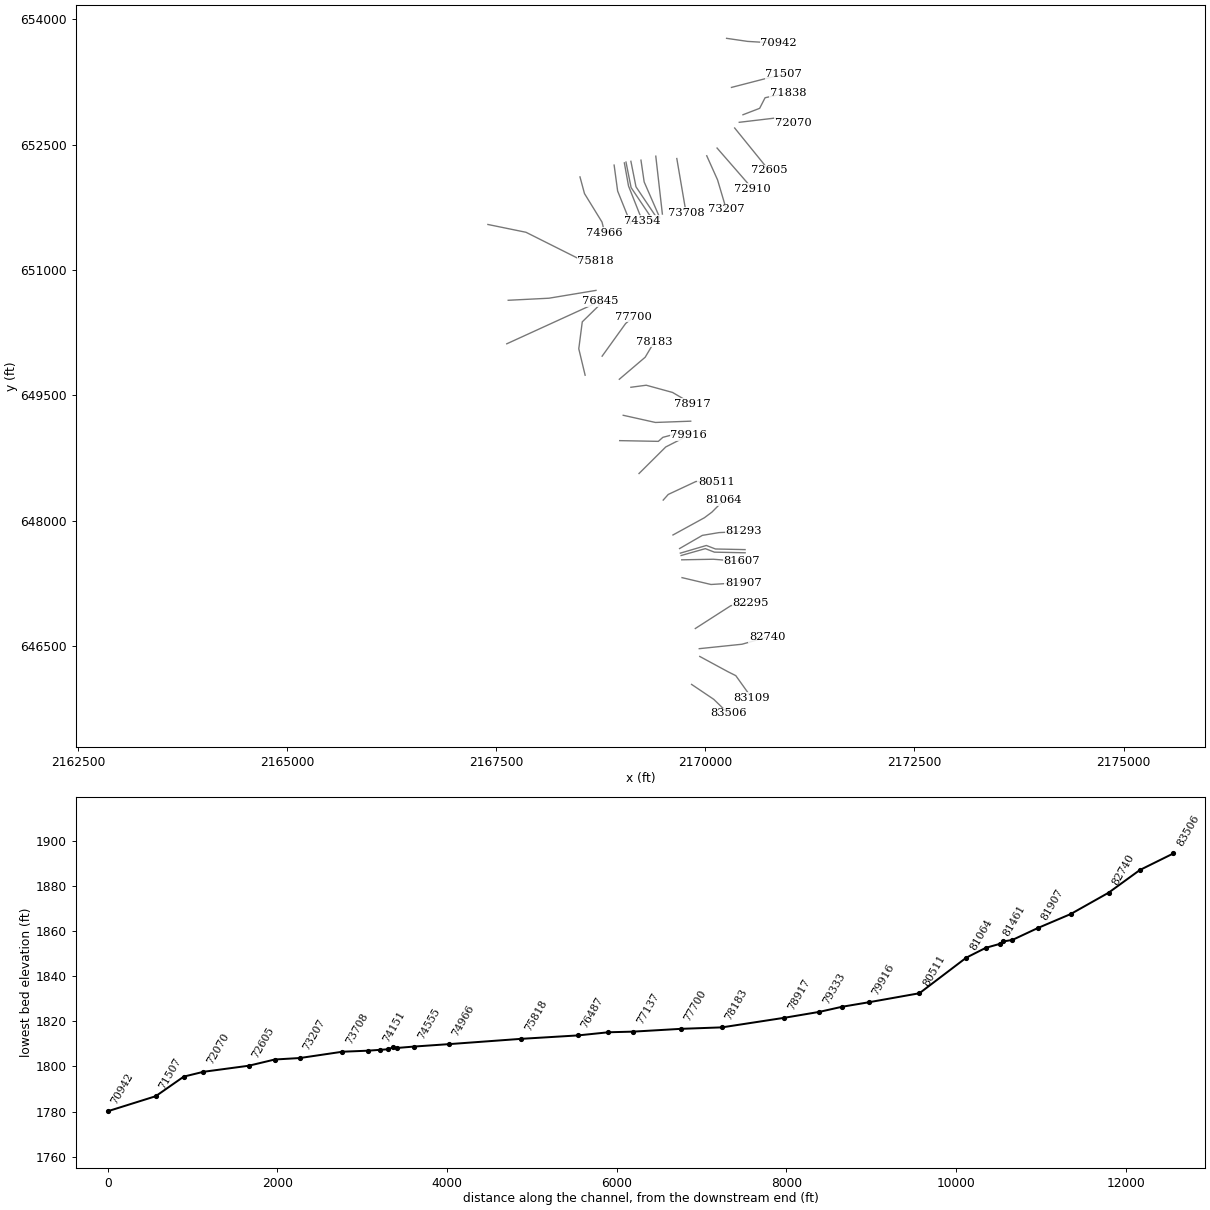
HEC-RAS study LIKANARV.prj: LIKANARV

--- LIKANARV.g01 (geometry) --- (continued)

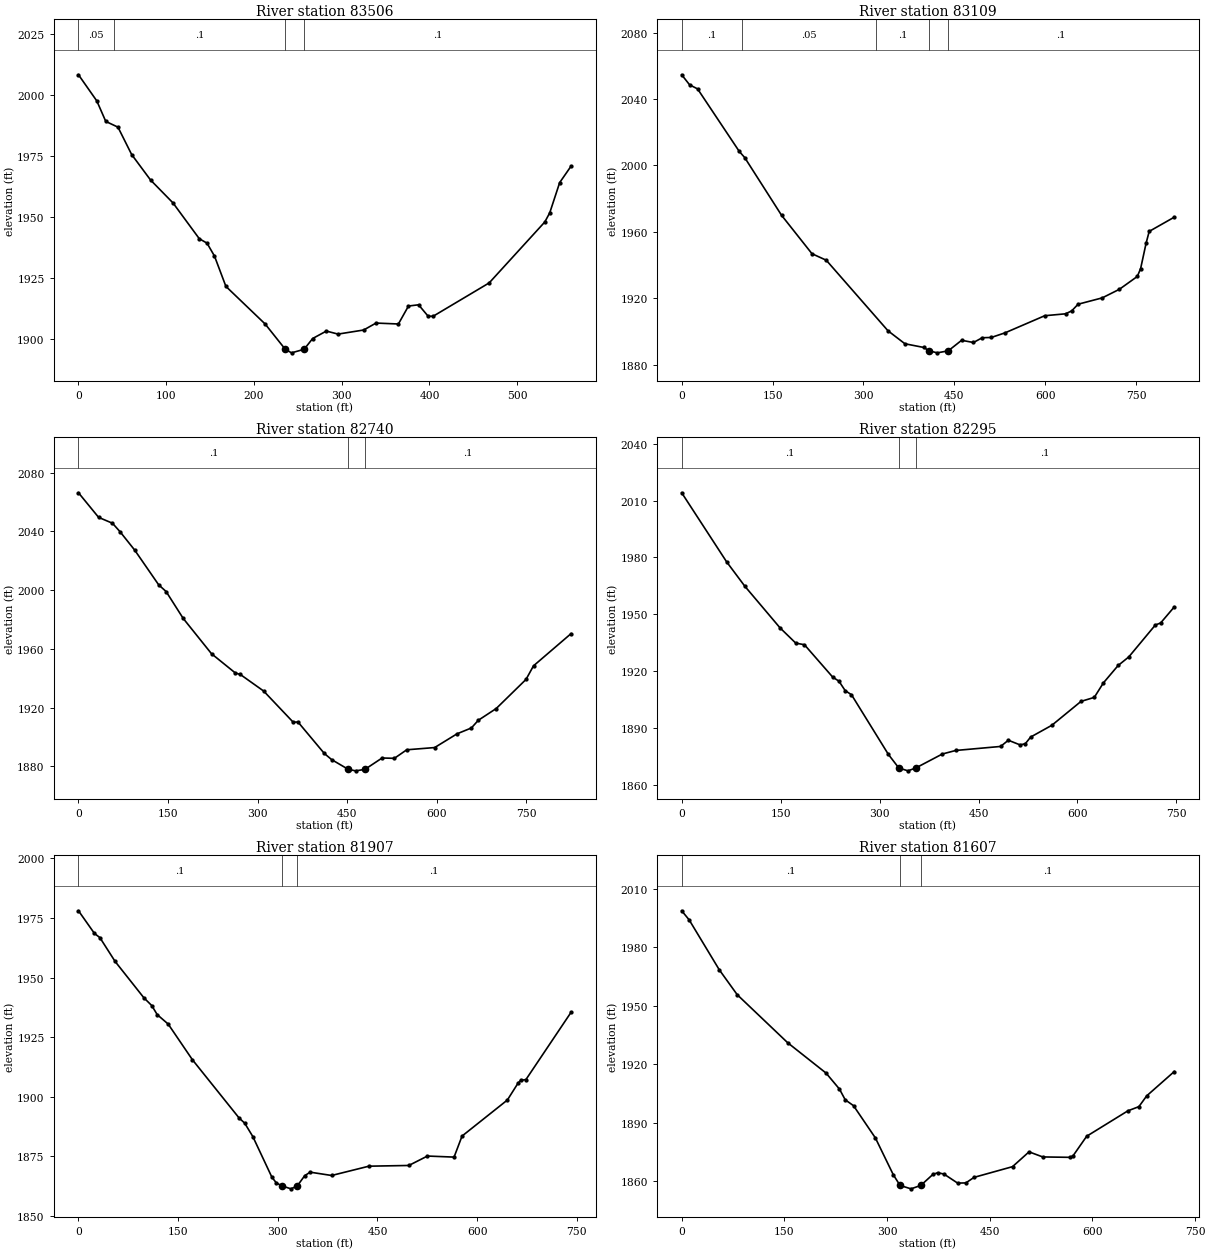
Type RM Length L Ch R = 1 ,83506   ,388.4,396.3,392.6
XS GIS Cut Line= 3
2169834.84454246646043.0465327222170099.99461168 645864.41196701
2170273.60539156645696.264124933
#Sta/Elev= 30
       0 2008.38    20.9 1997.66    31.1 1989.27      45 1986.92    60.6 1975.71
    82.1 1965.28   107.7 1955.89   137.7 1941.21   146.5  1939.4     155  1934.1
     168 1921.69   212.7 1906.29  235.711895.906   242.8 1894.46  257.141895.909
   266.9 1900.33   282.5 1903.38   295.8 1902.14     325 1903.81   339.1 1906.66
   364.6 1906.28   376.1 1913.64   387.6 1914.14   398.5 1909.46   404.2 1909.45
   468.1 1923.12   531.5 1948.09   537.1 1951.83   548.4  1964.2   561.4 1970.95
#Mann= 4 ,-1,0
       0     .05       0      40      .1       0  235.71    .045       0
  257.14      .1       0
Bank Sta=235.71,257.14
XS Rating Curve= 0 ,0
Exp/Cntr=0.3,0.1

Type RM Length L Ch R = 1 ,83109   ,363.1,369.1,378.7
XS GIS Cut Line= 4
2169932.78540338646377.2697140472170267.64164143 646195.76196701
2170363.64132064646147.5799741852170552.52324013645883.490963765
#Sta/Elev= 30
       0 2054.59      13 2048.55    26.2 2046.09    94.9 2008.48     104 2004.71
   164.8 1969.95     215  1946.8   238.6 1942.88   340.5 1900.37   368.4 1892.56
   399.4 1890.34   408.41888.296   421.8 1887.09  439.961888.297     462 1894.65
   481.5 1893.32   496.1 1896.19   510.9 1896.35   533.4  1899.1   599.2 1909.45
   633.6  1910.6   643.7 1912.37   654.2 1916.38     694 1920.19   722.4 1925.37
   751.9 1933.08   757.4 1937.79   766.6 1953.35   771.6 1960.25     813 1968.82
#Mann= 5 ,-1,0
       0      .1       0     100     .05       0     320      .1       0
   408.4    .045       0  439.96      .1       0
Bank Sta=408.4,439.96
XS Rating Curve= 0 ,0
Exp/Cntr=0.3,0.1

Type RM Length L Ch R = 1 ,82740   ,441.1,445.3,453.2
XS GIS Cut Line= 3
     2169926.622      646470.3122170438.17700882646523.558285181
2170736.67155598  646608.5856874
#Sta/Elev= 30
       0 2066.26    33.7 2049.53    56.9 2045.53    69.6 2039.75    94.1 2027.25
   134.3 2003.59   146.7 1999.06   175.2 1980.82   222.7 1956.73   262.6 1943.62
     271 1942.59     310 1931.33   359.5 1910.11   367.5 1910.26   411.5 1888.88
   423.8 1884.67  451.831878.009     464 1877.02  479.551878.008   508.3 1885.76
   528.9 1885.54   549.6 1891.35   596.3 1892.86   633.8 1902.22   657.8  1906.2
   669.4 1911.43   699.4 1919.43   749.3 1939.26   761.8 1948.48   824.7 1970.41
#Mann= 3 ,-1,0
       0      .1       0  451.83    .045       0  479.55      .1       0
Bank Sta=451.83,479.55
XS Rating Curve= 0 ,0
Exp/Cntr=0.3,0.1

Type RM Length L Ch R = 1 ,82295   ,394.5,387.5,375.3
XS GIS Cut Line= 3
2169879.66427031646711.6456967012170304.75161168646985.026779828
2170544.71681282647011.032729691
#Sta/Elev= 30
       0 2014.07      68 1977.74    95.7 1964.85   149.1  1942.9   172.9 1934.88
   186.1 1934.02   228.9 1916.98   238.4 1914.82   247.9 1909.82   257.4 1907.69
   313.4 1876.22  329.12 1869.12     343 1867.59  355.01 1869.12   395.1 1876.45
   415.4 1878.32   483.5 1880.44   495.2 1883.71   512.9 1881.27   520.9 1881.86
     529 1885.38   561.2  1891.6   605.4 1904.18   625.5 1906.28   639.3 1913.91
   661.7  1923.1   677.8 1927.59   718.1 1944.42   726.1 1945.49   746.8 1953.95
#Mann= 3 ,-1,0
       0      .1       0  329.12    .045       0  355.01      .1       0
Bank Sta=329.12,355.01
XS Rating Curve= 0 ,0
Exp/Cntr=0.3,0.1

Type RM Length L Ch R = 1 ,81907   ,296.4,300.6,302.9
XS GIS Cut Line= 3
2169720.83027031647320.1879168732170067.15362564647238.209426392
2170451.89218718647262.057909897
#Sta/Elev= 30
       0    1978      24  1968.5    32.2 1966.75    55.1 1956.76    98.3 1941.55
   110.3 1938.24   118.5 1934.45     135 1930.49   171.5 1915.52   241.8 1891.08
   250.1 1888.96   262.4 1883.31   291.1 1866.27   297.8 1863.88  306.011862.638
   319.9 1861.39  329.321862.637   340.5 1866.91   348.7 1868.38     381 1866.99
   437.1 1870.89   497.2 1871.19   525.2 1875.14   565.3  1874.7   577.3 1883.52
   645.5 1898.63   661.4 1905.63   665.5 1906.87   673.5 1907.23   741.4 1935.43
#Mann= 3 ,-1,0
       0      .1       0  306.01    .045       0  329.32      .1       0
Bank Sta=306.01,329.32
XS Rating Curve= 0 ,0
Exp/Cntr=0.3,0.1

Type RM Length L Ch R = 1 ,81607   ,113.5,105.8,101.1
XS GIS Cut Line= 3
2169717.26457361647533.5104314772170096.12655457647540.261663711
2170435.77674873647513.458476529
#Sta/Elev= 30
       0 1998.77    10.9  1994.1    54.9 1968.49    81.1 1955.71   154.9 1931.04
   210.9 1915.49   230.5 1907.27   238.9 1901.77     251 1898.77     283 1882.19
   309.1 1863.34  318.981857.848     335  1856.1  349.241857.847     367 1863.51
     374 1864.36     383 1863.71     403 1859.06   415.1 1859.13   427.1 1861.99
   483.3 1867.48   507.4 1875.08   527.4 1872.47   567.6 1872.26   571.6    1873
   591.6 1883.08   651.8 1896.12   667.9 1898.28   679.3 1903.81   719.6 1916.29
#Mann= 3 ,-1,0
       0      .1       0  318.98    .045       0  349.24      .1       0
Bank Sta=318.98,349.24
XS Rating Curve= 0 ,0
Exp/Cntr=0.3,0.1

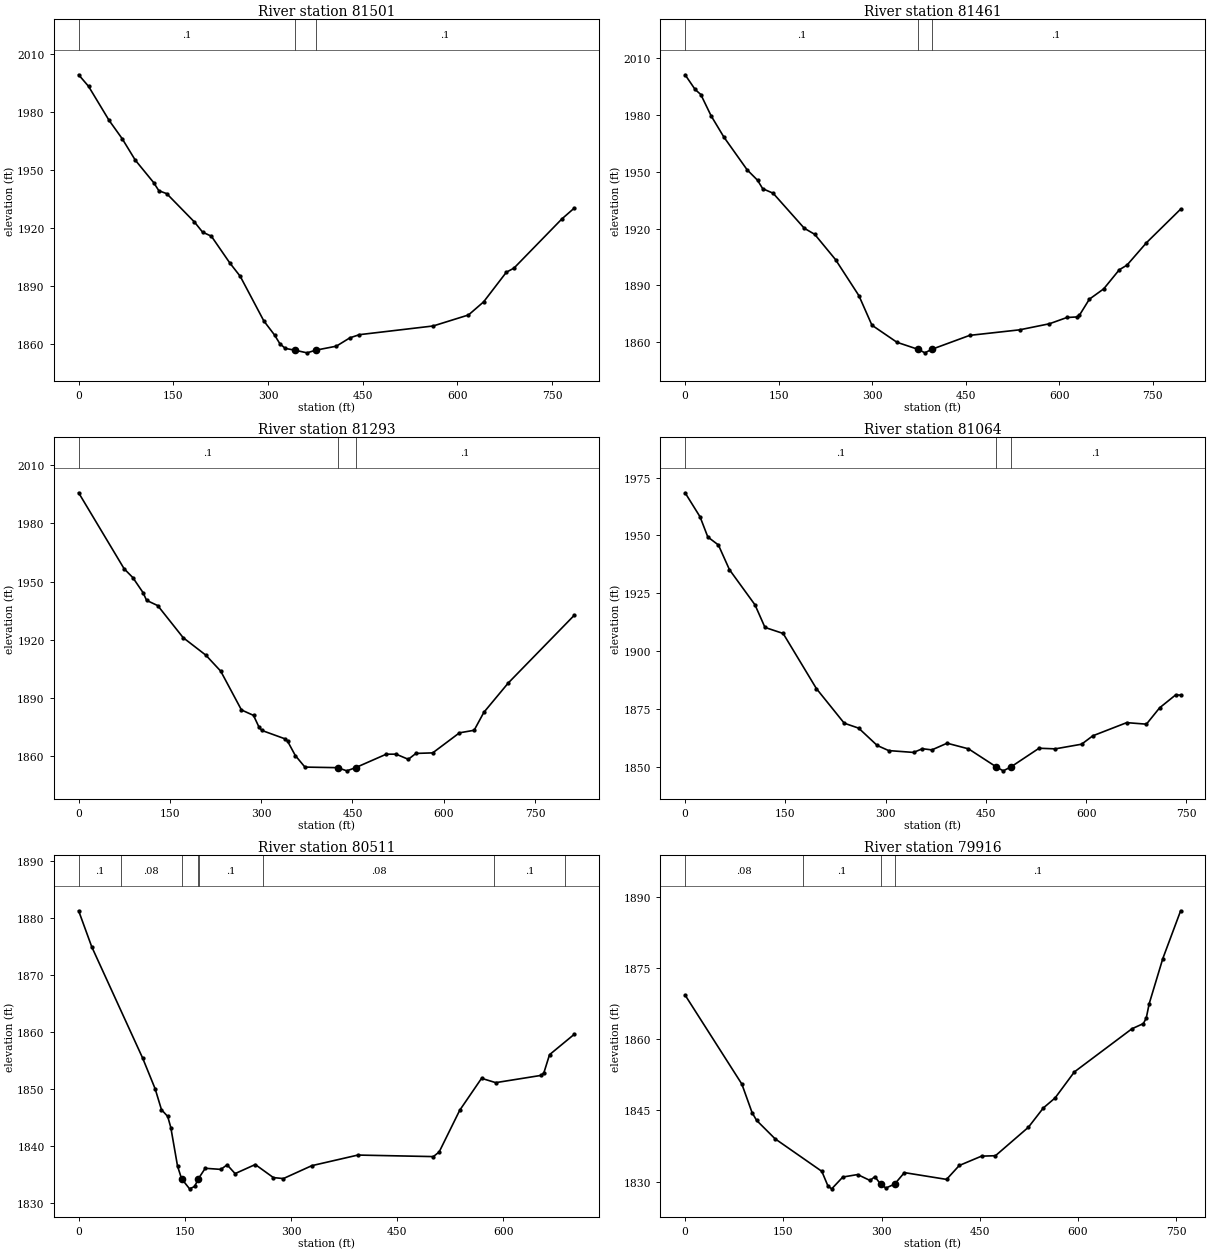
Type RM Length L Ch R = 1 ,81501   ,40.4,39.9,40.3
XS GIS Cut Line= 4
2169709.90697218647584.9005307982169999.20615247647667.101169198
2170107.86230149647625.1415187362170475.53209527647617.668042207
#Sta/Elev= 30
       0 1999.33    15.7 1993.36    48.1 1975.81    68.9  1966.3    89.7 1955.18
   118.8 1943.56   127.1 1939.33   139.6 1937.81   183.4 1923.16   196.4  1917.9
   210.3 1915.79   239.4 1901.99     256 1895.03   293.4 1871.94   310.4 1864.65
   318.9  1860.1   327.5 1857.72  342.491856.814   361.8 1855.44  375.661856.814
   408.2 1858.88   429.8 1863.22   444.9 1864.85   561.6 1869.34   617.6 1875.04
   641.6 1881.83   677.6 1897.17   689.6 1899.27   765.6 1924.76     785  1930.3
#Mann= 3 ,-1,0
       0      .1       0  342.49    .045       0  375.66      .1       0
Bank Sta=342.49,375.66
XS Rating Curve= 0 ,0
Exp/Cntr=0.3,0.1

Type RM Length L Ch R = 1 ,81461   ,159.5,168,173
XS GIS Cut Line= 4
2169700.73552856647613.3826916152170011.65256672647705.041142833
2170120.30871574647663.0814923722170474.46734835647655.608015842
#Sta/Elev= 30
       0 2001.34    16.1 1993.57    25.2 1990.91    41.7 1979.67      62 1968.53
    99.5 1951.12   116.2 1945.61   124.5 1941.13   141.2 1938.74   191.2 1920.22
   207.9 1917.02   241.3 1903.66   278.8 1884.61   299.7 1868.99   339.9 1859.95
  374.051856.195   384.7 1854.38  395.331856.196   456.5 1863.61   536.6 1866.54
   584.5 1869.75   612.5 1873.06   628.5 1873.35   632.5 1874.23   648.5 1882.74
   671.5 1888.19   696.5 1898.29   708.8 1900.72   740.1 1912.59   794.9 1930.33
#Mann= 3 ,-1,0
       0      .1       0  374.05    .045       0  395.33      .1       0
Bank Sta=374.05,395.33
XS Rating Curve= 0 ,0
Exp/Cntr=0.3,0.1

Type RM Length L Ch R = 1 ,81293   ,224.4,229.5,235.3
XS GIS Cut Line= 4
2169691.48687691647668.1499689012169963.79614911 647825.89800189
 2170162.9775718647859.0683801522170460.42776079647872.310667492
#Sta/Elev= 30
       0 1995.81    74.8 1956.66    89.1 1952.12   105.8 1944.42   111.7  1940.4
     130  1937.7   171.8 1921.19   209.1 1912.17   233.5 1903.95   267.6 1883.96
   287.4 1881.16   296.6    1875   301.3 1873.39   339.4 1869.06   343.5 1867.81
   356.1 1860.48   371.9 1854.53   425.6 1854.23   440.8  1852.6  455.261854.253
   505.6 1861.18   521.8 1861.18   541.8 1858.54   554.3 1861.57   581.9 1861.85
   625.9 1872.18     650 1873.49     666 1882.74     706 1897.82   814.4 1932.67
#Mann= 3 ,-1,0
       0      .1       0   425.6    .045       0  455.26      .1       0
Bank Sta=425.6,455.26
XS Rating Curve= 0 ,0
Exp/Cntr=0.3,0.1

Type RM Length L Ch R = 1 ,81064   ,553.4,552.6,547.6
XS GIS Cut Line= 4
     2169612.518      647830.6212169988.06050952648036.730317251
2170077.85725644  648103.62039732170219.20334137648246.587357217
#Sta/Elev= 30
       0 1968.42    22.4 1958.02      34 1949.31    49.8 1945.87    66.4 1935.17
   104.6 1919.98   119.5 1910.23   146.7 1907.62   196.5 1883.77   238.1 1868.84
   259.7  1866.7   287.4 1859.22   304.6    1857   341.8 1856.21   355.1 1857.81
   369.2  1857.3     392 1860.19     424 1857.76  465.611849.946     476 1848.25
   487.51849.945   529.6 1858.02   553.8 1857.75   593.2 1859.76     610 1863.39
   660.7 1869.08   690.2 1868.42     710  1875.5   733.8 1881.03   741.4 1880.99
#Mann= 3 ,-1,0
       0      .1       0  465.61    .045       0   487.5      .1       0
Bank Sta=465.61,487.5
XS Rating Curve= 0 ,0
Exp/Cntr=0.3,0.1

Type RM Length L Ch R = 1 ,80511   ,585.1,595.5,594.5
XS GIS Cut Line= 4
2169495.85408124648248.2303883162169556.32643534648315.745627643
2169888.04748161648470.9629098972170130.91892196648461.916182097
#Sta/Elev= 30
       0  1881.2    18.5 1874.89    90.4 1855.39   108.1 1849.99     117 1846.34
   125.8 1845.16   130.2 1843.21   139.7 1836.45   145.4 1834.24   156.7 1832.47
   163.8 1832.88  169.01 1834.22   178.8 1836.07   200.9 1835.88   209.7 1836.68
     221 1835.14   249.5 1836.73   275.1 1834.44   289.2 1834.27   329.3 1836.53
   394.4 1838.39     501 1838.12   509.2 1838.93   538.3 1846.25   569.1 1851.84
   589.1 1851.08   653.1 1852.35   657.1  1852.8   665.1 1855.98   699.9 1859.54
#Mann= 8 ,-1,0
       0      .1       0      60     .08       0   145.4    .045       0
  169.01     .08       0  170.64      .1       0  260.64     .08       0
  586.88      .1       0  686.88     .08       0
Bank Sta=145.4,169.01
XS Rating Curve= 0 ,0
Exp/Cntr=0.3,0.1

Type RM Length L Ch R = 1 ,79916   ,321.9,318.7,292
XS GIS Cut Line= 3
2169206.72148351648565.9536827492169526.08827728648883.554604708
2169798.89107107649023.075135155
#Sta/Elev= 30
       0 1869.31    86.7 1850.55   102.3 1844.54   109.2 1842.91   137.4 1839.03
   208.8 1832.17   218.3 1829.04   223.9 1828.48   240.9 1830.97   263.5 1831.49
   282.5 1830.24   289.8 1831.05  298.541829.482   306.7 1828.65   320.1 1829.49
   334.9  1831.9   399.3 1830.47   418.7  1833.4   452.7 1835.37     474 1835.46
   524.3 1841.46   547.1 1845.52   565.1 1847.64   594.5 1853.12   682.4 1862.21
   699.9 1863.31   704.3 1864.49   708.8 1867.51   729.6 1877.02   756.8 1887.08
#Mann= 4 ,-1,0
       0     .08       0     180      .1       0  298.54    .045       0
   320.1      .1       0
Bank Sta=298.54,320.1
XS Rating Curve= 0 ,0
Exp/Cntr=0.3,0.1

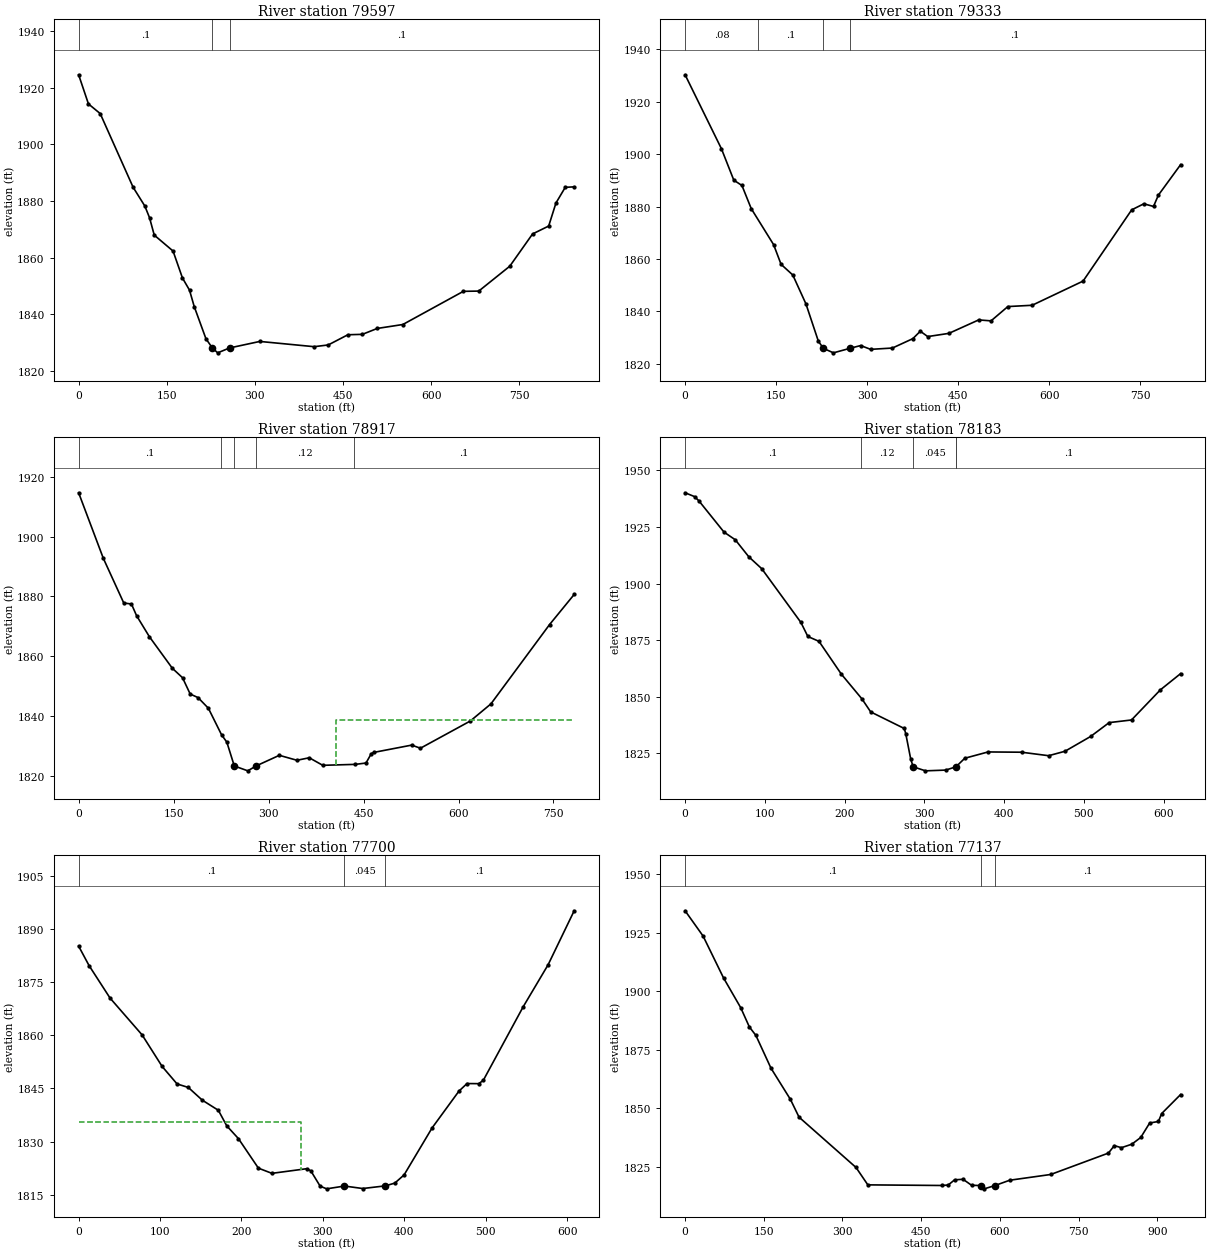
Type RM Length L Ch R = 1 ,79597   ,264.6,264.1,256.4
XS GIS Cut Line= 4
2168975.46945213648959.3850790292169437.65398488648950.609423344
2169491.77052827648998.8755296122169790.14282156649077.856430777
#Sta/Elev= 30
       0 1924.52    16.7 1914.24    36.7 1910.84    92.7 1884.86   112.7 1878.22
   120.7  1874.1   128.7 1867.98   160.7 1862.36   176.7 1852.86   188.7 1848.58
   196.7  1842.8   216.7 1831.42  227.68 1828.16   236.7 1826.46   256.8 1828.18
   308.4 1830.48   400.8 1828.63   424.8 1829.24   458.3 1832.84   482.9 1832.98
   508.2 1835.06   551.8 1836.45   654.8 1848.15     681 1848.24   733.8 1857.01
   772.6 1868.39     800 1871.17   812.4  1879.3   828.2 1884.83   843.4    1885
#Mann= 3 ,-1,0
       0      .1       0  227.68    .045       0   256.8      .1       0
Bank Sta=227.68,256.8
XS Rating Curve= 0 ,0
Exp/Cntr(USF)=0,0
Exp/Cntr=0.3,0.1

Type RM Length L Ch R = 1 ,79333   ,414.7,416,412.1
XS GIS Cut Line= 3
2169017.75144354649262.5868959452169402.49039849649176.792154192
2169824.81230838 649192.12920622
#Sta/Elev= 30
       0 1930.21    59.9 1902.01    80.3 1890.03    93.7 1888.01     109  1879.2
   145.9 1865.46   158.2 1857.96   177.5 1853.89   199.2 1842.87   219.7 1828.63
   228.1 1825.91   244.5 1824.22  271.771825.942   289.4    1827   305.8 1825.55
   341.7 1826.05   375.4 1829.63   387.7 1832.46   399.9 1830.42   434.8 1831.64
   483.9 1836.77   504.3 1836.41     532 1841.86     572 1842.35     656 1851.57
   736.1 1878.72   756.1 1881.03   772.1 1880.02   780.1 1884.33   816.8 1895.96
#Mann= 4 ,-1,0
       0     .08       0     120      .1       0   228.1    .045       0
  271.77      .1       0
Bank Sta=228.1,271.77
XS Rating Curve= 0 ,0
Exp/Cntr=0.3,0.1

Type RM Length L Ch R = 1 ,78917   ,691.3,734,735.5
XS GIS Cut Line= 4
2169109.49430141649597.8148959452169292.85879256649622.274912623
2169607.13989405649536.001424501 2169841.6644245649398.634843917
#Sta/Elev= 30
       0 1914.75      39 1892.79    71.3 1877.81    83.4 1877.49    91.5 1873.58
   111.7 1866.54     148 1855.95   164.1 1852.78   176.2 1847.32   188.6 1846.12
   204.9 1842.56   225.8 1833.64   234.1 1831.19  245.861823.212   267.2 1821.58
  280.21 1823.21     317 1826.78   344.8 1825.12   364.3 1825.96   385.6 1823.43
   437.3 1823.75   453.9  1824.2   462.2 1827.32   466.3 1827.76     526  1830.2
   539.9 1829.16   618.7 1838.28   651.2 1844.01   743.9 1870.61   782.7 1880.68
#Mann= 5 ,-1,0
       0      .1       0  224.99     .12       0  245.86    .045       0
  280.21     .12       0  434.99      .1       0
#XS Ineff= 2 , 0
                          406.68         1838.48
Permanent Ineff=
       F       F
Bank Sta=245.86,280.21
XS Rating Curve= 0 ,0
Exp/Cntr=0.3,0.1

Type RM Length L Ch R = 1 ,78183   ,478.3,482.9,489.2
XS GIS Cut Line= 3
2168971.03513516649693.6896446732169280.16814402649957.113921959
2169389.94742828650142.147800756
#Sta/Elev= 30
       0 1940.07    11.8 1938.39    17.3 1936.51    48.8 1922.71    62.9 1919.33
    79.9  1911.8    96.1 1906.56   145.2 1882.84   153.9 1876.64   167.9 1874.49
   195.9 1860.02   221.8 1849.06   232.7 1843.35   274.8 1836.03   276.7 1833.68
   282.9 1822.49  285.961819.123   301.4 1817.34   326.8 1817.67  339.561819.121
   350.7  1822.9   379.9 1825.68   421.8 1825.56   455.8 1824.02   476.3 1825.98
   508.4  1832.5   531.7 1838.63   559.7 1839.79   595.9 1853.09   621.3 1860.26
#Mann= 5 ,-1,0
       0      .1       0     220     .12       0  285.96    .045       0
  339.56     .12       0     340      .1       0
Bank Sta=285.96,339.56
XS Rating Curve= 0 ,0
Exp/Cntr=0.3,0.1

Type RM Length L Ch R = 1 ,77700   ,546.4,563,558.9
XS GIS Cut Line= 3
2168765.58131431649969.8674299562169046.34431431650360.442429956
2169144.26947548650442.208955318
#Sta/Elev= 30
       0 1885.13    12.8 1879.65    38.6 1870.48      78 1860.09   102.6 1851.19
   120.9 1846.27   134.7 1845.28   151.9 1841.69   171.6 1838.84   181.9 1834.46
   196.3 1830.84   220.8 1822.52   237.4 1821.06   279.9 1822.36   285.1 1821.79
   296.6 1817.45   304.6 1816.69   326.5 1817.48   348.9 1816.78   376.8 1817.53
   388.3 1818.31   399.7 1820.61   434.1 1833.87   467.1 1844.25     477 1846.38
   491.4 1846.35     497 1847.29   545.9    1868   576.6 1879.88   608.6  1895.1
#Mann= 3 ,-1,0
       0      .1       0   326.5    .045       0   376.8      .1       0
#XS Ineff= 2 , 0
          272.75 1835.65
Permanent Ineff=
       F       F
Bank Sta=326.5,376.8
XS Rating Curve= 0 ,0
Exp/Cntr=0.3,0.1

Type RM Length L Ch R = 1 ,77137   ,296,291.8,272.5
XS GIS Cut Line= 4
2168562.35846846649742.0120343162168486.45920483650058.353836761
2168528.21965464650380.5350056362168738.51061916650586.450139254
#Sta/Elev= 30
       0 1934.33    34.3 1923.52    73.2 1905.65   106.1 1892.86   122.5 1884.66
   134.9 1881.06   163.7 1867.03   200.7 1853.71   217.2 1846.09   325.8 1824.58
   348.3 1817.15   490.1 1816.88   501.6 1817.09   513.7 1819.31   529.8 1819.53
     546 1816.98  563.38 1816.85   570.2 1815.45   590.3 1816.84   618.7 1819.13
   696.9 1821.59   806.9 1830.74   818.1 1833.92   831.6 1833.04   851.4 1834.53
   868.5 1837.42   885.5  1843.6   902.1 1844.25   908.4 1847.65   944.5 1855.78
#Mann= 3 ,-1,0
       0      .1       0  563.38    .045       0   590.3      .1       0
Bank Sta=563.38,590.3
XS Rating Curve= 0 ,0
Exp/Cntr=0.3,0.1

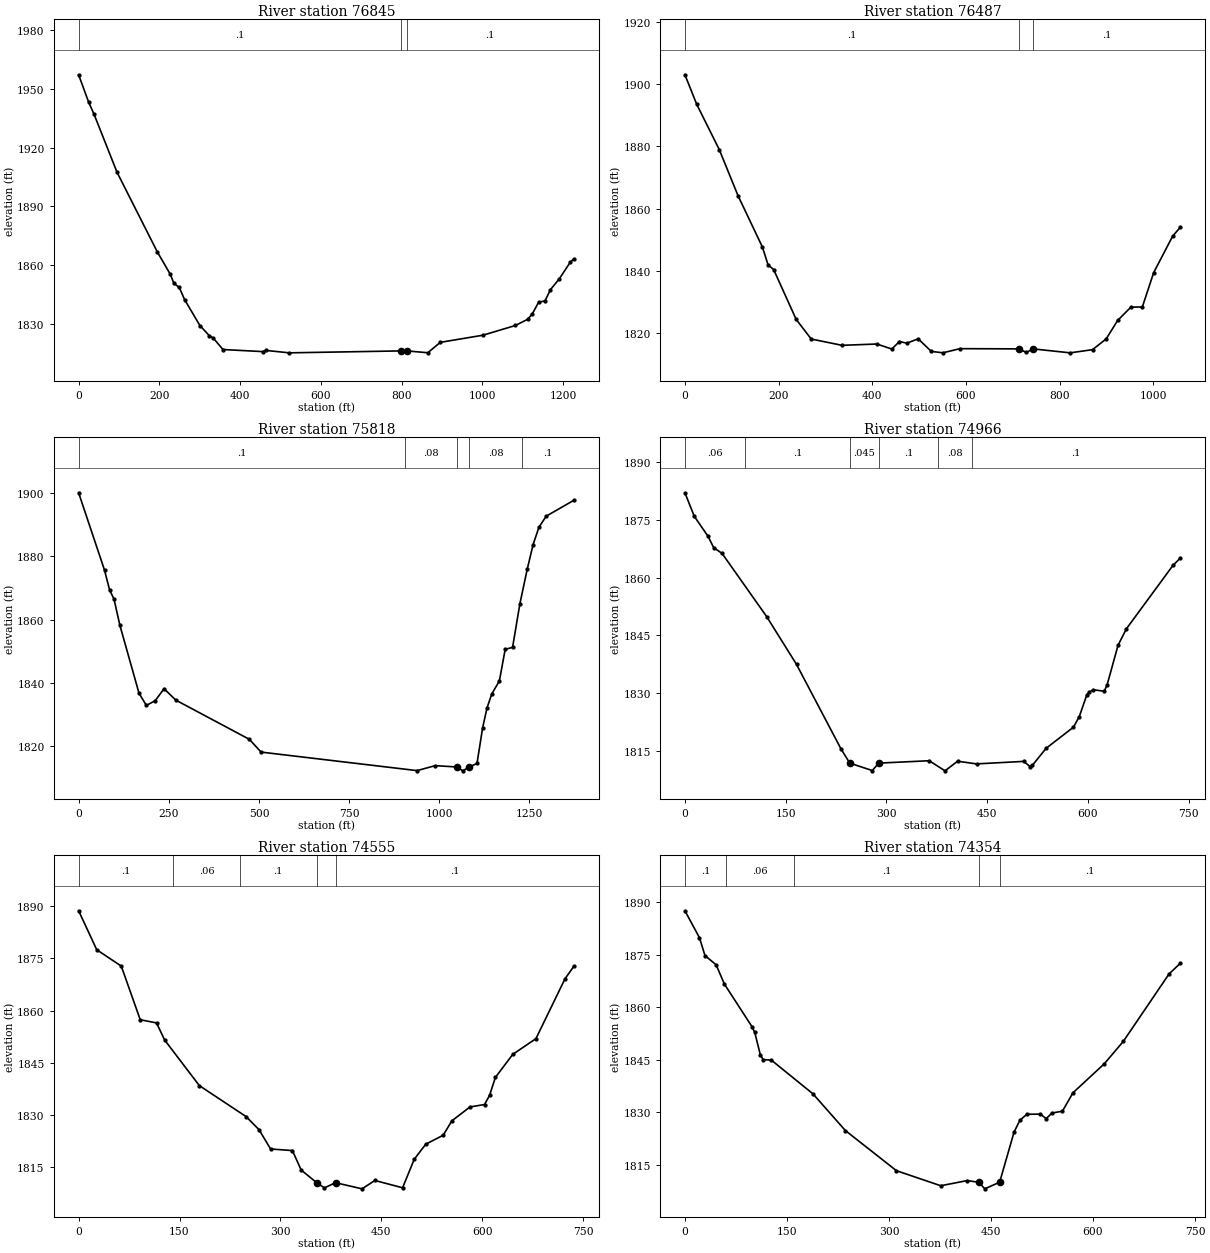
Type RM Length L Ch R = 1 ,76845   ,342.2,357.7,348.2
XS GIS Cut Line= 2
2167625.48108592650117.771629454 2168741.4519672650628.222268467
#Sta/Elev= 30
       0 1957.23      25 1943.14    38.2 1937.08    95.1 1907.44   194.7 1866.83
   227.3 1855.21   236.1 1850.62   249.3  1848.6   262.5 1842.36   300.4 1829.13
   324.1 1823.86   332.9 1822.84   357.7 1816.86     456  1815.8   464.8 1816.39
     522 1815.17   799.1 1816.16   812.3 1816.18   865.1 1815.22   895.9 1820.53
  1001.4 1824.17  1082.1 1829.15  1112.2  1832.3  1123.7    1835  1139.4 1840.99
  1155.4 1841.72  1168.6 1847.38    1191 1853.06  1217.9 1861.45  1227.2 1863.17
#Mann= 3 ,-1,0
       0      .1       0   799.1    .045       0   812.3      .1       0
Bank Sta=799.1,812.3
XS Rating Curve= 0 ,0
Exp/Cntr(USF)=0,0
Exp/Cntr=0.3,0.1

Type RM Length L Ch R = 1 ,76487   ,665,669.6,648.6
XS GIS Cut Line= 3
2167642.95796811650638.5856560352168129.42754039650663.232770939
2168692.21322683 650756.76757079
#Sta/Elev= 30
       0 1902.93    25.2 1893.45    73.3 1878.95   113.4 1864.15   165.4  1847.7
   177.4 1842.02   189.5 1840.45   237.5  1824.5   269.6 1818.21   335.3 1816.19
   409.7 1816.61   441.8    1815   457.8 1817.41   473.8 1816.88     498 1818.27
   525.9 1814.25   550.7 1813.79   587.2 1815.12   712.9 1815.05   729.1 1813.89
   742.9 1815.05   822.4 1813.78   870.2  1814.8   899.4 1818.26   923.7 1824.15
   952.1 1828.44   976.5 1828.48  1000.8 1839.53  1041.3 1851.21  1057.6 1854.04
#Mann= 3 ,-1,0
       0      .1       0   712.9    .045       0   742.9      .1       0
Bank Sta=712.9,742.9
XS Rating Curve= 0 ,0
Exp/Cntr=0.3,0.1

Type RM Length L Ch R = 1 ,75818   ,826.3,851.7,828.1
XS GIS Cut Line= 4
2167400.06882205651545.3898302552167855.33050928651452.094340744
2168468.07702891651144.7343417282168687.89731282651105.369599702
#Sta/Elev= 30
       0 1900.09    71.8 1875.65    85.9 1869.39    98.1 1866.51   114.4 1858.22
   167.5 1836.76   187.9 1832.92   212.4 1834.43   236.9 1838.19   269.6 1834.59
   473.5 1822.21   505.9 1818.18   938.4 1812.33   988.7  1813.9  1048.7 1813.48
  1065.3 1812.26 1082.171813.424  1104.6 1814.59  1120.2 1825.84  1132.4 1832.16
  1145.9 1836.64  1166.6 1840.64  1182.8 1850.66  1203.2 1851.24  1223.5 1865.03
  1243.8 1875.92  1260.2 1883.74  1276.3  1889.2  1296.6 1892.71  1373.6 1897.75
#Mann= 5 ,-1,0
       0      .1       0  904.72     .08       0  1048.7    .045       0
 1082.17     .08       0 1230.24      .1       0
Bank Sta=1048.7,1082.17
XS Rating Curve= 0 ,0
Exp/Cntr=0.3,0.1

Type RM Length L Ch R = 1 ,74966   ,412.8,410.5,403.7
XS GIS Cut Line= 4
2168500.89671833652114.5301796692168554.83816428651914.687723663
2168764.45333582651573.5685722812168795.31790363651447.150604406
#Sta/Elev= 30
       0 1881.95    13.8 1875.89    34.5 1870.64    42.8 1867.73    55.3 1866.24
   121.6 1849.89   166.1 1837.49   232.2 1815.64  245.351811.919   278.9 1809.98
   288.6 1811.91   363.7 1812.53   387.2 1809.91   405.9  1812.4   434.1 1811.71
   504.5 1812.36   513.9 1810.98   517.3 1811.35   537.7 1815.75   578.4 1821.22
   587.1 1823.97   598.4 1829.64   601.6 1830.29   607.8 1830.92   624.2 1830.53
   628.4 1832.11   644.8 1842.45   657.3 1846.73   726.6 1863.15   737.5 1865.03
#Mann= 6 ,-1,0
       0     .06       0      90      .1       0  245.35    .045       0
   288.6      .1       0  376.99     .08       0  426.99      .1       0
Bank Sta=245.35,288.6
XS Rating Curve= 0 ,0
Exp/Cntr=0.3,0.1

Type RM Length L Ch R = 1 ,74555   ,193.4,201.3,190.5
XS GIS Cut Line= 3
2168908.98337945      652255.9572168951.04538643651945.405940996
2169108.70612818651552.692450515
#Sta/Elev= 30
       0 1888.64      27 1877.44    63.4 1872.77    91.6 1857.37   115.8 1856.46
   127.9 1851.55   179.5 1838.46     249 1829.58   268.4 1825.78   285.4 1820.28
   317.9 1819.82   330.9 1814.24  353.77 1810.64   365.4 1809.12   382.1  1810.6
   421.4 1808.84   440.5 1811.24   481.7 1809.14     499 1817.32   516.2 1821.66
   542.1 1824.23     555 1828.36     582 1832.35   603.5 1833.03     611 1835.65
   619.7 1840.82   645.5 1847.43     680 1851.95   723.1 1869.09   736.6 1872.78
#Mann= 5 ,-1,0
       0      .1       0     140     .06       0     240      .1       0
  353.77    .045       0   382.1      .1       0
Bank Sta=353.77,382.1
XS Rating Curve= 0 ,0
Exp/Cntr=0.3,0.1

Type RM Length L Ch R = 1 ,74354   ,47.2,51.1,55.7
XS GIS Cut Line= 3
2169031.18462556652282.2518295422169080.99490367652006.203229523
2169245.74940706651589.852595993
#Sta/Elev= 30
       0  1887.5    21.4 1879.81    29.5 1874.72    45.8 1872.11      58 1866.61
    98.6 1854.45   102.7  1852.8   110.8 1846.47   114.9 1845.08   127.1 1844.91
   188.1 1835.33   235.9 1824.84   310.9  1813.4   376.1  1809.1     415 1810.58
   432.2 1810.08   440.8 1808.22  462.69 1810.11   483.8 1824.36   492.4 1827.75
   502.6 1829.48   522.5 1829.52   531.1 1828.24   539.6 1829.83     555 1830.37
   570.4 1835.59   616.6 1843.89   644.4 1850.24   711.8  1869.5   728.3 1872.54
#Mann= 5 ,-1,0
       0      .1       0      60     .06       0     160      .1       0
   432.2    .045       0  462.69      .1       0
Bank Sta=432.2,462.69
XS Rating Curve= 0 ,0
Exp/Cntr(USF)=0,0
Exp/Cntr=0.3,0.1

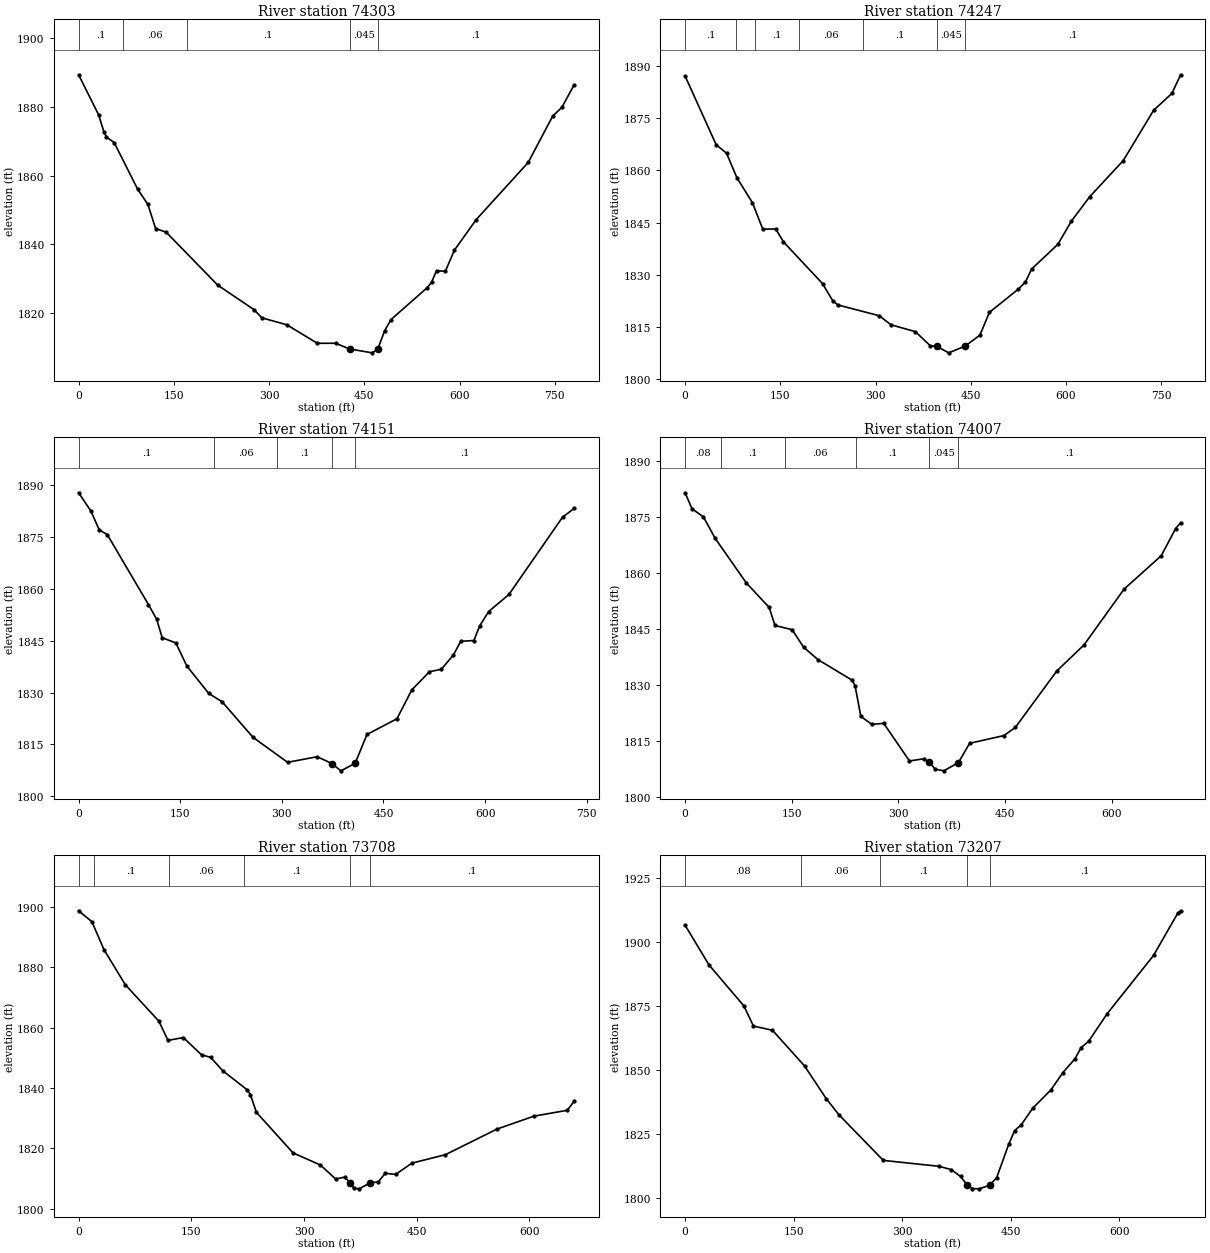
Type RM Length L Ch R = 1 ,74303   ,54.9,55.8,54.8
XS GIS Cut Line= 3
2169050.91705203652292.174419416 2169111.7536066651987.248192268
2169373.20585089651597.092102165
#Sta/Elev= 30
       0 1889.36    31.6 1877.66    39.8 1872.76    43.8 1871.26    56.1  1869.6
    92.8 1856.12   109.1 1851.62   121.3 1844.59   137.7 1843.58   219.2 1828.13
   276.3    1821   288.6 1818.63   327.9 1816.61     376 1811.22   404.9 1811.23
   426.7 1809.56   462.6 1808.44   471.3 1809.56     482 1814.84   492.1 1818.13
   549.4 1827.45     556 1829.02   563.8 1832.35   577.6 1832.15   591.9 1838.31
   626.4 1847.24   708.3 1863.87   746.8 1877.35   761.2 1879.85   780.6 1886.47
#Mann= 5 ,-1,0
       0      .1       0      70     .06       0     170      .1       0
   426.7    .045       0   471.3      .1       0
Bank Sta=426.7,471.3
XS Rating Curve= 0 ,0
Exp/Cntr=0.3,0.1

Type RM Length L Ch R = 1 ,74247   ,100.2,96.1,90.5
XS GIS Cut Line= 3
2169109.57219061652301.1985911532169170.40874519651996.272364004
2169431.86098948651606.116273901
#Sta/Elev= 30
       0 1887.12      49 1867.36    65.3 1864.95    81.6 1857.91   106.1 1850.73
   122.4 1843.14   142.8  1843.2     155 1839.48   216.5 1827.51   232.5 1822.61
   240.7 1821.38   305.9 1818.28   324.3 1815.69   362.8 1813.71   386.5 1809.62
   396.5 1809.49   415.3 1807.63   441.3 1809.58   464.4  1812.7   479.4 1819.26
   524.9 1825.91   536.2 1827.99   545.8 1831.68   587.2 1838.78   608.5 1845.45
   637.3 1852.44   690.2 1862.84     738 1877.26   766.8 1882.12   780.6 1887.47
#Mann= 7 ,-1,0
       0      .1       0      80     .06       0     110      .1       0
     180     .06       0     280      .1       0   396.5    .045       0
   441.3      .1       0
Bank Sta=396.5,441.3
XS Rating Curve= 0 ,0
Exp/Cntr=0.3,0.1

Type RM Length L Ch R = 1 ,74151   ,150.8,143.7,138.6
XS GIS Cut Line= 3
2169229.95322683652315.1605383612169268.12732906652054.523564516
2169455.04879515651625.394001518
#Sta/Elev= 30
       0 1887.75    18.2 1882.44    30.3 1877.08    42.4 1875.63   103.1 1855.43
   115.2 1851.19   123.3 1845.86   143.5 1844.35   159.7 1837.69     192 1829.76
   211.8 1827.34   257.6 1817.03   308.5 1809.84   352.1 1811.46     374 1809.49
     387 1807.38  408.17 1809.54   425.6 1817.89   469.9 1822.43   491.8 1830.79
   517.9 1836.03   535.4 1836.73   553.2 1840.87     564 1844.81   583.4 1845.05
   592.1 1849.31   605.2 1853.41   635.3 1858.38   714.3 1880.69   731.5 1883.22
#Mann= 5 ,-1,0
       0      .1       0     200     .06       0  293.42      .1       0
     374    .045       0  408.17      .1       0
Bank Sta=374,408.17
XS Rating Curve= 0 ,0
Exp/Cntr(USF)=0,0
Exp/Cntr=0.3,0.1

Type RM Length L Ch R = 1 ,74007   ,296.4,299.5,294.3
XS GIS Cut Line= 2
2169407.07018788652362.7674738152169485.89173026651670.092060131
#Sta/Elev= 30
       0  1881.5     9.7 1877.22    25.8 1875.04    42.2 1869.32    86.1 1857.35
   118.3 1850.77   126.4 1845.95   150.6 1844.81   166.7 1840.14   186.8 1836.81
   235.1 1831.27   239.1 1829.81   247.2 1821.59   262.7 1819.45   279.4 1819.73
   315.6 1809.65   335.7 1810.23   343.8 1809.27   351.8 1807.45   363.9    1807
  384.59 1809.23   400.2 1814.37   448.5 1816.45   464.6 1818.64   522.9 1833.76
   561.2 1840.74   617.5 1855.68   669.9 1864.65     690 1871.92   697.1 1873.47
#Mann= 6 ,-1,0
       0     .08       0      50      .1       0     140     .06       0
     240      .1       0   343.8    .045       0  384.59      .1       0
Bank Sta=343.8,384.59
XS Rating Curve= 0 ,0
Exp/Cntr(USF)=0,0
Exp/Cntr=0.3,0.1

Type RM Length L Ch R = 1 ,73708   ,495.5,501.1,499.4
XS GIS Cut Line= 2
2169658.29724748652334.4783631752169769.44356769 651684.19125595
#Sta/Elev= 30
       0 1898.69    17.6  1895.1    33.8 1885.78    62.2 1874.16   106.8 1862.11
     119 1855.73   139.3 1856.68   163.6 1850.96   175.8  1850.1     192 1845.64
   224.6 1839.32   228.6 1837.79   236.7 1831.89   285.4 1818.46   321.9 1814.43
   342.2 1809.79   354.4 1810.44  361.15 1808.54   366.5 1806.72   373.6 1806.54
   387.4 1808.45     399 1808.88   408.2 1811.69   422.1 1811.32   443.6 1815.05
   488.3 1817.86   557.2 1826.37     606 1830.62   650.3 1832.56   659.7 1835.52
#Mann= 6 ,-1,0
       0     .08       0      20      .1       0     120     .06       0
     220      .1       0  361.15    .045       0   387.4      .1       0
Bank Sta=361.15,387.4
XS Rating Curve= 0 ,0
Exp/Cntr=0.3,0.1

Type RM Length L Ch R = 1 ,73207   ,289.8,296.6,303
XS GIS Cut Line= 3
     2170016.177652367.3561579232170145.52600649652079.040131424
2170250.34727961651725.249851813
#Sta/Elev= 30
       0 1906.61    33.1 1891.09    81.3 1875.11    94.5 1867.27   120.8 1865.62
   165.1 1851.71   195.3 1838.87   212.8  1832.6     274 1814.84   351.3 1812.54
   367.9 1811.24   380.8 1808.59   390.31805.135   397.2 1803.87   406.5 1803.75
  420.841805.137   430.6 1808.03   447.3 1821.11   455.6 1826.49   464.5 1828.69
   480.5 1835.19   505.7 1842.36   522.3 1849.13   539.1 1854.56   547.4 1858.86
   557.8 1861.33   583.5 1872.11   647.5 1894.81   680.9 1911.24     685 1912.25
#Mann= 5 ,-1,0
       0     .08       0     160     .06       0     270      .1       0
   390.3    .045       0  420.84      .1       0
Bank Sta=390.3,420.84
XS Rating Curve= 0 ,0
Exp/Cntr=0.3,0.1

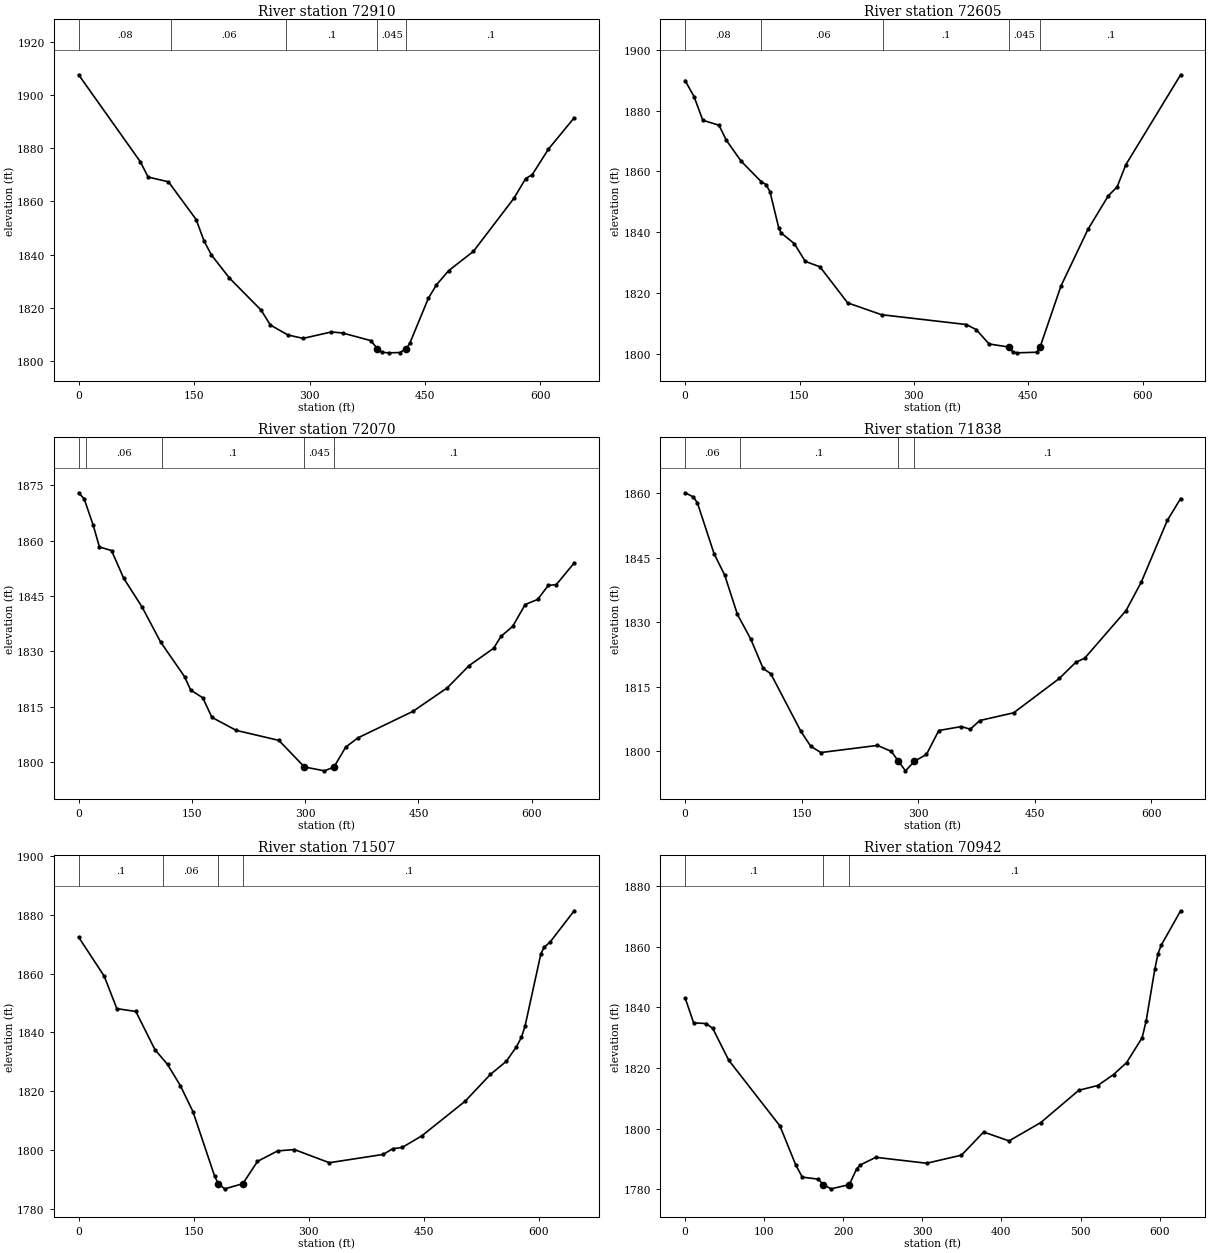
Type RM Length L Ch R = 1 ,72910   ,304.7,305.5,302.8
XS GIS Cut Line= 2
2170139.54993858652459.9588571642170562.09775982651974.226314998
#Sta/Elev= 30
       0  1907.6    80.2  1874.9    90.3 1869.16   116.7 1867.37   152.7 1853.19
   162.7 1845.29   172.5 1839.88     196 1831.17     237 1819.17   249.1 1813.54
   271.8 1809.82   291.6 1808.52   328.5 1810.95     343 1810.54   379.5 1807.69
   388.11804.693   393.7  1803.3   403.2 1803.09   417.2  1803.2  425.94  1804.7
   430.5 1806.86   454.3 1823.56   464.9 1828.65   480.8 1833.99   512.9 1841.23
   565.7 1861.25   580.8 1868.61   589.3 1870.05   610.4 1879.67   643.8 1891.43
#Mann= 5 ,-1,0
       0     .08       0     120     .06       0     270      .1       0
   388.1    .045       0  425.94      .1       0
Bank Sta=388.1,425.94
XS Rating Curve= 0 ,0
Exp/Cntr(USF)=0,0
Exp/Cntr=0.3,0.1

Type RM Length L Ch R = 1 ,72605   ,484.2,535.1,532.3
XS GIS Cut Line= 2
2170350.03719735652699.6824295872170758.91737567652194.760836941
#Sta/Elev= 30
       0 1889.86    11.8 1884.55    23.2  1876.8    44.4 1875.17    54.2 1870.18
    73.3  1863.4     100 1856.56   106.2 1855.64   111.3 1853.29   122.7  1841.5
   125.6 1839.82   143.2 1836.24   157.6 1830.39   176.8 1828.63   213.1 1816.77
   257.6 1812.87   368.7 1809.65   381.6 1807.99   398.6 1803.26   424.2 1802.25
   429.9 1800.57   435.6 1800.34   461.2 1800.54  465.41 1802.25   492.8 1822.32
   528.2 1840.94     555 1852.02   566.4 1854.86   577.8 1862.16   649.7 1891.75
#Mann= 5 ,-1,0
       0     .08       0     100     .06       0     260      .1       0
   424.2    .045       0  465.41      .1       0
Bank Sta=424.2,465.41
XS Rating Curve= 0 ,0
Exp/Cntr=0.3,0.1

Type RM Length L Ch R = 1 ,72070   ,218.6,231.6,240.8
XS GIS Cut Line= 3
2170404.90798605652767.8178769072170831.38998605652818.414876907
2171051.04756852652762.347310275
#Sta/Elev= 30
       0 1873.02     7.3 1871.39    19.4 1864.17    27.5 1858.34    43.6 1857.35
    59.7 1849.83    83.9 1842.09   108.6 1832.55   140.2 1823.19   148.4 1819.53
   164.4 1817.44   176.5 1812.13   208.7 1808.61   265.1  1805.9  299.051798.685
   325.5 1797.64  338.121798.685   353.7 1804.08   369.8 1806.57   442.7 1813.77
   488.1 1820.13     517 1826.16   549.5 1830.85   559.4 1834.11   574.8  1836.8
   591.3 1842.72   607.8  1844.1   621.9  1847.9   632.6 1848.13   656.2    1854
#Mann= 5 ,-1,0
       0      .1       0      10     .06       0     110      .1       0
  299.05    .045       0  338.12      .1       0
Bank Sta=299.05,338.12
XS Rating Curve= 0 ,0
Exp/Cntr=0.3,0.1

Type RM Length L Ch R = 1 ,71838   ,336.1,331.3,312.6
XS GIS Cut Line= 4
2170449.34310573652858.2319708542170648.73039072652935.001406786
2170713.77116283653061.8842245082170988.86164159653120.527543624
#Sta/Elev= 30
       0 1860.05    10.7 1859.08    15.9 1857.67    37.3 1845.89    50.9 1840.97
    67.3 1831.82    84.5 1826.08   100.4 1819.27   110.2 1818.06   148.8 1804.73
   161.6 1801.21   174.7 1799.76   247.5 1801.41   265.4 1800.01   274.5 1797.72
   283.5 1795.51   295.1 1797.74   310.5 1799.31   326.4 1804.87   355.4 1805.79
   366.9 1805.16   379.1 1807.19   422.7 1808.98   481.4 1816.95   502.6  1820.7
   514.1 1821.66   567.3 1832.72   586.9 1839.33   620.4 1853.65   637.5 1858.72
#Mann= 4 ,-1,0
       0     .06       0      70      .1       0   274.5    .045       0
   295.1      .1       0
Bank Sta=274.5,295.1
XS Rating Curve= 0 ,0
Exp/Cntr(USF)=0,0
Exp/Cntr=0.3,0.1

Type RM Length L Ch R = 1 ,71507   ,562.9,565,545.7
XS GIS Cut Line= 3
2170311.93158489 653185.300846562170711.17558489 653288.60784656
2170938.56006301653341.112873978
#Sta/Elev= 30
       0 1872.39    33.3 1859.16    49.8 1848.09    74.6 1847.12    99.4 1834.17
   115.9  1829.1   132.5 1821.94     149 1813.06   177.3 1791.08  182.131788.547
   190.3 1786.82  213.941788.548   233.1 1796.16   259.4 1799.72   281.2 1800.17
   326.7  1795.7   396.9 1798.52   409.3 1800.45   421.6 1800.89   447.1 1804.81
   503.8 1816.63   536.6 1825.72   557.2 1830.14   570.5 1835.09   577.1 1838.36
   581.7 1842.08   602.3 1866.62   606.4 1868.88   614.6 1870.78   645.8 1881.36
#Mann= 4 ,-1,0
       0      .1       0     110     .06       0  182.13    .045       0
  213.94      .1       0
Bank Sta=182.13,213.94
XS Rating Curve= 0 ,0
Exp/Cntr=0.3,0.1

Type RM Length L Ch R = 1 ,70942   ,426.1,419.5,398.7
XS GIS Cut Line= 3
2170253.50471758653772.4327260592170504.61135546653735.832455509
 2170876.7774911653713.484400673
#Sta/Elev= 30
       0 1843.15    10.8 1834.92      27 1834.66      35 1833.05    55.2 1822.57
   119.9 1800.92   140.1 1787.93   148.2 1784.02   168.4 1783.35  174.771781.547
   184.6 1780.16  207.651781.546     217 1786.78   221.7 1788.06   241.2 1790.56
   305.4  1788.6   349.5 1791.27   377.5  1798.9   409.6 1795.97   449.7 1802.01
   497.8 1812.66   521.8 1814.24   541.8 1817.87   558.3  1821.8   577.9 1829.98
     583 1835.56   593.9 1852.52   597.9 1857.64   601.9 1860.44   626.6 1871.87
#Mann= 3 ,-1,0
       0      .1       0  174.77    .045       0  207.65      .1       0
Bank Sta=174.77,207.65
XS Rating Curve= 0 ,0
Exp/Cntr=0.3,0.1