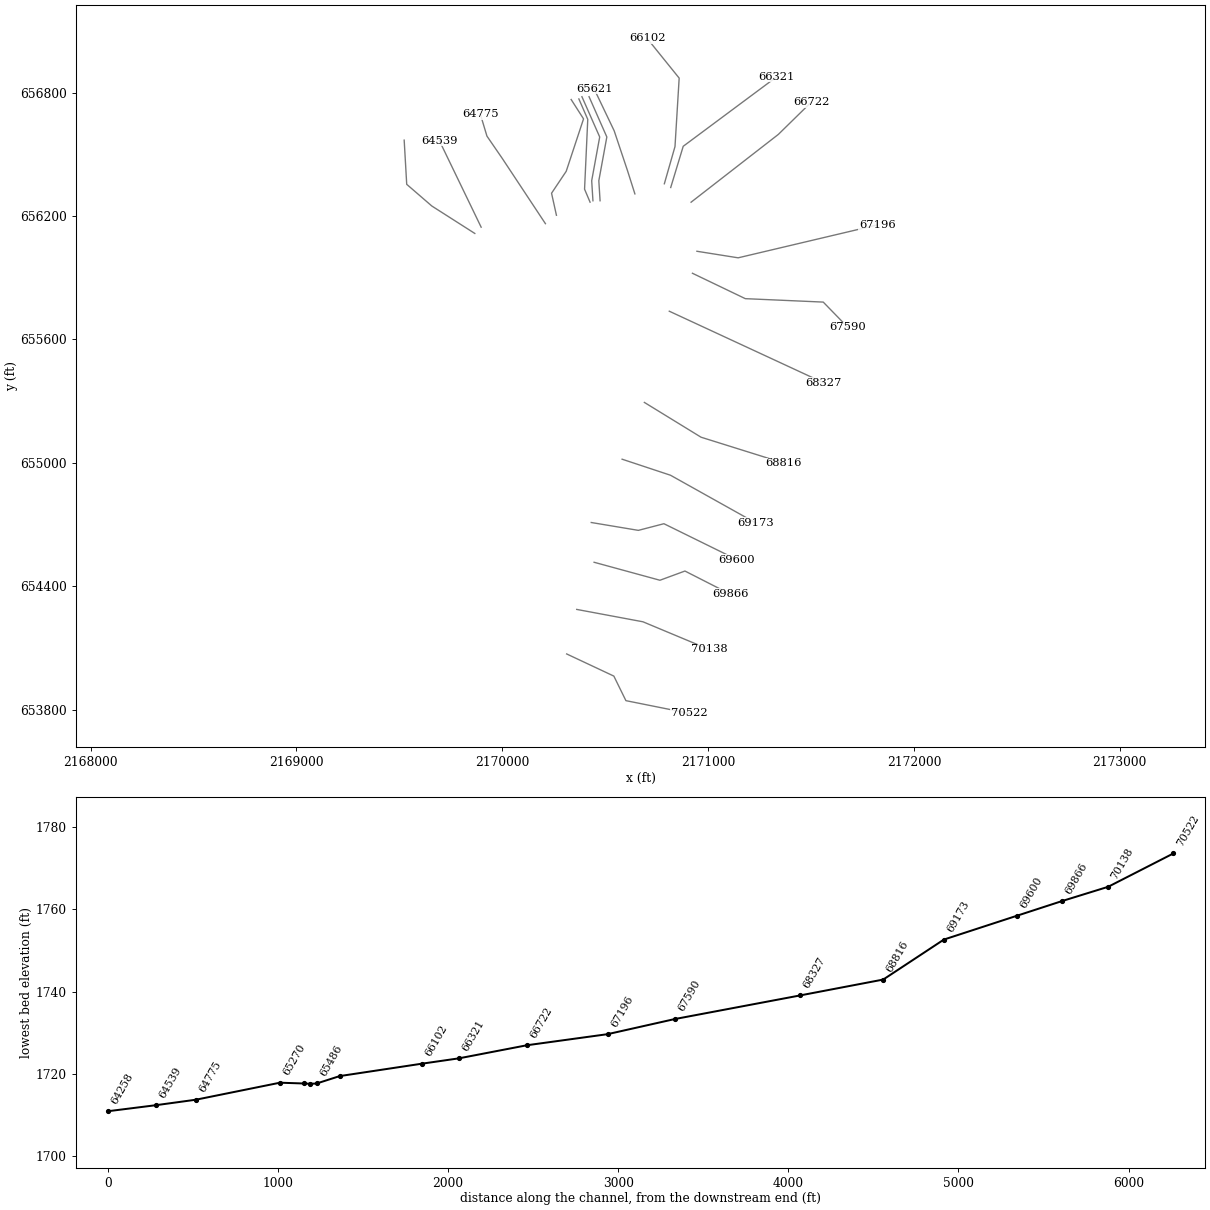
HEC-RAS study LIKANARV.prj: LIKANARV

--- LIKANARV.g01 (geometry) --- (continued)

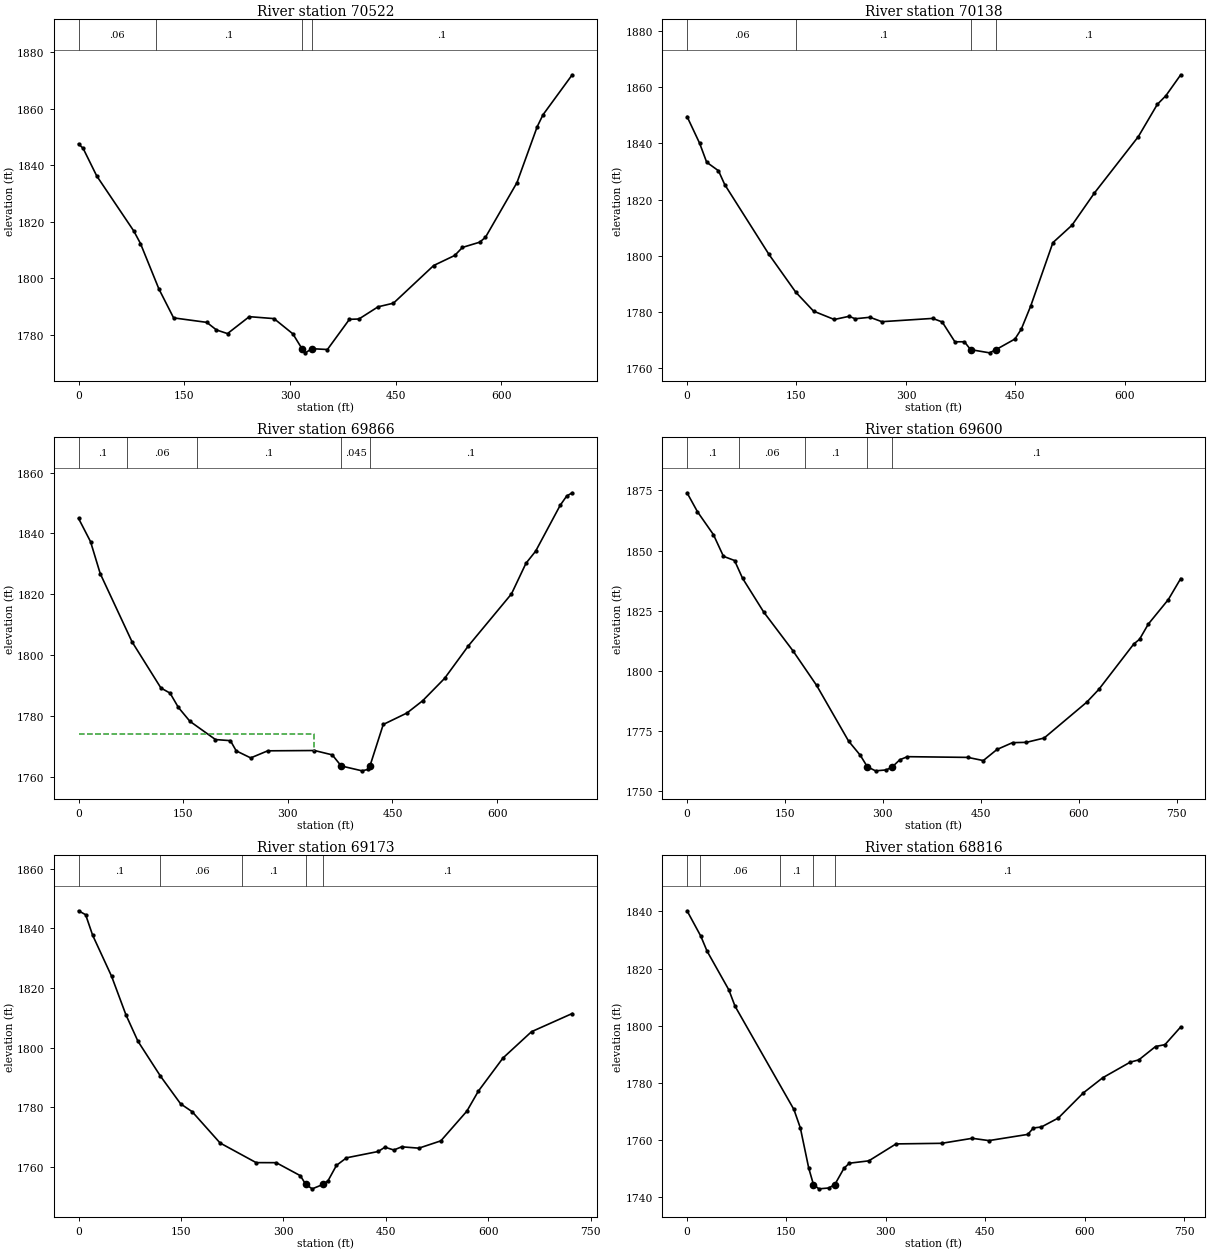
Type RM Length L Ch R = 1 ,70522   ,371,383.9,381.1
XS GIS Cut Line= 4
2170312.86410851654070.5493132912170542.10617414653962.858854552
2170600.74949326 653843.439731992170908.89347916653781.597686377
#Sta/Elev= 30
       0 1847.52     6.5 1845.94    25.8 1836.18    78.5 1816.66    87.9 1812.26
   114.1 1796.16   134.9 1785.96     182 1784.37   195.7 1781.69   211.4  1780.4
   242.3 1786.39   277.4  1785.7   304.2  1780.3  316.97  1775.1     322 1773.59
   330.9 1775.06   353.2 1774.77   384.4 1785.45   397.9 1785.56   425.1 1789.88
   446.9 1791.16     504 1804.49   533.9 1808.05   544.8 1810.89   569.3 1812.74
   577.5 1814.48   622.2 1833.83   650.9  1853.6   659.1 1857.81   700.6 1871.97
#Mann= 4 ,-1,0
       0     .06       0     110      .1       0  316.97    .045       0
   330.9      .1       0
Bank Sta=316.97,330.9
XS Rating Curve= 0 ,0
Exp/Cntr(USF)=0,0
Exp/Cntr=0.3,0.1

Type RM Length L Ch R = 1 ,70138   ,252.5,272.7,282
XS GIS Cut Line= 3
2170361.77006301654286.9989013962170683.53402742654226.849833575
2171005.77883839654092.143959596
#Sta/Elev= 30
       0 1849.53    17.3 1839.99    26.9 1833.27    43.1 1830.24    51.6 1825.34
   112.3 1800.47   148.9 1787.08   173.4  1780.3   201.8 1777.33   222.2 1778.47
   230.3 1777.59   250.7 1778.12     267 1776.55   336.7 1777.72   349.7 1776.45
   367.1 1769.39   380.1 1769.41   388.61766.617   414.6 1765.47  423.441766.617
   449.4 1770.39   458.1  1773.9   471.1  1782.2   501.4 1804.67   527.5 1810.85
   558.4 1822.36   618.5 1842.38   644.5 1853.85   656.2 1856.92   676.6 1864.38
#Mann= 4 ,-1,0
       0     .06       0     150      .1       0   388.6    .045       0
  423.44      .1       0
Bank Sta=388.6,423.44
XS Rating Curve= 0 ,0
Exp/Cntr=0.3,0.1

Type RM Length L Ch R = 1 ,69866   ,261.7,265.8,258.6
XS GIS Cut Line= 4
2170446.14437923654516.2385385672170766.01702895654428.806680977
2170887.56863584654473.5888519372171107.21452198654361.633424535
#Sta/Elev= 30
       0 1844.95    17.2 1837.31    31.1  1826.8    76.7 1804.38   118.1 1789.21
   131.2 1787.52   143.1 1782.83   159.7 1778.25   196.3 1772.26   217.7  1771.9
     226 1768.55   246.8 1766.23   271.2 1768.56   338.2 1768.66   363.7 1767.23
   376.5 1763.59   406.4 1761.98   414.9 1762.45   417.7 1763.56   436.8 1777.22
   470.8 1780.99   493.3 1785.02   524.7 1792.36   558.9 1803.08   620.6 1820.13
   641.4  1830.2   655.2 1834.16   690.5 1849.28   699.8 1852.31   707.7 1853.37
#Mann= 5 ,-1,0
       0      .1       0      70     .06       0     170      .1       0
   376.5    .045       0   417.7      .1       0
#XS Ineff= 2 , 0
          338.03 1773.94
Permanent Ineff=
       F       F
Bank Sta=376.5,417.7
XS Rating Curve= 0 ,0
Exp/Cntr(USF)=0,0
Exp/Cntr=0.3,0.1

Type RM Length L Ch R = 1 ,69600   ,439.1,427,401.8
XS GIS Cut Line= 4
2170432.35390957654709.5304410762170661.24895038654671.323421096
2170785.34116643      654703.6562171140.72006782654528.810239058
#Sta/Elev= 30
       0 1874.05      16 1866.15    40.4 1856.66    55.8 1847.62    72.8 1845.88
      85 1838.52   117.4 1824.47     162 1808.43   198.5 1793.95   247.5 1770.78
   265.5 1764.85  276.251760.081   288.8  1758.4   305.4 1758.78  314.611760.082
     326 1763.01   337.6 1764.29   430.3 1763.99   453.9 1762.67   474.9 1767.29
   498.7 1770.12   519.9 1770.25   547.1 1772.04   612.3 1786.93   630.9 1792.27
   684.4 1811.14   693.3 1813.12   706.7 1819.43   737.4 1829.64   756.4 1838.38
#Mann= 5 ,-1,0
       0      .1       0      80     .06       0     180      .1       0
  276.25    .045       0  314.61      .1       0
Bank Sta=276.25,314.61
XS Rating Curve= 0 ,0
Exp/Cntr=0.3,0.1

Type RM Length L Ch R = 1 ,69173   ,351.6,356.9,342.1
XS GIS Cut Line= 3
 2170582.2743316655017.2951402592170817.21149697654939.415363203
2171232.15435671654707.204293073
#Sta/Elev= 30
       0 1845.87    10.4 1844.55    20.6  1837.7    48.4 1823.91    69.4 1810.99
      87 1802.13     120 1790.42   149.5 1781.14   166.4 1778.51   207.3 1768.01
   260.1 1761.43   289.5 1761.41   324.8 1757.05  332.761754.131   342.2 1752.64
  358.131754.128   365.5 1755.41   377.7  1760.5   392.4 1763.04   438.8 1765.16
   448.7  1766.6   461.8 1765.66   473.2 1766.73   498.4 1766.28   530.6 1768.73
   568.7 1778.69   585.5 1785.39   621.6 1796.51   663.4 1805.33     723 1811.42
#Mann= 5 ,-1,0
       0      .1       0     120     .06       0     240      .1       0
  332.76    .045       0  358.13      .1       0
Bank Sta=332.76,358.13
XS Rating Curve= 0 ,0
Exp/Cntr=0.3,0.1

Type RM Length L Ch R = 1 ,68816   ,483.9,488.8,487.3
XS GIS Cut Line= 3
2170690.44283695655293.3411230912170965.77005712 655124.20893591
2171368.44218021654998.081665599
#Sta/Elev= 30
       0  1840.2    20.8 1831.31    30.2 1826.09    63.1 1812.52    72.4 1806.83
   161.3 1770.67     171 1764.23   183.7 1750.13   190.81744.412     199 1742.91
   213.7  1743.2  223.031744.414   236.9 1750.12   244.9 1751.88   274.3  1752.7
   315.4 1758.63   384.3 1758.84   430.4 1760.59   455.6 1759.79   514.3 1761.96
   522.7  1764.2   534.9 1764.56   560.4  1767.7   598.1 1776.48   627.4 1781.78
     669 1787.25   681.8 1788.03   707.1 1792.71   721.3 1793.36   745.1 1799.56
#Mann= 5 ,-1,0
       0      .1       0      20     .06       0     140      .1       0
   190.8    .045       0  223.03      .1       0
Bank Sta=190.8,223.03
XS Rating Curve= 0 ,0
Exp/Cntr=0.3,0.1

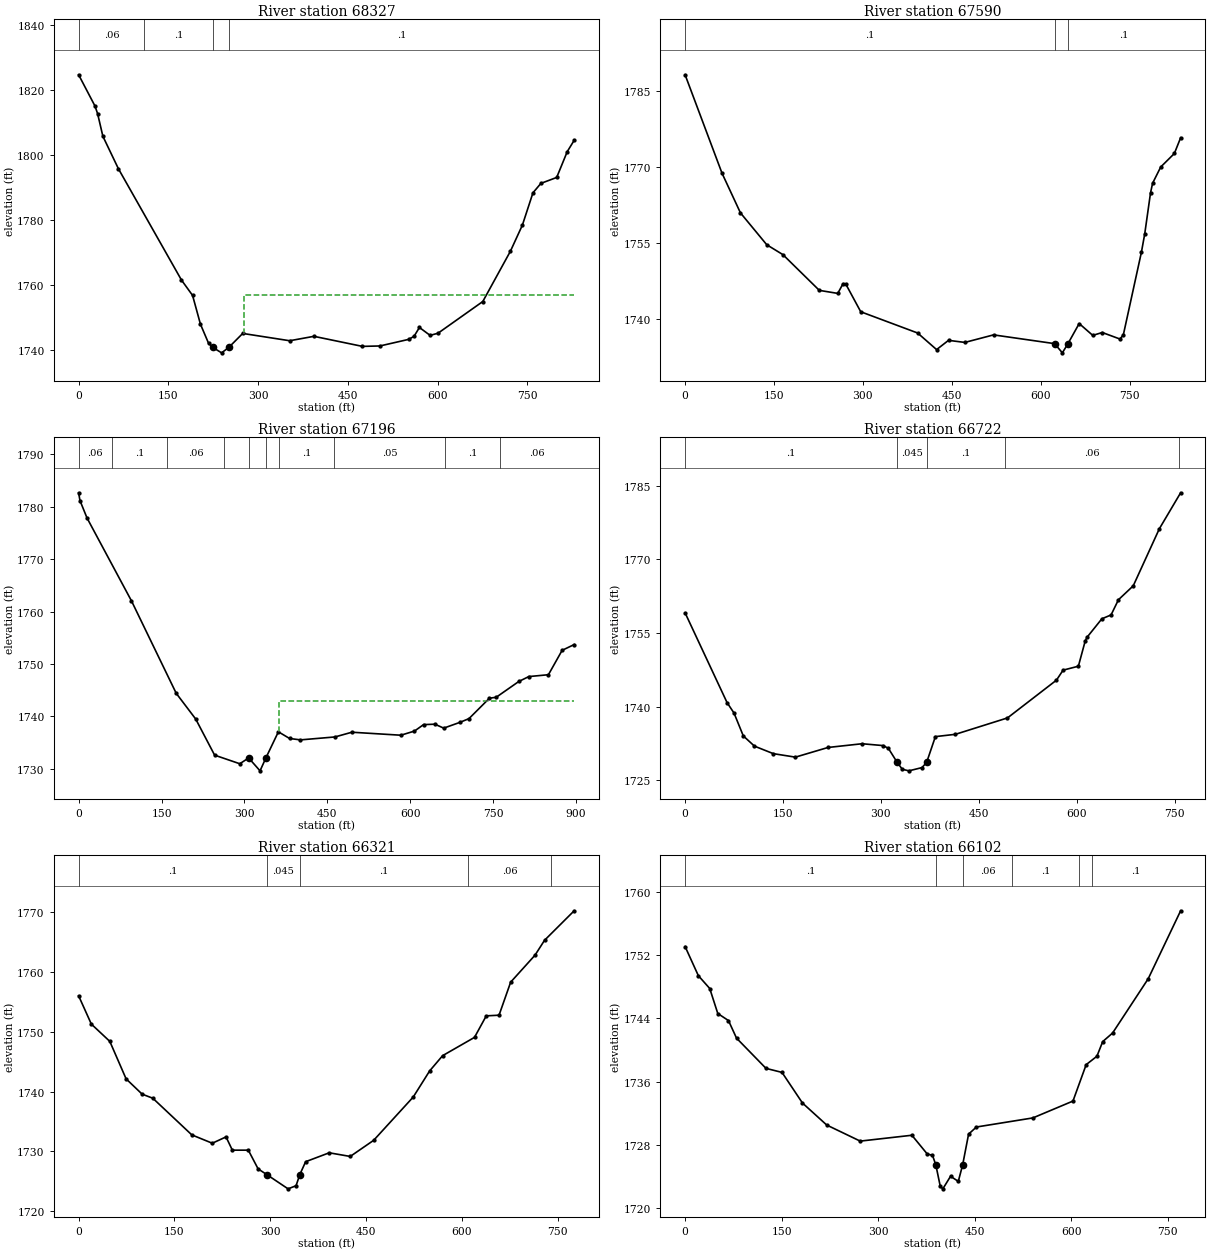
Type RM Length L Ch R = 1 ,68327   ,715.5,737.4,725.2
XS GIS Cut Line= 2
2170811.44959264655736.7822675322171562.66480346655388.293783119
#Sta/Elev= 30
       0 1824.77    27.3 1815.14    31.7 1812.79    40.5 1805.82    66.5 1795.79
   171.9 1761.47   190.4 1756.76   203.6 1747.86   217.1 1742.01   224.4  1740.7
   238.9 1739.05  250.851740.709   274.2 1745.03   352.7 1742.78   393.2 1744.14
   474.3 1741.04   503.5 1741.17   551.5  1743.2   560.5 1744.14   569.5 1746.87
   587.3 1744.44   600.5 1745.09   675.4 1754.87   721.5 1770.36   741.6 1778.44
   759.2 1788.38   772.5 1791.29   798.9 1793.12   816.5 1801.07   828.1 1804.57
#Mann= 4 ,-1,0
       0     .06       0     110      .1       0   224.4    .045       0
  250.85      .1       0
#XS Ineff= 2 , 0
                          276.78         1756.75
Permanent Ineff=
       F       F
Bank Sta=224.4,250.85
XS Rating Curve= 0 ,0
Exp/Cntr=0.3,0.1

Type RM Length L Ch R = 1 ,67590   ,388.8,394.3,389.5
XS GIS Cut Line= 4
2170923.98838606 655921.247744582171180.86725273655797.812445015
2171559.51337437655781.1319991272171679.61258476655657.696699561
#Sta/Elev= 30
       0 1788.27    62.3 1768.81    93.4 1760.97   137.8 1754.67   165.1 1752.71
   226.5 1745.65   257.6 1745.05   266.5 1746.96   270.9 1746.95   296.4 1741.42
   392.4 1737.22   424.4 1733.94   444.5 1735.77   472.1 1735.36   520.5 1736.85
   623.5 1735.12   636.6  1733.3  645.991735.099     665 1739.09   687.9 1736.75
     704 1737.32   733.8 1736.03   739.5 1736.85     770 1753.19   775.6 1756.81
   785.4 1764.94   788.9 1766.83   802.6 1770.04   825.6 1772.71   836.2 1775.82
#Mann= 3 ,-1,0
       0      .1       0   623.5    .045       0  645.99      .1       0
Bank Sta=623.5,645.99
XS Rating Curve= 0 ,0
Exp/Cntr(USF)=0,0
Exp/Cntr=0.3,0.1

Type RM Length L Ch R = 1 ,67196   ,464.2,473.5,483.6
XS GIS Cut Line= 3
2170945.77301389656028.1922019592171146.02476262655996.338558102
2171821.41929745656156.054211735
#Sta/Elev= 30
       0 1782.63     2.4 1781.15    15.2 1777.82    95.6 1762.03   176.6 1744.41
   211.9  1739.5   246.1 1732.62   291.7 1730.98   307.7 1732.09   328.3 1729.63
  339.07 1732.13   361.5 1737.07   381.7  1735.8   401.4 1735.53   463.9 1736.09
   494.5 1736.99   583.1 1736.42   607.8 1737.21   624.2 1738.44   644.8 1738.52
   660.7 1737.77     690 1738.87   706.4 1739.58   743.4 1743.47   755.8 1743.66
   796.7 1746.67   814.8  1747.6   850.2 1747.95     875  1752.6   896.8  1753.7
#Mann= 10 ,-1,0
       0     .06       0      60      .1       0     160     .06       0
  262.77     .05       0   307.7    .045       0  339.07     .05       0
  362.77      .1       0  462.77     .05       0  662.77      .1       0
  762.77     .06       0
#XS Ineff= 2 , 0
                          362.02         1742.91
Permanent Ineff=
       F       F
Bank Sta=307.7,339.07
XS Rating Curve= 0 ,0
Exp/Cntr=0.3,0.1

Type RM Length L Ch R = 1 ,66722   ,385.7,400.6,389
XS GIS Cut Line= 3
2170917.40738409656266.7473362562171341.45390187656596.438077405
2171500.02742984656752.008357939
#Sta/Elev= 30
       0 1759.12    64.3 1740.84      75  1738.7    89.2 1734.05   106.3 1731.97
   135.2 1730.44     169 1729.73     219  1731.7   271.2 1732.46   303.7 1732.08
   311.6  1731.5  325.041728.646   332.8 1727.26   342.9 1726.94   362.9  1727.6
  370.071728.646   383.5 1733.91   414.2 1734.38     494 1737.72     569 1745.41
   579.2 1747.45   602.6 1748.25   613.1  1753.4     616 1754.17   638.6 1757.91
   652.7  1758.7     664 1761.79   686.7 1764.63   726.7 1776.26   759.3 1783.58
#Mann= 5 ,-1,0
       0      .1       0  325.04    .045       0  370.07      .1       0
     490     .06       0  757.13      .1       0
Bank Sta=325.04,370.07
XS Rating Curve= 0 ,0
Exp/Cntr=0.3,0.1

Type RM Length L Ch R = 1 ,66321   ,209.7,219.3,239.9
XS GIS Cut Line= 3
2170818.40151539656338.0999916032170879.17731884 656538.55351876
2171333.39648144656876.552285296
#Sta/Elev= 30
       0 1756.04    19.9 1751.31    48.8 1748.42    74.3 1742.15    99.4 1739.59
   116.1 1738.91   177.1 1732.78   209.2 1731.38   230.7 1732.44   240.6 1730.22
   265.6 1730.22   280.9 1727.09     295  1726.1   327.8 1723.75   340.3 1724.27
  346.07 1726.11   355.3 1728.29   392.2 1729.78   425.1 1729.17   461.8 1731.87
   523.7 1739.11   549.4 1743.48   569.7 1746.03   619.6 1749.09     638 1752.69
     658  1752.8   676.2 1758.33   714.3 1762.84   729.2 1765.33   775.6 1770.27
#Mann= 5 ,-1,0
       0      .1       0     295    .045       0  346.07      .1       0
  609.46     .06       0  739.46      .1       0
Bank Sta=295,346.07
XS Rating Curve= 0 ,0
Exp/Cntr(USF)=0,0
Exp/Cntr=0.3,0.1

Type RM Length L Ch R = 1 ,66102   ,467.2,480.7,476.4
XS GIS Cut Line= 4
2170787.48879066656356.3582772132170839.23620143656537.263361597
2170859.51167104656870.0329131512170703.55386537657063.396369695
#Sta/Elev= 30
       0 1753.05    20.6 1749.37    38.3 1747.75    50.8 1744.59    67.4  1743.7
    79.9 1741.48   125.7 1737.66   150.6 1737.15   182.4 1733.28   220.1  1730.5
   272.1 1728.47   352.4 1729.21   376.4 1726.83   384.4 1726.68  389.581725.469
   396.5 1722.76   400.5 1722.44   412.5 1724.03   424.5 1723.38  431.271725.465
   440.5 1729.35   452.6 1730.25   540.4  1731.4   602.7 1733.53   623.2 1738.13
   639.9 1739.19   648.9 1741.04   664.3 1742.13   719.6 1748.98     770 1757.57
#Mann= 6 ,-1,0
       0      .1       0  389.58    .045       0  431.27     .06       0
  508.16      .1       0  611.55     .05       0  631.55      .1       0
Bank Sta=389.58,431.27
XS Rating Curve= 0 ,0
Exp/Cntr=0.3,0.1

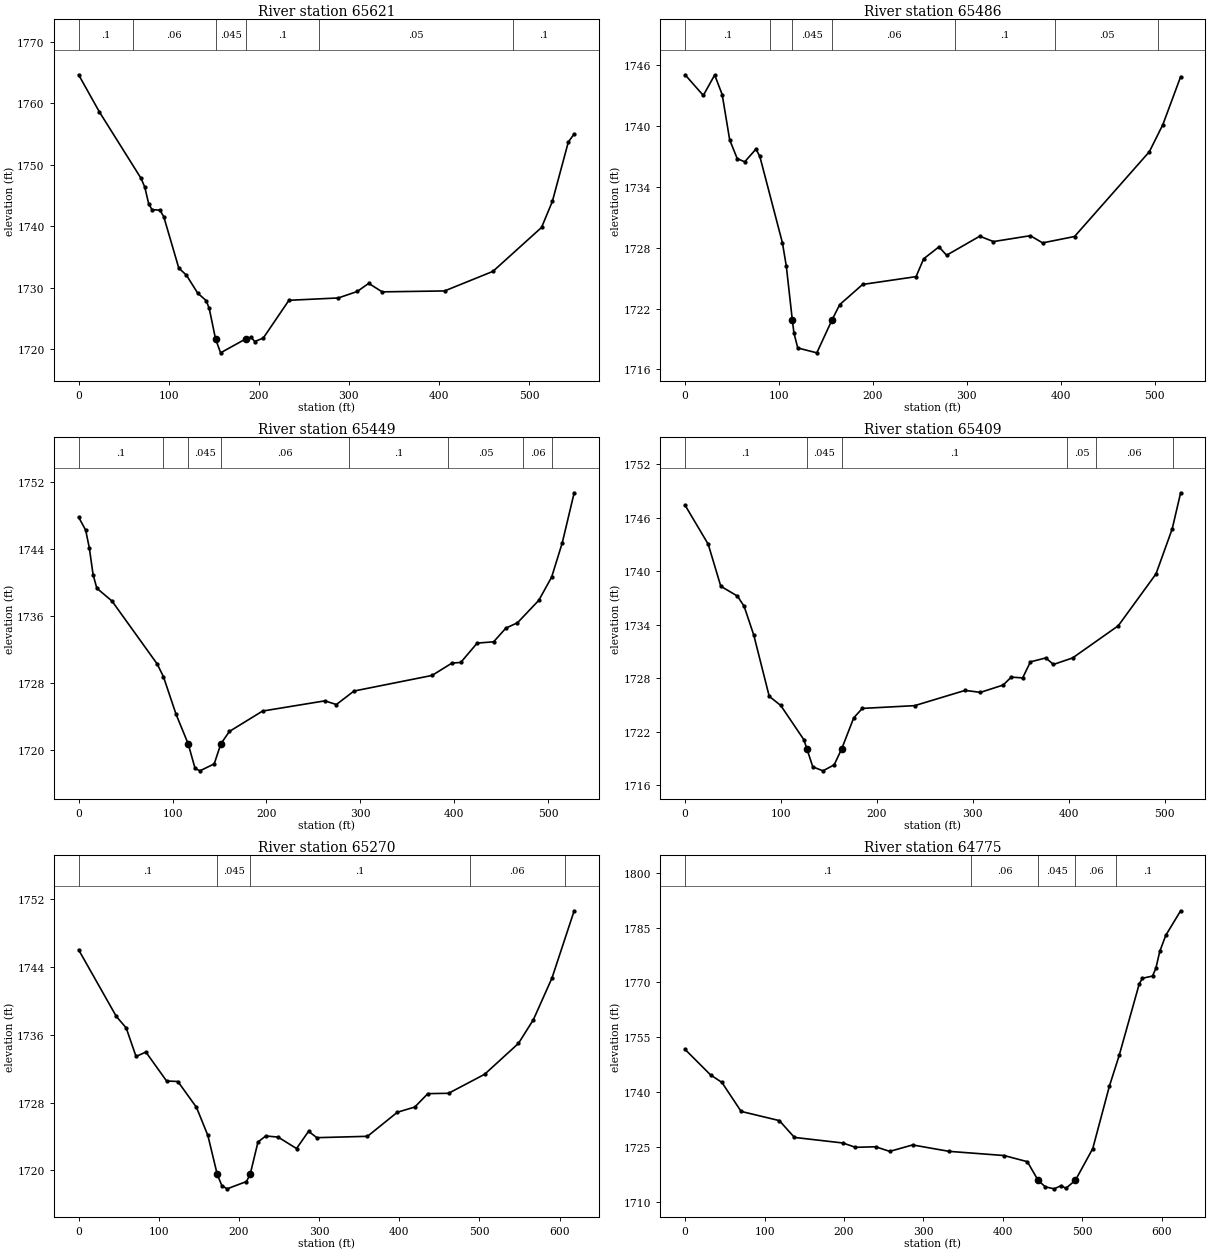
Type RM Length L Ch R = 1 ,65621   ,149.4,135.7,127.4
XS GIS Cut Line= 4
2170644.37693465656307.1503899642170608.94075621656418.728458438
2170543.74710668656613.8716454222170445.75164169656819.011435169
#Sta/Elev= 30
       0 1764.63    23.1 1758.58    69.3  1747.8    73.5 1746.35    77.7  1743.7
    81.4 1742.72    90.3 1742.62    94.5 1741.57   111.2 1733.22   119.7 1732.06
   132.3 1729.12   141.7 1727.92     145 1726.65     152 1721.71   157.6 1719.44
  186.041721.746   191.3 1721.98   195.6 1721.28     205 1721.84   233.5 1727.98
   288.3 1728.36   309.3 1729.41   322.1 1730.73     337 1729.35   406.3  1729.5
     460 1732.68     514 1739.82     526 1744.06   543.7  1753.7   550.2 1755.02
#Mann= 6 ,-1,0
       0      .1       0      60     .06       0     152    .045       0
  186.04      .1       0  267.07     .05       0  482.82      .1       0
Bank Sta=152,186.04
XS Rating Curve= 0 ,0
Exp/Cntr=0.3,0.1

Type RM Length L Ch R = 1 ,65486   ,36.2,36.8,37.1
XS GIS Cut Line= 4
2170475.20928966656273.7792487122170469.12926713656371.059609127
 2170508.0414113656583.8603975342170421.70509143656779.637122868
#Sta/Elev= 30
       0 1745.08    19.4 1743.04    31.5 1745.06    39.5 1743.13    47.5 1738.65
    55.5 1736.81    63.5 1736.49    75.5 1737.75    79.6 1737.02   103.7 1728.48
   107.8  1726.2  114.181720.905   115.9 1719.61     120 1718.12   140.3 1717.64
  156.541720.902   164.7  1722.4   189.1 1724.39     246 1725.16   254.1 1726.92
   270.4  1728.1   278.5 1727.27   313.8 1729.15   328.4 1728.62   367.7  1729.2
   380.8 1728.49   414.8 1729.12   494.5 1737.49   508.9 1740.17   527.8 1744.89
#Mann= 7 ,-1,0
       0      .1       0      90     .06       0  114.18    .045       0
  156.54     .06       0  287.47      .1       0   393.8     .05       0
   503.8      .1       0
Bank Sta=114.18,156.54
XS Rating Curve= 0 ,0
Exp/Cntr(USF)=0,0
Exp/Cntr=0.3,0.1

Type RM Length L Ch R = 1 ,65449   ,35.4,40.3,40.3
XS GIS Cut Line= 4
2170440.55316126656273.7792487122170434.47313873656371.059609127
 2170473.3852829656583.8603975342170387.04896303656779.637122868
#Sta/Elev= 30
       0 1747.82     7.5 1746.27    11.4 1744.14    15.4 1740.96    19.4 1739.34
    35.5 1737.82    83.6 1730.32    90.3  1728.8   103.7 1724.33  116.641720.787
     124 1717.86   129.2 1717.56   144.4 1718.39  151.511720.785   160.6 1722.26
   195.9 1724.69   262.3 1725.91   274.5 1725.47   293.3 1727.08   376.4 1728.94
   397.6 1730.41     407 1730.49   424.5  1732.8     442 1732.95   455.1 1734.59
   467.4 1735.22   490.1  1737.9   503.8 1740.67   515.1 1744.75   527.8 1750.73
#Mann= 8 ,-1,0
       0      .1       0      90     .06       0  116.64    .045       0
  151.51     .06       0  287.47      .1       0   393.8     .05       0
   473.8     .06       0   503.8      .1       0
Bank Sta=116.64,151.51
XS Rating Curve= 0 ,0
Exp/Cntr(USF)=0,0
Exp/Cntr=0.3,0.1

Type RM Length L Ch R = 1 ,65409   ,141.2,138.8,113.9
XS GIS Cut Line= 4
 2170426.6108316656266.9816391492170399.83749081656330.028538408
2170415.38330159656669.4454070252170372.20049388656768.765864763
#Sta/Elev= 30
       0 1747.42    24.1 1743.05    37.2 1738.34    54.5 1737.24    61.5  1736.1
    71.6 1732.86    87.7    1726    99.7 1724.97   123.7 1721.15  126.94 1720.12
   133.1 1718.09   143.7 1717.64   155.4 1718.31   163.3 1720.12   175.8 1723.58
   184.7 1724.64   239.3 1724.95   291.9 1726.66   307.9 1726.44   331.6 1727.26
     340 1728.15   351.9 1728.06     360 1729.86     376  1730.3     384 1729.57
     404  1730.3   451.6 1733.91   490.9 1739.72   507.8 1744.77   516.6 1748.82
#Mann= 6 ,-1,0
       0      .1       0  126.94    .045       0   163.3      .1       0
   398.5     .05       0  428.27     .06       0  508.27      .1       0
Bank Sta=126.94,163.3
XS Rating Curve= 0 ,0
Exp/Cntr(USF)=0,0
Exp/Cntr=0.3,0.1

Type RM Length L Ch R = 1 ,65270   ,459.6,494.5,502.7
XS GIS Cut Line= 5
2170263.16630269656203.2720230932170239.45537294656310.406413486
2170310.63904304656416.8789155862170394.90815525656671.875060319
2170334.71593224656765.993809018
#Sta/Elev= 30
       0    1746      47 1738.15    59.3  1736.8    71.6 1733.43    83.9 1733.95
   109.7 1730.54   123.8 1730.48     147 1727.43   161.2 1724.12  172.911719.524
   178.6 1718.22   185.2 1717.83   209.3 1718.69  213.921719.524   223.7 1723.35
   233.4 1724.06   248.8 1723.93   271.8 1722.58   286.8 1724.61   297.1 1723.86
   360.3 1724.02   397.6 1726.86   419.3 1727.47   435.6 1729.05   461.4 1729.09
   506.4 1731.33   548.6 1734.97   567.2 1737.76   590.4 1742.67   618.1  1750.6
#Mann= 5 ,-1,0
       0      .1       0  172.91    .045       0  213.92      .1       0
   487.8     .06       0  606.36      .1       0
Bank Sta=172.91,213.92
XS Rating Curve= 0 ,0
Exp/Cntr=0.3,0.1

Type RM Length L Ch R = 1 ,64775   ,239.4,236.5,229.4
XS GIS Cut Line= 4
2170209.68682207656162.3807301272169999.89845052656479.743914547
2169925.59486449656587.9342693282169893.33426451 656695.09622121
#Sta/Elev= 30
       0 1751.73    32.1 1744.77    46.3 1742.74    70.5 1734.82   118.6 1732.31
   137.6 1727.72   198.6  1726.2   214.3 1725.02   239.8 1725.17   257.5 1723.91
   286.3 1725.67   332.2 1723.92   401.4 1722.78   430.7  1721.1  444.161716.044
   453.2 1714.24   464.5 1713.69   473.3 1714.58   479.2 1713.82  491.221716.047
     513 1724.67   533.9 1741.68   546.4  1750.2   571.6 1769.69   575.6 1771.16
   588.2 1771.76   592.4 1773.85   597.3 1778.46   604.9 1782.87   623.6 1789.57
#Mann= 5 ,-1,0
       0      .1       0     360     .06       0  444.16    .045       0
  491.22     .06       0  541.68      .1       0
Bank Sta=444.16,491.22
XS Rating Curve= 0 ,0
Exp/Cntr=0.3,0.1

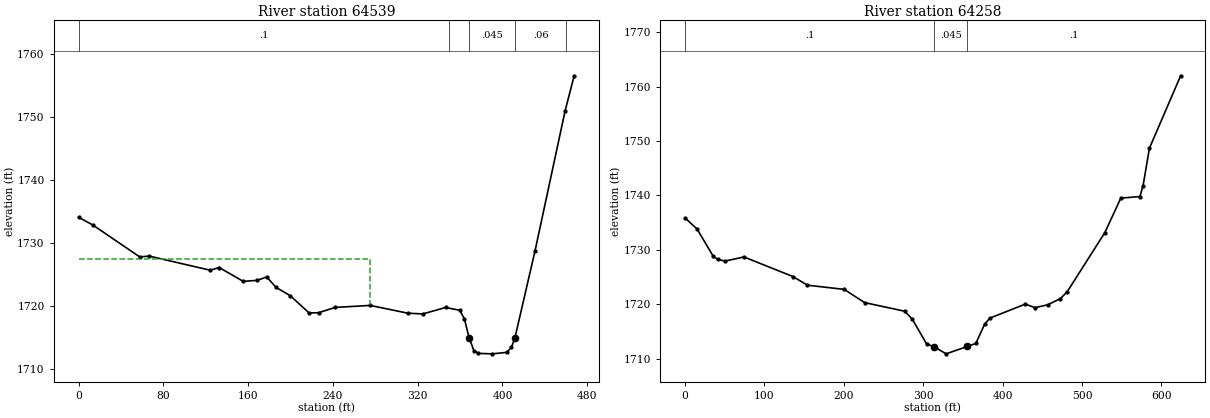
Type RM Length L Ch R = 1 ,64539   ,273.4,280.5,286
XS GIS Cut Line= 2
2169897.41521653656145.2912745132169694.11252649656566.522747394
#Sta/Elev= 30
       0 1734.03    13.2 1732.83    57.6 1727.75    66.7 1727.87   124.2 1725.63
   132.7 1726.06   155.3 1723.86   168.5 1724.02   177.5 1724.56   186.4 1722.89
   199.7 1721.59   217.5 1718.85   226.4 1718.88   242.1 1719.72   275.2 1720.04
   310.8  1718.8   324.9 1718.69   346.3 1719.71   359.6 1719.27   364.1 1717.91
   368.5 1714.94     373 1712.86   377.4 1712.42   390.3 1712.35   404.1 1712.58
   408.5  1713.4  411.74 1714.86   430.7 1728.66   459.2 1750.98   467.7 1756.51
#Mann= 5 ,-1,0
       0      .1       0     350     .06       0   368.5    .045       0
  411.74     .06       0     460      .1       0
#XS Ineff= 2 , 0
          274.65 1727.34
Permanent Ineff=
       F       F
Bank Sta=368.5,411.74
XS Rating Curve= 0 ,0
Exp/Cntr(USF)=0,0
Exp/Cntr=0.3,0.1

Type RM Length L Ch R = 1 ,64258   ,349.4,352.4,327.4
XS GIS Cut Line= 4
2169866.62468091656114.8352103862169657.89804597656248.102756624
2169535.74661245656353.671601904 2169523.4456609656568.467871821
#Sta/Elev= 30
       0 1735.85    15.1 1733.81    35.3 1728.85    40.9 1728.25    50.4 1727.93
    74.1 1728.69   135.8 1725.09   154.1  1723.5   200.4 1722.73     226 1720.31
   276.4 1718.72     286 1717.31   304.3 1712.68   313.4 1712.22   328.8 1710.89
  355.591712.249   366.2  1712.8   377.2  1716.3   383.9 1717.45   428.6 1720.03
   440.7 1719.37   456.7  1719.9   472.6 1721.02   481.3 1722.29   528.8 1733.18
   548.8 1739.49   572.9 1739.79   576.9  1741.8   584.9 1748.67   624.2 1761.97
#Mann= 3 ,-1,0
       0      .1       0   313.4    .045       0  355.59      .1       0
Bank Sta=313.4,355.59
XS Rating Curve= 0 ,0
Exp/Cntr=0.3,0.1