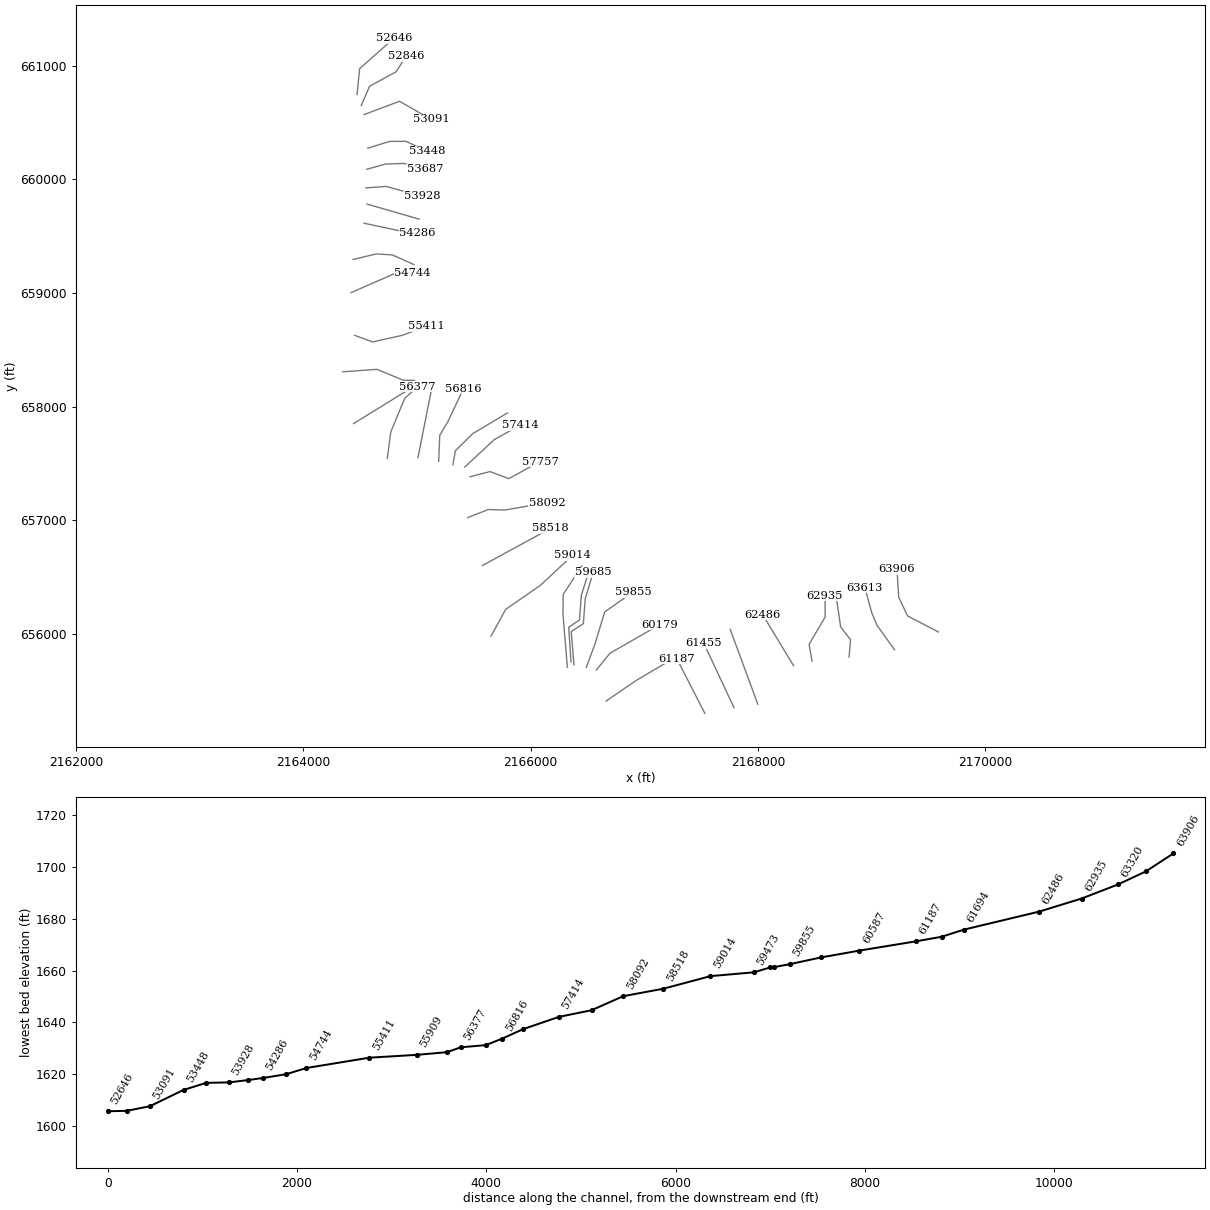
HEC-RAS study LIKANARV.prj: LIKANARV

--- LIKANARV.g01 (geometry) --- (continued)

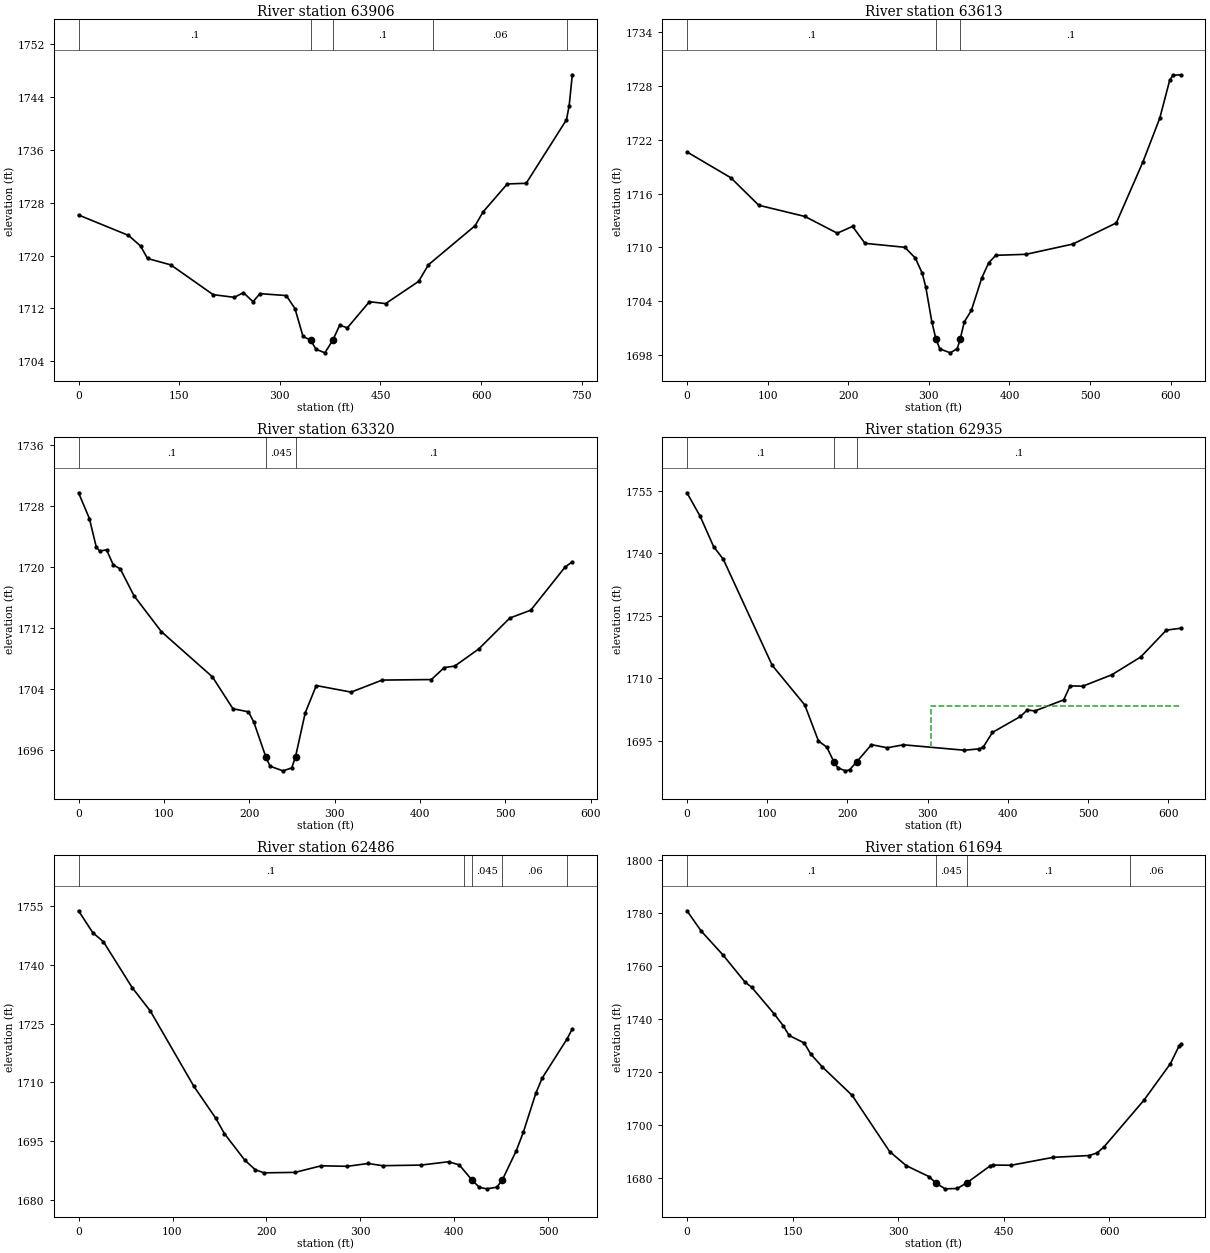
Type RM Length L Ch R = 1 ,63906   ,290.8,293.1,288.5
XS GIS Cut Line= 4
2169586.20517091656016.5705359692169315.26679935656157.275954028
2169236.99982661656322.1455591782169221.73045052656569.912078961
#Sta/Elev= 30
       0 1726.14    74.4 1723.05    92.4 1721.45   102.8 1719.55   137.5 1718.58
   200.6 1714.07   232.2 1713.66   245.7 1714.37   260.1    1713   270.4 1714.22
   309.6 1713.93   322.6 1711.96   334.6 1707.73  345.811707.188   353.9  1705.8
   367.2 1705.25  379.071707.187   389.3 1709.45   400.6 1709.03   433.6    1713
   457.7 1712.71   506.9 1716.08   521.6  1718.6     591 1724.51   603.1 1726.62
   639.1 1730.85   667.2 1730.94   727.3 1740.57   731.3  1742.7     736 1747.39
#Mann= 5 ,-1,0
       0      .1       0  345.81    .045       0  379.07      .1       0
   527.8     .06       0   727.8     .08       0
Bank Sta=345.81,379.07
XS Rating Curve= 0 ,0
Exp/Cntr=0.3,0.1

Type RM Length L Ch R = 1 ,63613   ,287.5,293.2,295.6
XS GIS Cut Line= 4
2169199.94508545655860.7609307762169046.93151974656073.921914547
2168998.30264597656190.0364277532168939.50800325656406.348029744
#Sta/Elev= 30
       0 1720.63    54.5 1717.75      89  1714.7   146.3 1713.45   186.4 1711.59
   205.4 1712.34   220.8 1710.46   270.3 1710.02   283.3 1708.81   291.9 1707.11
   296.3 1705.55   303.7 1701.73  308.651699.868   313.6 1698.72   326.6 1698.28
   335.3 1698.75     3391699.867     344 1701.73   352.7 1702.99   365.7 1706.62
   374.3  1708.3     383 1709.13   420.6 1709.24   478.6 1710.38   532.5 1712.73
   565.3 1719.47   586.4 1724.38   598.8 1728.63   602.9 1729.16   612.4 1729.21
#Mann= 3 ,-1,0
       0      .1       0  308.65    .045       0     339      .1       0
Bank Sta=308.65,339
XS Rating Curve= 0 ,0
Exp/Cntr=0.3,0.1

Type RM Length L Ch R = 1 ,63320   ,396.5,384.4,361.3
XS GIS Cut Line= 4
2168800.41985884655796.498368309   2168813.65011655948.336766851
 2168726.4891152656060.4300032462168685.35328286 656341.59559221
#Sta/Elev= 30
       0 1729.77    12.7 1726.39    20.8 1722.64    24.8 1722.11    32.8 1722.28
    40.8 1720.28    48.9 1719.78    64.9 1716.26      97 1711.54   156.9 1705.59
   180.9 1701.41   199.1    1701   205.4 1699.65  219.341695.117   224.4 1693.86
   239.5 1693.25   249.8 1693.63   254.31695.115   265.6 1700.86   278.6 1704.45
   319.4 1703.59   355.8 1705.17   413.5 1705.24   428.6 1706.82   440.7    1707
     469 1709.26   505.4 1713.32   529.9 1714.35   570.1 1720.01   578.6 1720.71
#Mann= 3 ,-1,0
       0      .1       0  219.34    .045       0   254.3      .1       0
Bank Sta=219.34,254.3
XS Rating Curve= 0 ,0
Exp/Cntr=0.3,0.1

Type RM Length L Ch R = 1 ,62935   ,431.1,448.9,465
XS GIS Cut Line= 4
2168474.42079664655760.5009702562168448.84875845655907.803283345
2168590.58315143656148.6281806432168588.38347701656335.082513249
#Sta/Elev= 30
       0 1754.49    16.4 1748.88    33.2  1741.6    45.3 1738.55   106.2 1713.13
   146.8 1703.63   163.9 1694.98   174.3  1693.5  183.021690.023     188 1688.55
   197.5 1687.82   202.6 1688.05  211.771690.026     230  1694.1   249.4 1693.35
   269.8 1694.06   345.8 1692.76   364.6  1693.1   369.2  1693.5   380.8 1697.04
   415.7 1700.86   424.2 1702.43   433.5 1702.17   469.5 1704.83   477.5 1708.18
   493.5 1708.13   529.5 1710.85   565.5 1715.11   597.5 1721.56   615.4 1722.01
#Mann= 3 ,-1,0
       0      .1       0  183.02    .045       0  211.77      .1       0
#XS Ineff= 2 , 0
                          303.68         1703.48
Permanent Ineff=
       F       F
Bank Sta=183.02,211.77
XS Rating Curve= 0 ,0
Exp/Cntr=0.3,0.1

Type RM Length L Ch R = 1 ,62486   ,787.2,791.8,766.5
XS GIS Cut Line= 2
2168311.70223688655720.2996971372168039.62322715656169.875365063
#Sta/Elev= 30
       0 1753.86    15.1 1748.28    26.5 1745.94    57.1 1734.21    76.3 1728.27
   122.6 1709.03     146 1700.83   155.3 1696.87   176.8 1690.14     188 1687.67
   197.4 1686.86   230.4 1686.98   258.2 1688.66   286.2 1688.53   308.1 1689.25
   323.6 1688.69   364.4 1688.84   393.8  1689.7   405.2 1688.89  418.681685.032
   426.5 1683.16   434.3 1682.77   445.2 1683.19  450.98 1685.03   465.9 1692.54
   473.3 1697.19   486.7 1707.22   493.5 1711.11     520 1721.13   525.5 1723.68
#Mann= 5 ,-1,0
       0      .1       0     410     .06       0  418.68    .045       0
  450.98     .06       0     520      .1       0
Bank Sta=418.68,450.98
XS Rating Curve= 0 ,0
Exp/Cntr=0.3,0.1

Type RM Length L Ch R = 1 ,61694   ,235.9,239.3,239.2
XS GIS Cut Line= 2
2167997.85087354655380.9105615312167755.14638282656039.168075665
#Sta/Elev= 30
       0 1780.76    20.2 1773.12    51.4 1764.02    82.5 1753.86    91.8 1751.95
   123.9 1741.86   136.7 1737.43   145.2  1733.7   166.6 1730.89   175.9 1726.68
   192.1 1721.91   234.8 1711.08     288 1689.91   311.5  1684.6   344.1 1680.44
   353.5 1678.04   366.9 1675.84     384 1675.97  397.25 1678.02   430.9 1684.53
   435.1 1684.81   460.7 1684.74   520.4 1687.73   571.6 1688.41     583 1689.42
   592.9 1691.77   649.4 1709.31   686.8 1723.02   699.2 1729.71   701.6 1730.37
#Mann= 4 ,-1,0
       0      .1       0   353.5    .045       0  397.25      .1       0
     630     .06       0
Bank Sta=353.5,397.25
XS Rating Curve= 0 ,0
Exp/Cntr=0.3,0.1

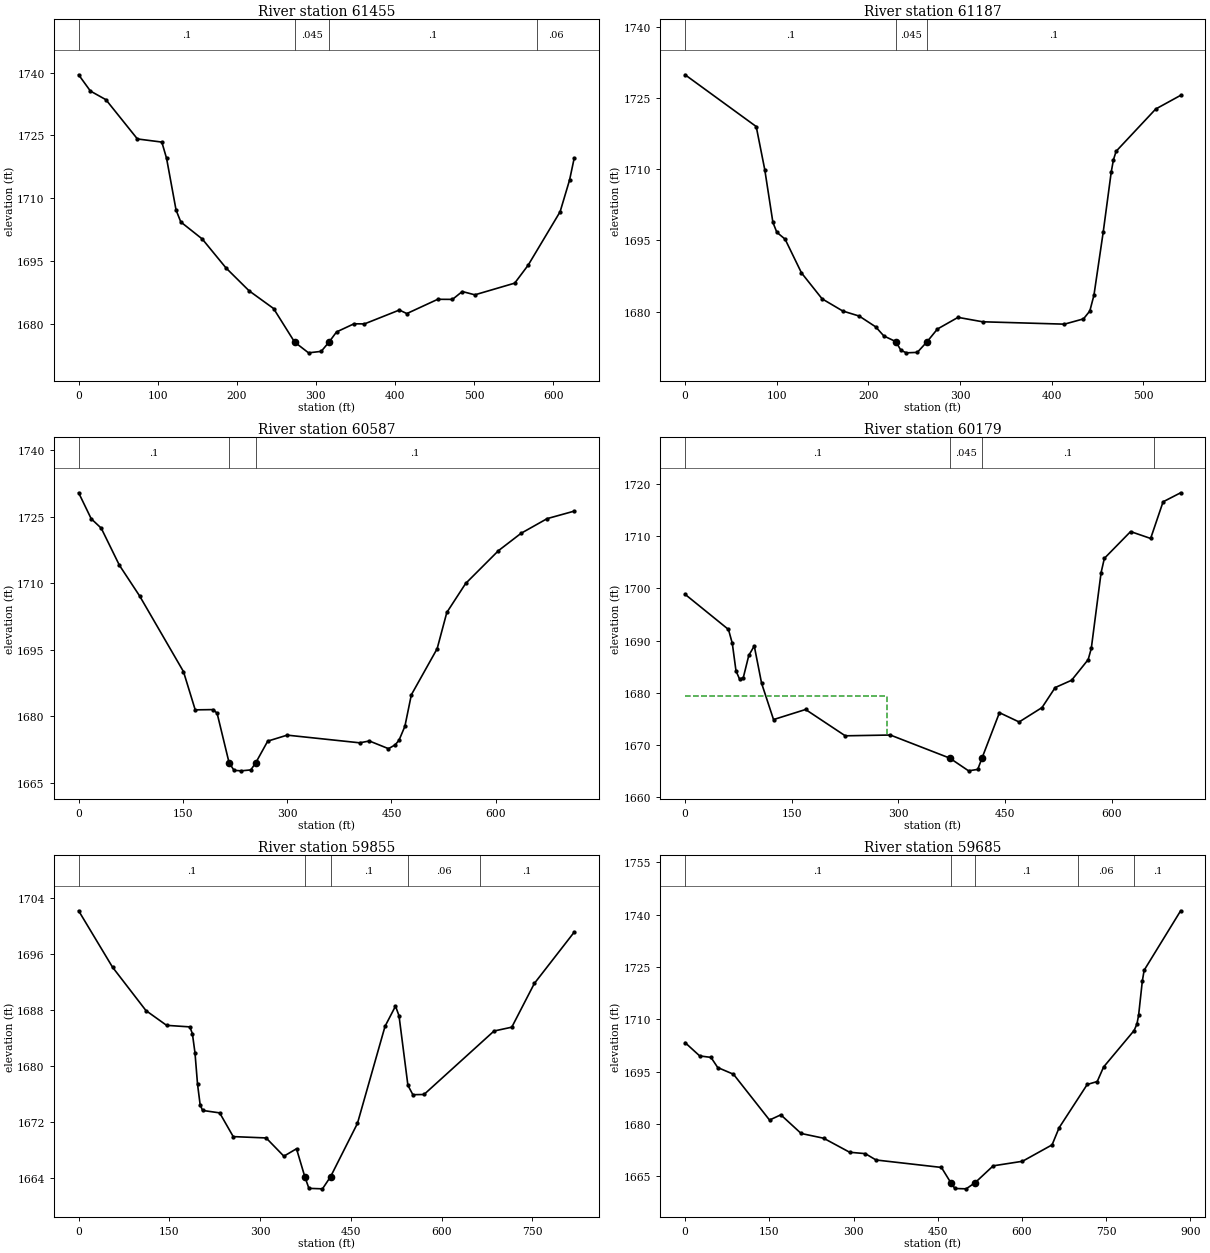
Type RM Length L Ch R = 1 ,61455   ,266,267.7,266.3
XS GIS Cut Line= 2
2167788.77141635655349.9243475952167522.86904909655917.270487631
#Sta/Elev= 30
       0 1739.48    14.9 1735.59    34.5 1733.53    74.3 1724.15   105.2  1723.4
   111.2 1719.52   123.2 1707.16   129.2 1704.31   156.3 1700.25   186.4 1693.32
   215.6 1687.86   246.5 1683.64   273.1 1675.62   290.7 1673.05   306.7  1673.4
  316.54  1675.6   326.1 1678.04   348.2 1679.99   361.4 1679.96   405.6 1683.28
     415 1682.43   454.1 1685.84   472.7 1685.82   485.1  1687.7     501 1686.91
   551.4  1689.7   568.4 1693.99   608.8 1706.75   620.8 1714.35   626.6 1719.53
#Mann= 4 ,-1,0
       0      .1       0   273.1    .045       0  316.54      .1       0
     580     .06       0
Bank Sta=273.1,316.54
XS Rating Curve= 0 ,0
Exp/Cntr(USF)=0,0
Exp/Cntr=0.3,0.1

Type RM Length L Ch R = 1 ,61187   ,621.8,600.5,567.2
XS GIS Cut Line= 2
2167532.04610221  655300.08268742167285.68709248655781.432815579
#Sta/Elev= 30
       0 1729.86    77.6 1718.96    86.9 1709.91    95.8 1698.78   100.1 1696.69
   109.1 1695.25     127 1688.14   149.5 1682.68     172 1680.12     190 1679.05
   207.9 1676.79   216.9 1674.86  229.861673.678   235.5 1671.84   241.5 1671.31
   253.4 1671.41  264.15 1673.68   275.3 1676.32   297.8 1678.78   324.6 1677.85
   413.9 1677.35   434.7 1678.46   441.6 1680.12   446.1 1683.44   456.3 1696.85
     465 1709.43   467.4 1711.97   470.3 1713.75   513.5 1722.65   540.7 1725.53
#Mann= 3 ,-1,0
       0      .1       0  229.86    .045       0  264.15      .1       0
Bank Sta=229.86,264.15
XS Rating Curve= 0 ,0
Exp/Cntr=0.3,0.1

Type RM Length L Ch R = 1 ,60587   ,401.3,407.6,403.2
XS GIS Cut Line= 3
2166663.80108923655408.4403450572166934.07943104655593.609608439
2167266.08871714655788.941299617
#Sta/Elev= 30
       0 1730.42    18.1 1724.56    32.5 1722.44    58.6 1714.09    87.7 1707.16
   150.8  1690.1   167.7 1681.47   193.6 1681.53   199.2  1680.7  216.341669.592
   223.5 1667.83   233.9 1667.72   247.7 1667.93  254.951669.589     272 1674.42
     300 1675.77   404.3 1674.04   418.2 1674.45   445.7 1672.72   455.4 1673.59
   460.9 1674.64   469.3 1677.76   478.6 1684.87   515.7 1695.26   529.6 1703.43
   556.7 1709.97   603.9 1717.37   636.4 1721.28   673.9 1724.59   712.8 1726.28
#Mann= 3 ,-1,0
       0      .1       0  216.34    .045       0  254.95      .1       0
Bank Sta=216.34,254.95
XS Rating Curve= 0 ,0
Exp/Cntr=0.3,0.1

Type RM Length L Ch R = 1 ,60179   ,303.4,324.3,336.7
XS GIS Cut Line= 3
2166577.73093182655681.6441324892166697.51863192655829.075147997
2167137.17898173656081.814031725
#Sta/Elev= 30
       0 1698.87      61 1692.14    66.4 1689.48    71.6  1684.2    76.7 1682.61
    81.9 1682.93    89.6 1687.17    97.3 1688.98   107.6 1681.84   124.4 1674.88
   169.5 1676.81   225.3 1671.77   288.7 1671.92   372.31667.497   398.8 1665.06
   411.7 1665.34  417.57 1667.47   442.2  1676.2   469.9 1674.42   502.1 1677.18
   520.6 1681.01   543.7 1682.41     567 1686.36   571.4  1688.5   585.2 1703.03
   589.8 1705.76   626.7 1710.89   654.9 1709.57   672.4 1716.59   697.1 1718.32
#Mann= 4 ,-1,0
       0      .1       0   372.3    .045       0  417.57      .1       0
  659.96     .06       0
#XS Ineff= 2 , 0
          284.34  1679.3
Permanent Ineff=
       F       F
Bank Sta=372.3,417.57
XS Rating Curve= 0 ,0
Exp/Cntr(USF)=0,0
Exp/Cntr=0.3,0.1

Type RM Length L Ch R = 1 ,59855   ,168.4,169.7,177.9
XS GIS Cut Line= 4
2166490.00571758655704.6364351692166566.68245684655913.883305871
2166651.20206743656192.0893488742166900.19912684656368.879074481
#Sta/Elev= 30
       0 1702.11      56 1694.08   111.3 1687.89   145.4 1685.79   183.8 1685.57
     188 1684.61   192.3 1681.88   196.5 1677.42   200.8  1674.5   204.8 1673.67
   233.1 1673.32   255.5 1669.94   309.9 1669.75   339.2 1667.15   360.1 1668.21
  373.751664.243   380.6 1662.57     403  1662.5  416.461664.241   460.8 1671.82
   506.4 1685.65   523.7 1688.53   529.5 1687.16   544.2 1677.25   552.4 1675.91
   570.8 1675.94   686.5 1684.98   715.9 1685.53   753.2 1691.76     819 1699.06
#Mann= 5 ,-1,0
       0      .1       0  373.75    .045       0  416.46      .1       0
  543.61     .06       0  663.61      .1       0
Bank Sta=373.75,416.46
XS Rating Curve= 0 ,0
Exp/Cntr=0.3,0.1

Type RM Length L Ch R = 1 ,59685   ,42.5,41.8,44.6
XS GIS Cut Line= 5
     2166381.392      655727.2712166356.84704134656019.349718088
2166463.58521457656089.6077561642166480.20462587656308.102818601
2166549.57472418656540.609582175
#Sta/Elev= 30
       0  1703.3      26 1699.48    46.1 1699.06    58.1 1696.15    86.2 1694.22
   150.4 1681.08   170.5 1682.58   206.7 1677.23   246.8 1675.86   293.1 1671.84
     321 1671.44   340.1 1669.62   456.6 1667.48   473.2 1663.13   480.6 1661.44
   500.7 1661.34  516.741663.129   548.8 1667.94     601 1669.25   653.7 1673.96
   666.2 1678.86   716.3 1691.29   734.1 1692.13   745.5 1696.31   799.8 1706.77
   804.8  1708.6   807.8 1711.12   814.5 1721.01   817.7 1724.07   882.7 1741.13
#Mann= 5 ,-1,0
       0      .1       0   473.2    .045       0  516.74      .1       0
  700.02     .06       0  800.02      .1       0
Bank Sta=473.2,516.74
XS Rating Curve= 0 ,0
Exp/Cntr=0.3,0.1

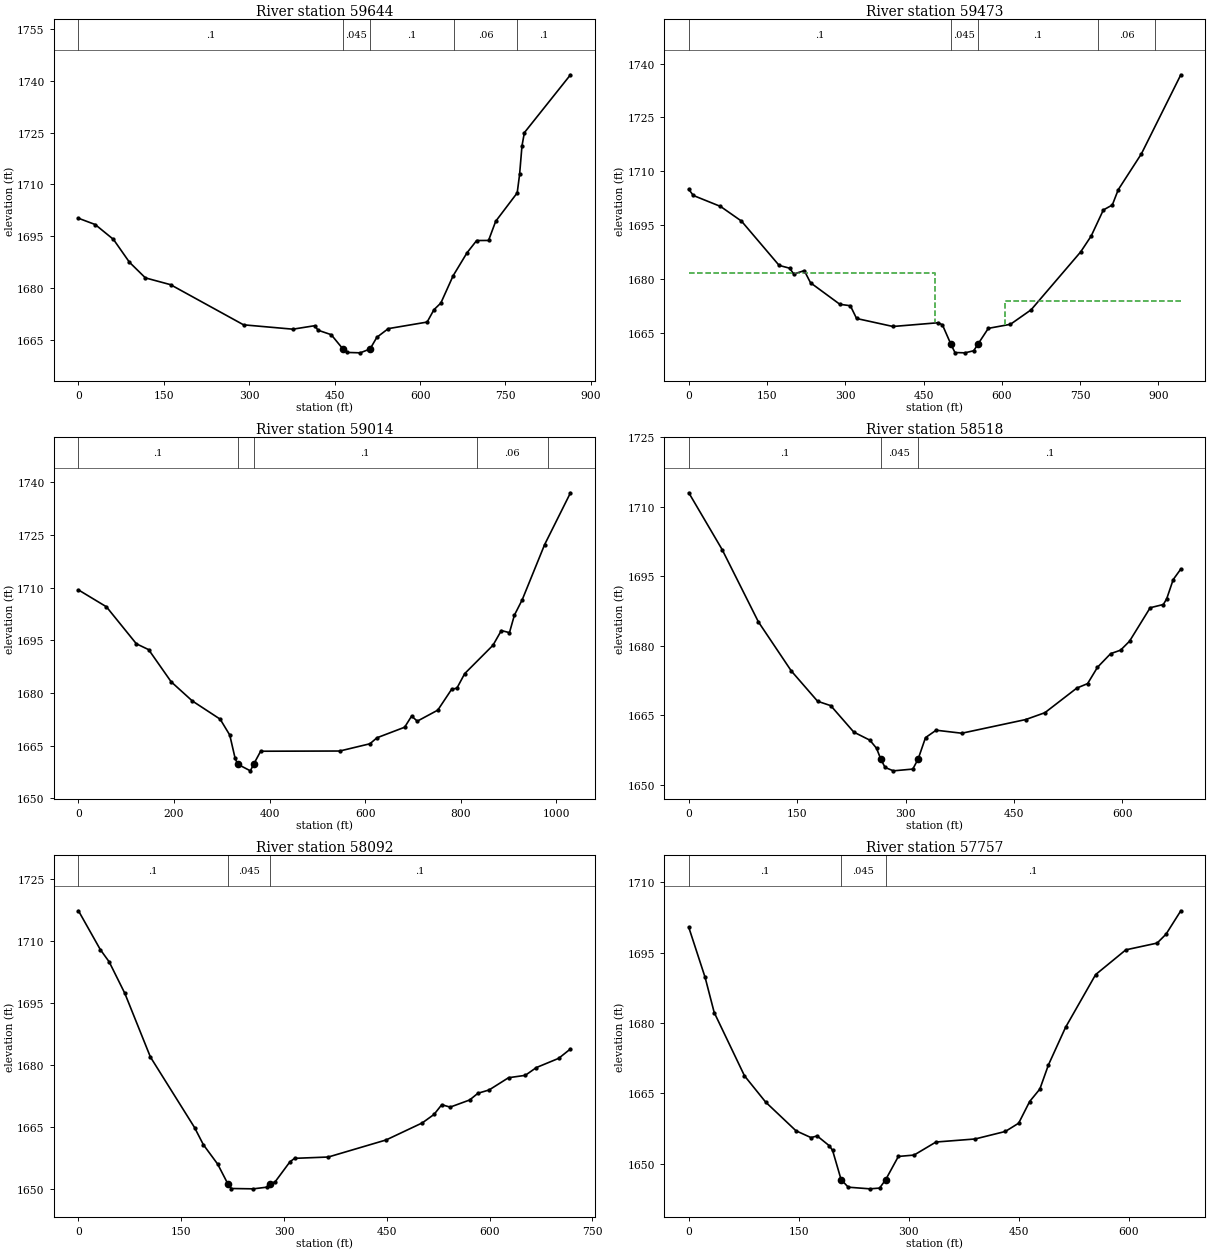
Type RM Length L Ch R = 1 ,59644   ,167.3,170.7,165.2
XS GIS Cut Line= 5
2166355.28619666655751.8453870352166334.79458635656057.435266291
2166429.37271453  656122.28883992166445.99212582656340.783902337
2166514.01110802656554.375040276
#Sta/Elev= 30
       0 1700.18    29.4 1698.36    61.5 1694.05    89.5 1687.45   117.6 1682.91
   161.7 1680.95     290 1669.32   376.6 1668.06   414.7 1669.06     421 1667.75
   443.9 1666.47  464.491662.337     472 1661.33   494.9 1661.21  512.191662.337
   524.1 1665.71   544.2 1668.22   612.4 1670.12   624.4  1673.7   636.5 1675.63
   658.1 1683.54   682.5 1690.19   699.4 1693.73   720.3 1693.75   732.8 1699.29
   770.6 1707.52   774.8 1712.85     779 1721.13   783.2 1724.96   864.2 1741.72
#Mann= 5 ,-1,0
       0      .1       0  464.49    .045       0  512.19      .1       0
  660.08     .06       0  770.08      .1       0
Bank Sta=464.49,512.19
XS Rating Curve= 0 ,0
Exp/Cntr=0.3,0.1

Type RM Length L Ch R = 1 ,59473   ,475.5,459.2,444.8
XS GIS Cut Line= 4
2166323.17889004655704.5596557642166284.45283732656169.723503361
2166286.11882562656347.0798561572166449.44579907656597.583414018
#Sta/Elev= 30
       0 1704.95     8.6 1703.23    60.8 1700.17     101 1696.08   173.2 1683.72
   193.3 1682.94   201.3 1681.31   221.4 1682.26   233.4 1678.87   289.6 1672.87
   309.7 1672.47   321.7 1668.91   391.4 1666.68   478.2 1667.73   486.2 1667.14
  502.251661.808   510.2 1659.42   529.4 1659.33   546.2 1659.91  554.541661.806
   574.2 1666.16   616.6 1667.29   656.2 1671.33   751.2 1687.48   771.4 1691.92
   794.7 1699.18   811.9 1700.57   823.3 1704.85   867.6 1714.83   943.2 1736.89
#Mann= 5 ,-1,0
       0      .1       0  502.25    .045       0  554.54      .1       0
  784.14     .06       0  894.14      .1       0
#XS Ineff= 2 , 0
          472.32 1681.57  606.38         1673.83
Permanent Ineff=
       F       F
Bank Sta=502.25,554.54
XS Rating Curve= 0 ,0
Exp/Cntr=0.3,0.1

Type RM Length L Ch R = 1 ,59014   ,493.3,496,500
XS GIS Cut Line= 4
2165650.95385128655979.0071290352165780.53490381 656215.48340713
 2166087.1980664656428.1923177632166370.07146774656691.742822371
#Sta/Elev= 30
       0 1709.34    58.5 1704.54   121.1 1694.02   146.9 1692.34     194 1683.19
   238.2 1677.75   296.5 1672.56   316.6 1668.04   327.6 1661.53  333.071659.756
   359.7 1657.86  366.621659.759   381.2 1663.44   546.7  1663.5   609.8 1665.56
   624.6 1667.27   682.5 1670.27   697.1 1673.45   708.9 1671.99   751.8 1675.13
   780.9 1681.08   791.8 1681.38   808.2 1685.53   867.3 1693.59   884.8 1697.78
   901.8 1697.18   912.1 1702.15   928.5 1706.54   975.4 1722.24  1029.5 1736.98
#Mann= 5 ,-1,0
       0      .1       0  333.07    .045       0  366.62      .1       0
  832.86     .06       0  982.86      .1       0
Bank Sta=333.07,366.62
XS Rating Curve= 0 ,0
Exp/Cntr=0.3,0.1

Type RM Length L Ch R = 1 ,58518   ,435.1,425.1,415.3
XS GIS Cut Line= 2
2165575.62459631656601.208368233 2166173.4329844656927.184551861
#Sta/Elev= 30
       0 1713.04    46.2 1700.77    96.3 1685.18   141.9 1674.57   178.3 1668.03
   196.5 1667.08   228.4 1661.37   250.6 1659.63   259.8 1657.89   265.7 1655.55
   271.6 1653.75   283.1 1653.01     310 1653.39   317.4 1655.56   327.6 1660.18
   342.3 1661.78   377.8 1661.13   466.2 1664.08   492.8 1665.56     537 1670.88
   551.9 1671.84   565.6 1675.37   583.8 1678.31   597.5 1679.06   609.9 1680.99
   638.5 1688.22   656.7 1688.92   661.3 1690.13   670.4 1694.31   680.9 1696.58
#Mann= 3 ,-1,0
       0      .1       0   265.7    .045       0   317.4      .1       0
Bank Sta=265.7,317.4
XS Rating Curve= 0 ,0
Exp/Cntr=0.3,0.1

Type RM Length L Ch R = 1 ,58092   ,337.5,335.5,322.4
XS GIS Cut Line= 4
 2165446.4454026657023.1923079192165627.93385647657094.406747092
2165770.57519669657089.403859238 2166145.2221217657154.333392125
#Sta/Elev= 30
       0 1717.23    31.9 1707.86    44.8 1704.91    67.7 1697.29     105 1681.93
   169.4 1664.91   182.3 1660.76   203.2 1656.07  218.431651.173   223.2  1650.2
   255.2 1650.12   275.3 1650.53  278.971651.172   287.3 1651.89   308.5 1656.63
   315.3 1657.48   364.5  1657.8   448.9 1661.92   501.7 1666.04   518.8 1668.08
   530.1 1670.43   542.3 1669.84   570.7 1671.56   582.9 1673.19   599.1 1673.98
   627.5 1676.94   651.9 1677.51   668.1 1679.39   700.6 1681.61   717.9 1683.89
#Mann= 3 ,-1,0
       0      .1       0  218.43    .045       0  278.97      .1       0
Bank Sta=218.43,278.97
XS Rating Curve= 0 ,0
Exp/Cntr=0.3,0.1

Type RM Length L Ch R = 1 ,57757   ,316.6,342.9,356.9
XS GIS Cut Line= 4
2165466.58507562657382.7893651022165643.05610264657428.048121701
 2165808.4139413657365.8605332232166081.83209342657516.791346668
#Sta/Elev= 30
       0 1700.38    22.3 1689.71    34.7 1682.24      76 1668.76   104.9 1663.16
   146.2 1657.06   166.8  1655.6   175.1 1655.96   191.9 1653.84   196.2 1652.86
   207.81646.646   217.6 1645.04   247.1 1644.69   260.3 1644.85  268.611646.646
   285.9 1651.59   307.3 1651.88   337.2 1654.66   390.6 1655.31   431.8 1656.91
     450 1658.67     465 1663.29   478.9 1665.94   490.6 1671.08   513.9 1679.06
     555 1690.32   596.2 1695.59   638.9 1697.03     651 1698.92   671.2 1703.91
#Mann= 3 ,-1,0
       0      .1       0   207.8    .045       0  268.61      .1       0
Bank Sta=207.8,268.61
XS Rating Curve= 0 ,0
Exp/Cntr=0.3,0.1

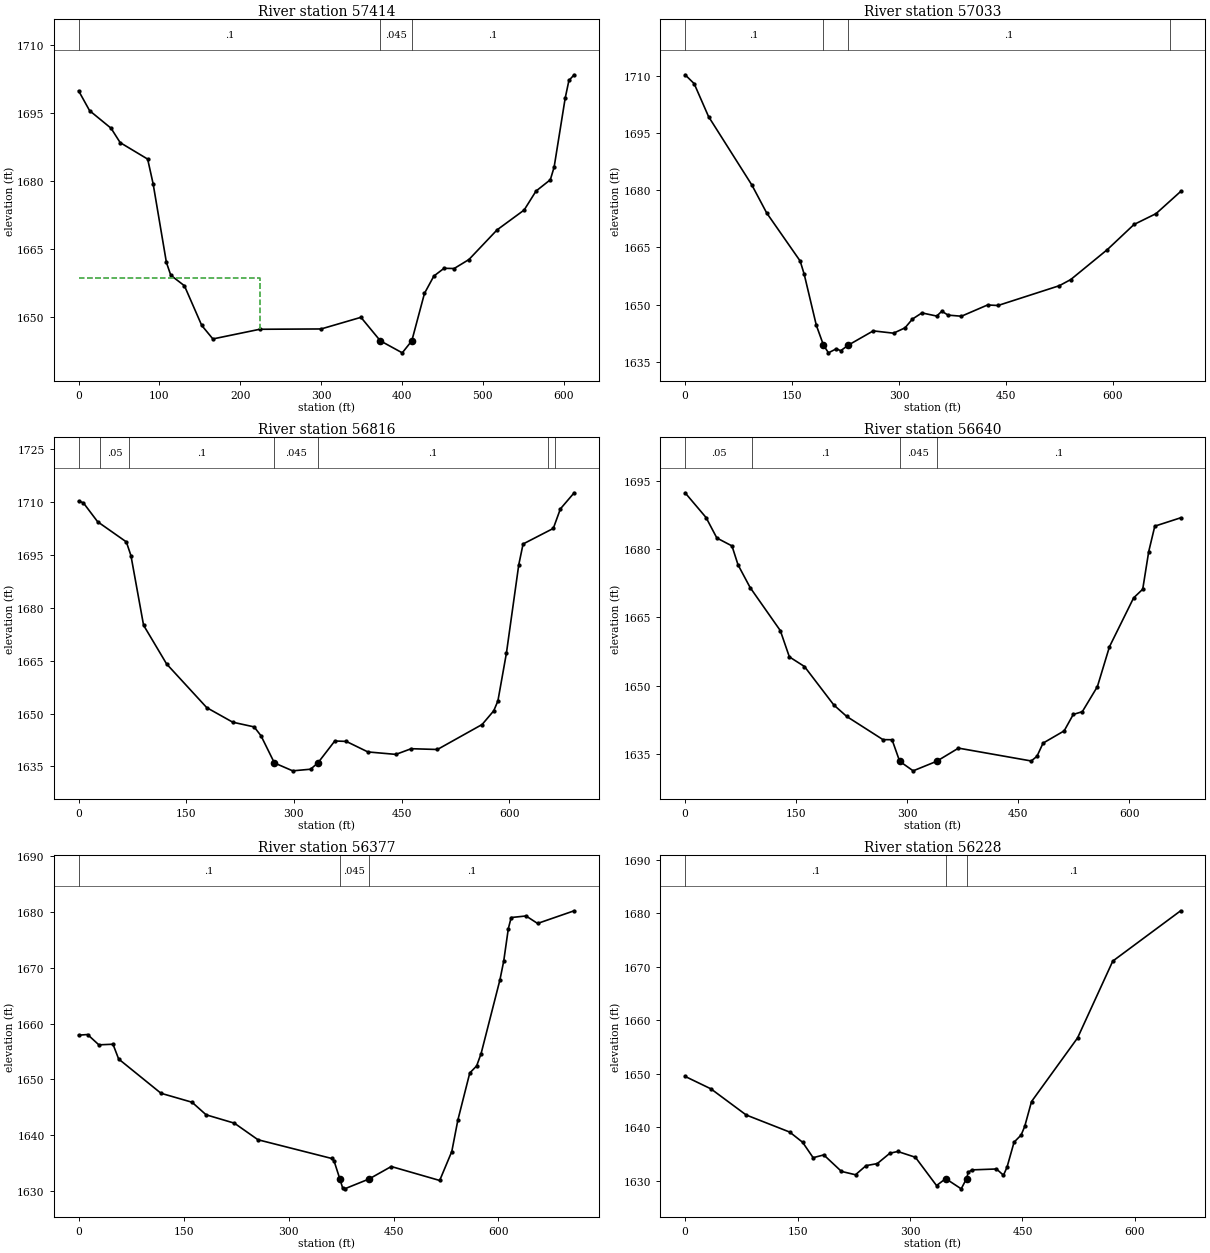
Type RM Length L Ch R = 1 ,57414   ,339.6,380.9,350.6
XS GIS Cut Line= 3
2165420.79326246657467.8744118132165679.57471973657709.311784877
2165905.80504797 657835.67803624
#Sta/Elev= 30
       0 1699.84    13.6 1695.47    40.1 1691.61    51.4 1688.44    85.4 1684.81
    92.2 1679.34   108.6 1662.05     114 1659.23   130.9 1656.91   152.3 1648.18
   166.1  1645.2   224.1 1647.33     300  1647.4   349.3 1649.96  373.271644.787
   400.4 1642.14  412.221644.785   427.9 1655.24   439.5 1659.05   452.1 1660.76
   464.6 1660.71   482.9 1662.69   517.7 1669.22   551.2 1673.59   565.9 1677.77
   583.6 1680.26   588.3 1683.04     602 1698.25   606.6 1702.13   613.1 1703.38
#Mann= 3 ,-1,0
       0      .1       0  373.27    .045       0  412.22      .1       0
#XS Ineff= 2 , 0
          224.07 1658.59
Permanent Ineff=
       F       F
Bank Sta=373.27,412.22
XS Rating Curve= 0 ,0
Exp/Cntr=0.3,0.1

Type RM Length L Ch R = 1 ,57033   ,210.5,217.4,222.3
XS GIS Cut Line= 4
2165316.71046774657488.6995427312165337.40493942657610.902599623
2165490.85769145657762.2560749892165796.38305718657944.256915166
#Sta/Elev= 30
       0 1710.21    12.7 1707.89    32.9 1699.26    93.8 1681.29   114.4 1674.03
   161.4 1661.43   167.1 1657.94   184.1 1644.58  194.121639.394   201.1 1637.38
   212.1 1638.44   218.3 1637.94   228.91639.396   263.9 1643.13   292.4 1642.53
   308.5 1643.93   318.9 1646.23   332.2 1647.84     353 1647.01   360.1 1648.28
   368.9 1647.26   387.6 1646.97   424.3 1649.92   438.9 1649.78     525 1654.97
     541 1656.58   592.4 1664.44   629.7    1671   660.6 1673.84   695.1 1679.64
#Mann= 4 ,-1,0
       0      .1       0  194.12    .045       0   228.9      .1       0
  679.48     .06       0
Bank Sta=194.12,228.9
XS Rating Curve= 0 ,0
Exp/Cntr=0.3,0.1

Type RM Length L Ch R = 1 ,56816   ,166.6,175.5,186.4
XS GIS Cut Line= 4
 2165191.5784868657518.7136638042165200.94438747657748.830469333
 2165269.9972434657862.8949907832165409.51771973658158.562009217
#Sta/Elev= 30
       0 1710.19     6.5 1709.74    26.5 1704.35    66.5 1698.64    72.9 1694.76
    90.5 1675.03   122.6 1664.06   178.6 1651.67   214.8 1647.55   244.6 1646.22
   254.1 1643.73  272.841636.008   298.3 1633.77   323.2 1634.23  333.421636.009
     357 1642.23     373 1642.11   403.1 1639.13   442.1 1638.43   463.5 1640.04
     500 1639.82   562.3  1646.9   578.5 1650.78   584.3 1653.57   596.2 1667.15
   613.4 1692.18   619.4 1698.05   661.5 1702.46   671.4    1708   690.6 1712.56
#Mann= 7 ,-1,0
       0      .1       0      30     .05       0      70      .1       0
  272.84    .045       0  333.42      .1       0  653.65     .06       0
  663.65      .1       0
Bank Sta=272.84,333.42
XS Rating Curve= 0 ,0
Exp/Cntr=0.3,0.1

Type RM Length L Ch R = 1 ,56640   ,261.8,263.2,251.7
XS GIS Cut Line= 2
2165008.99779304 657551.079939922165139.50583413658207.458617142
#Sta/Elev= 30
       0 1692.44    28.3 1686.99    42.9 1682.48    63.3 1680.74    71.5 1676.57
    87.8 1671.58   128.6 1662.09   140.8 1656.31   161.2 1654.19   200.9 1645.71
   218.3 1643.19   267.2 1638.09   279.5 1638.07  289.77 1633.32     308 1631.22
   339.7 1633.32   369.2 1636.22   467.5 1633.39   475.2 1634.43   483.4 1637.32
   511.9 1640.02   524.2 1643.64   536.4 1644.24   556.8 1649.77   573.1 1658.55
   605.7  1669.3     618 1671.21   626.1  1679.5   634.3 1685.09   669.2 1686.93
#Mann= 4 ,-1,0
       0     .05       0      90      .1       0  289.77    .045       0
   339.7      .1       0
Bank Sta=289.77,339.7
XS Rating Curve= 0 ,0
Exp/Cntr(USF)=0,0
Exp/Cntr=0.3,0.1

Type RM Length L Ch R = 1 ,56377   ,155.7,149.4,131.4
XS GIS Cut Line= 4
 2164739.5392259657544.4894964852164770.15384648657777.119586275
2164891.70840241658071.3574981982165006.99626763658175.229506892
#Sta/Elev= 30
       0 1657.92    12.8 1658.04    28.9 1656.19    49.1  1656.3    57.2 1653.65
   117.7 1647.51   162.1  1645.9   182.2 1643.65   222.6 1642.15   256.3 1639.18
   361.8 1635.82   364.9 1635.43   373.31632.164   377.5 1630.47   380.2 1630.38
     4151632.142   446.8 1634.38     516 1631.88   533.3 1637.07     542 1642.72
     559 1651.15   568.8 1652.41   575.2 1654.63   602.1 1667.84   607.5 1671.19
   614.1 1677.02   618.2 1679.01   639.4 1679.29   655.9 1677.95   708.2 1680.22
#Mann= 3 ,-1,0
       0      .1       0   373.3    .045       0     415      .1       0
Bank Sta=373.3,415
XS Rating Curve= 0 ,0
Exp/Cntr=0.3,0.1

Type RM Length L Ch R = 1 ,56228   ,335.6,318.4,300.6
XS GIS Cut Line= 2
2164442.82320304657850.4807400562165005.15932125658197.862437651
#Sta/Elev= 30
       0 1649.49    34.5 1647.16    81.5 1642.28   139.5 1639.09   156.7 1637.19
   170.8  1634.3     185 1634.82   208.5 1631.74   227.3 1631.11   241.4 1632.82
   256.3 1633.19   273.2 1635.14   283.7 1635.46   307.2 1634.38   335.4 1629.09
   347.6 1630.39   368.3 1628.48  375.37 1630.38   377.7 1631.56   382.4 1632.02
   415.3 1632.19   424.7 1631.02   429.4 1632.52   438.8  1637.2   448.2 1638.53
     453 1640.14   462.1 1644.79   523.5 1656.68   570.5 1671.04     661 1680.44
#Mann= 3 ,-1,0
       0      .1       0   347.6    .045       0  375.37      .1       0
Bank Sta=347.6,375.37
XS Rating Curve= 0 ,0
Exp/Cntr(USF)=0,0
Exp/Cntr=0.3,0.1

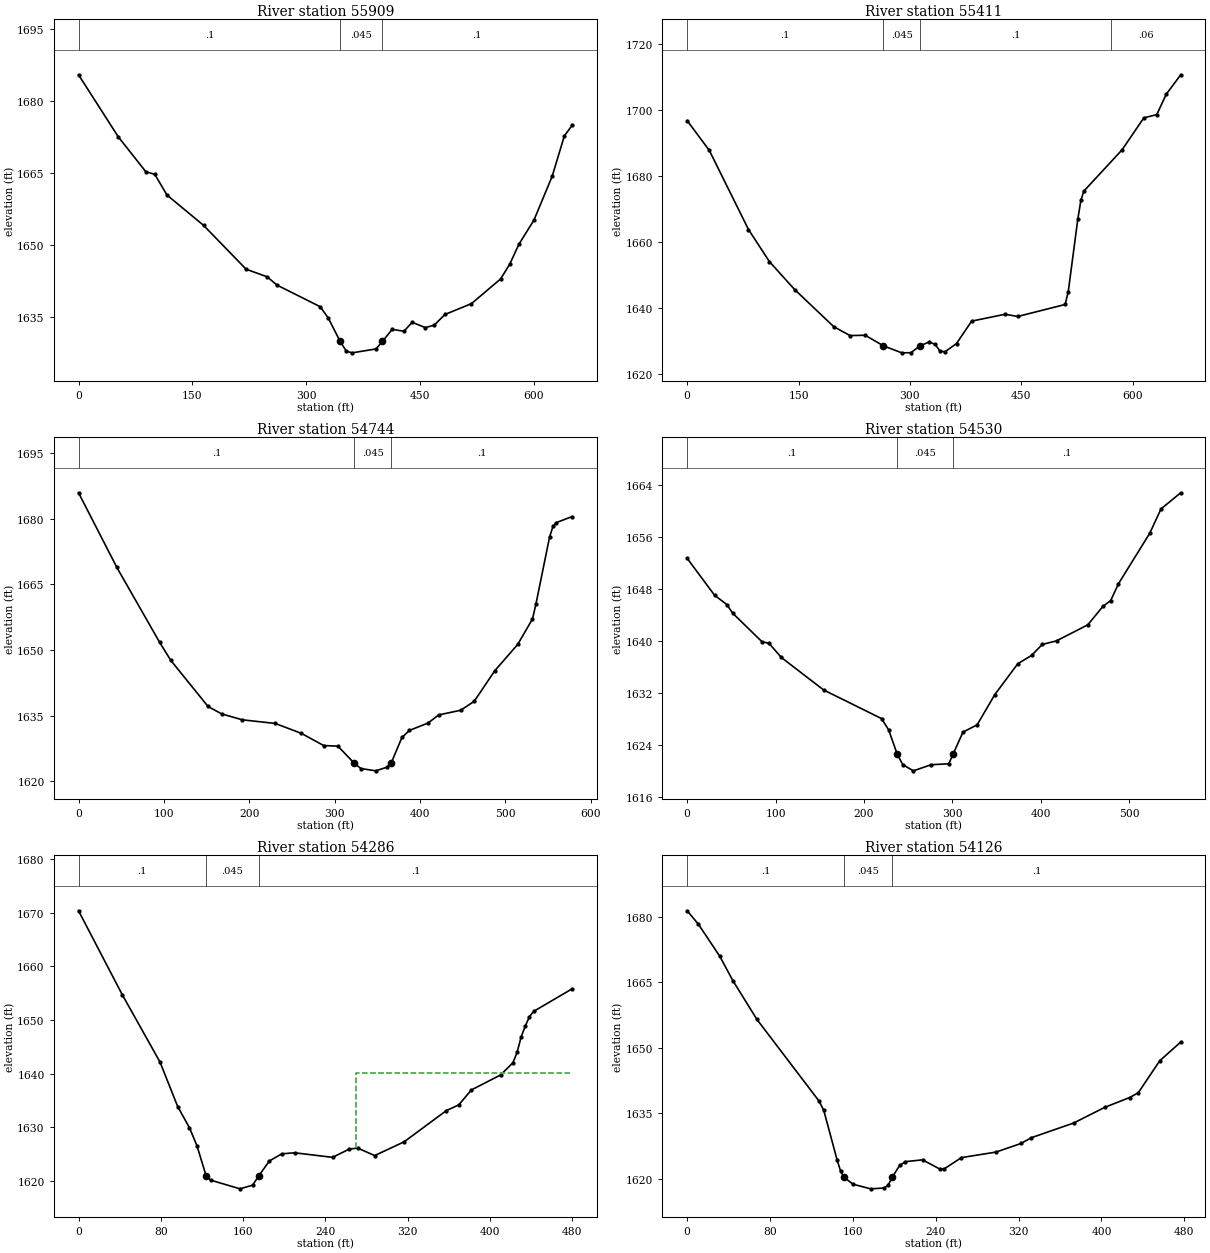
Type RM Length L Ch R = 1 ,55909   ,452.3,498.3,493.6
XS GIS Cut Line= 4
2164347.95429605658306.3213486952164647.81952632658328.026596471
2164881.01785523658231.9880927662164978.41121534658230.841601439
#Sta/Elev= 30
       0 1685.52    52.4 1672.55    88.5 1665.31   100.5 1664.72   116.5 1660.41
   164.7 1654.08   220.8 1644.92   248.9 1643.31   260.9 1641.65   318.4 1637.09
   329.1  1634.7   344.61629.854   352.9 1627.78   360.6 1627.46   391.9 1628.28
   400.41629.864   413.2 1632.36   428.7 1631.97   439.5 1633.84   456.8 1632.73
   468.6 1633.24   482.7 1635.47   517.6 1637.73     556 1642.89     568 1645.95
     580  1650.1     600 1655.19     624 1664.35     640 1672.75   650.2 1674.96
#Mann= 3 ,-1,0
       0      .1       0   344.6    .045       0   400.4      .1       0
Bank Sta=344.6,400.4
XS Rating Curve= 0 ,0
Exp/Cntr=0.3,0.1

Type RM Length L Ch R = 1 ,55411   ,649.3,667.3,648.7
XS GIS Cut Line= 4
2164452.20371708658627.1457170782164610.37924564658569.471178227
2164867.00348243658626.3006491182165086.50887721658706.143995625
#Sta/Elev= 30
       0 1696.88    29.8 1687.84    82.6 1663.82   110.7 1654.09   144.7  1645.6
   197.4 1634.32   219.4 1631.61   239.8 1631.71  264.281628.502     289 1626.37
   301.3 1626.41   313.6 1628.49   325.9 1629.68     334 1628.94   340.7 1626.86
   347.4  1626.7   362.8  1629.2   383.2    1636   428.3 1638.09   445.2 1637.41
   509.1 1641.05   513.3 1644.96   526.1 1666.86   530.3 1672.68   534.2 1675.45
   585.7 1687.99   615.1 1697.73   632.5 1698.69   645.3  1704.9   664.8  1710.8
#Mann= 4 ,-1,0
       0      .1       0  264.28    .045       0   313.6      .1       0
   571.2     .06       0
Bank Sta=264.28,313.6
XS Rating Curve= 0 ,0
Exp/Cntr=0.3,0.1

Type RM Length L Ch R = 1 ,54744   ,220,213.6,192.8
XS GIS Cut Line= 3
2164421.25828953 659003.145094812164820.37024121659178.190653493
2164962.56472394659174.119757846
#Sta/Elev= 30
       0  1685.9    44.9 1668.84    94.9 1651.77     108 1647.63   151.7 1637.08
   167.7 1635.38     192 1634.03   230.3 1633.21   260.9 1630.95   287.1 1628.16
   303.8 1628.02   322.91624.124   330.8  1622.9   348.2 1622.38   361.3 1623.22
   366.11624.125   378.8    1630   387.6 1631.62   409.4  1633.3   421.8 1635.15
   447.6 1636.22   463.4 1638.25   487.6 1645.26   514.4 1651.26   531.7 1657.08
   535.7 1660.43   551.7 1675.79   555.7 1678.22   559.7 1679.09   578.1 1680.47
#Mann= 3 ,-1,0
       0      .1       0   322.9    .045       0   366.1      .1       0
Bank Sta=322.9,366.1
XS Rating Curve= 0 ,0
Exp/Cntr=0.3,0.1

Type RM Length L Ch R = 1 ,54530   ,248.9,244.3,242.7
XS GIS Cut Line= 4
2164438.02511329659294.7057535362164641.46411852659343.646268943
2164783.48757499  659335.00970742164972.53231097659250.563327875
#Sta/Elev= 30
       0  1652.7      31 1647.02    44.8 1645.59    51.6 1644.24    84.5 1639.88
    92.7  1639.6   106.6 1637.43   154.4 1632.43     220 1628.02     228 1626.29
   237.71622.548     244 1620.93     256 1619.97   276.1 1620.91   296.1 1621.06
  301.03 1622.56   312.1 1625.93   328.2 1627.06   348.2 1631.72   374.2 1636.47
   389.8 1637.75   401.9 1639.44     418 1639.99   453.4 1642.46   470.6 1645.31
   479.3 1646.19   488.1 1648.78   523.5 1656.56   536.3 1660.32   558.6  1662.8
#Mann= 3 ,-1,0
       0      .1       0   237.7    .045       0  301.03      .1       0
Bank Sta=237.7,301.03
XS Rating Curve= 0 ,0
Exp/Cntr(USF)=0,0
Exp/Cntr=0.3,0.1

Type RM Length L Ch R = 1 ,54286   ,160.6,159.5,157.2
XS GIS Cut Line= 3
2164534.68742759659614.0606886392164923.40703505659531.379489444
2165005.65815475659532.269018043
#Sta/Elev= 30
       0 1670.37    42.4 1654.76    79.2 1642.16    96.4 1633.86   107.8 1629.92
   115.1 1626.57   123.91621.015   128.3 1620.16   156.9 1618.53   169.2 1619.22
   175.3 1620.99   185.5 1623.73   197.6 1625.06   210.1 1625.25   246.9  1624.4
   263.2 1625.95   271.4 1626.12   287.8 1624.73   316.4 1627.29   357.3 1633.09
   369.6 1634.19   381.8 1636.97   410.2 1639.76   422.2 1642.04   426.2 1643.96
   430.2 1646.87   434.2 1648.89   438.2  1650.6   442.2  1651.6   479.7 1655.82
#Mann= 3 ,-1,0
       0      .1       0   123.9    .045       0   175.3      .1       0
#XS Ineff= 2 , 0
                          269.73         1640.18
Permanent Ineff=
       F       F
Bank Sta=123.9,175.3
XS Rating Curve= 0 ,0
Exp/Cntr=0.3,0.1

Type RM Length L Ch R = 1 ,54126   ,197.4,198.2,197.9
XS GIS Cut Line= 2
2164561.81582874659782.1916717072165019.55359048659649.764394723
#Sta/Elev= 30
       0 1681.36    10.8  1678.3    31.6  1670.9    44.1 1665.38    67.3 1656.51
   127.4 1637.78   131.9 1635.66   144.8 1624.29   148.2 1621.73   151.41620.366
   160.2 1618.77   177.1 1617.72   189.8  1617.9     194 1618.54  197.85 1620.32
   205.1 1623.08   210.7 1623.94   227.3 1624.36     244 1622.23   248.1 1622.28
   264.8 1624.87   298.1 1626.13   322.5 1628.12   332.1 1629.41   373.1 1632.78
   403.2 1636.38   427.2 1638.62   435.5 1639.71   456.3 1647.05   476.5 1651.32
#Mann= 3 ,-1,0
       0      .1       0   151.4    .045       0  197.85      .1       0
Bank Sta=151.4,197.85
XS Rating Curve= 0 ,0
Exp/Cntr(USF)=0,0
Exp/Cntr=0.3,0.1

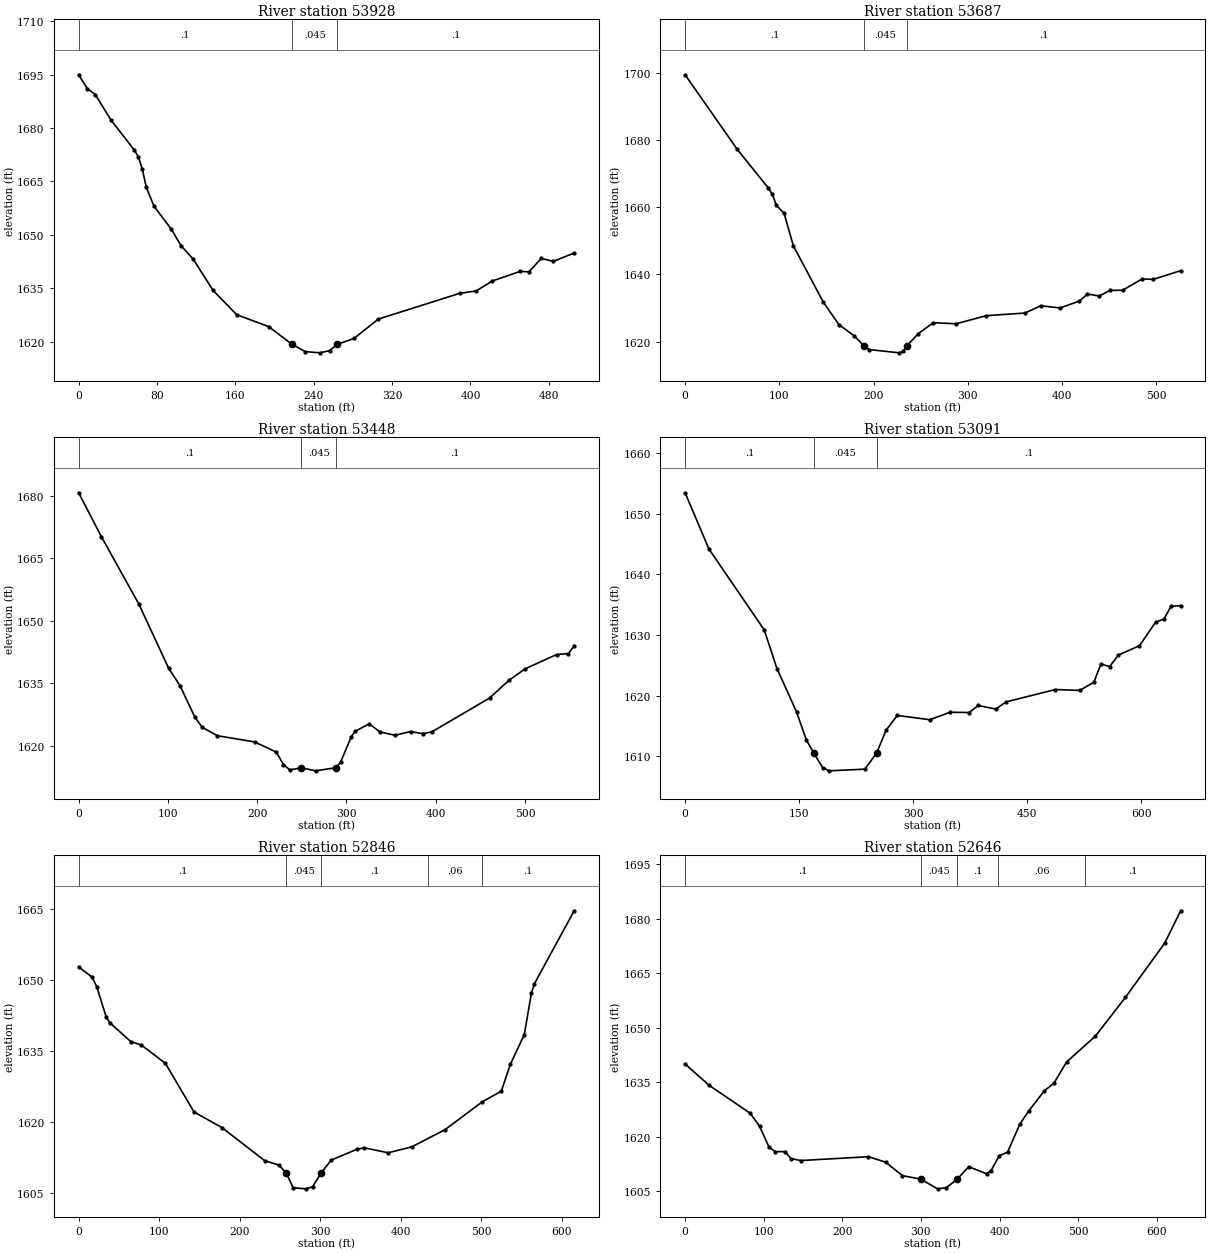
Type RM Length L Ch R = 1 ,53928   ,220.1,241.3,247.3
XS GIS Cut Line= 3
 2164551.2600313659925.1747461312164730.70858779 659937.64977947
2165044.50365716659849.364928148
#Sta/Elev= 30
       0 1694.96     8.9 1691.08      17  1689.4      33 1682.26      57 1673.76
    61.1 1671.86    65.1 1668.36    69.1 1663.33    77.1 1657.95    94.6  1651.6
   104.4 1646.98   117.2 1643.08   137.2 1634.38   161.3 1627.56   193.9 1624.21
  217.59 1619.28   231.3 1617.18   246.3 1616.83   256.2 1617.45   264.21619.234
   281.1 1620.87   306.1 1626.33   389.2 1633.56   405.8 1634.22   422.4 1637.03
   450.6  1639.7   459.8  1639.6   472.3 1643.36   484.7 1642.52   505.9  1644.9
#Mann= 3 ,-1,0
       0      .1       0  217.59    .045       0   264.2      .1       0
Bank Sta=217.59,264.2
XS Rating Curve= 0 ,0
Exp/Cntr(USF)=0,0
Exp/Cntr=0.3,0.1

Type RM Length L Ch R = 1 ,53687   ,231.2,238.7,231.4
XS GIS Cut Line= 4
 2164559.0288115660088.5877294852164720.29361088660134.205124596
2164882.65741917660140.2451146292165071.54059435 660088.59384664
#Sta/Elev= 30
       0 1699.52    55.2 1677.35    88.5 1665.72    92.6 1663.87    96.8 1660.64
   105.1 1658.21   114.8 1648.61   146.7 1631.74   163.3 1625.04   179.5 1621.71
   189.6 1618.78   195.5 1617.62   227.5 1616.65   231.5 1617.17   235.5 1618.79
   247.5 1622.38   263.5 1625.63   287.6 1625.31   319.6 1627.73   360.7 1628.51
   377.3 1630.68     398 1630.03   418.5 1632.08     427 1634.19   439.5 1633.59
     451 1635.26   464.3 1635.31   485.1 1638.68   496.6 1638.53   525.9 1641.14
#Mann= 3 ,-1,0
       0      .1       0   189.6    .045       0   235.5      .1       0
Bank Sta=189.6,235.5
XS Rating Curve= 0 ,0
Exp/Cntr=0.3,0.1

Type RM Length L Ch R = 1 ,53448   ,338.9,357.3,352.7
XS GIS Cut Line= 4
2164567.81613497660274.5067666912164758.87424221660333.971272227
2164903.84339483660334.498796902  2165094.011212660245.542695227
#Sta/Elev= 30
       0 1680.69    25.5 1670.14    67.4 1653.99   100.9 1638.53   113.5 1634.41
   130.2 1626.81   138.6 1624.36   155.4 1622.37   197.3 1620.87   221.4 1618.43
   229.4 1615.44   236.5 1614.17   249.4 1614.66   265.4 1613.94   288.3  1614.7
   293.4 1616.04   305.4 1622.15   309.4 1623.39   325.4 1625.22   337.4 1623.29
   354.3 1622.48   371.9 1623.38   385.2 1622.87   395.4 1623.27   460.3 1631.42
   482.3 1635.73     500 1638.42   535.3 1641.86   548.6 1642.09     555 1643.95
#Mann= 3 ,-1,0
       0      .1       0   249.4    .045       0   288.3      .1       0
Bank Sta=249.4,288.3
XS Rating Curve= 0 ,0
Exp/Cntr=0.3,0.1

Type RM Length L Ch R = 1 ,53091   ,238.2,245.1,240.5
XS GIS Cut Line= 3
2164534.94652616660570.0380079642164846.82235964660687.111397761
2165123.19232899 660528.77443615
#Sta/Elev= 30
       0 1653.46    31.4 1644.18   103.9 1630.89   120.9 1624.46   146.6 1617.33
   159.4 1612.72  169.31 1610.55   180.8 1608.18   189.3 1607.63   236.4 1607.91
   251.9 1610.57   264.3 1614.34     279 1616.76   321.8 1616.06   348.5 1617.29
   373.6 1617.24   385.3  1618.4   408.4 1617.82   422.3    1619   486.8 1621.03
   519.1 1620.89   537.5 1622.24   546.7 1625.22   558.3 1624.82   569.8 1626.71
   597.5 1628.26   618.6 1632.11   629.7 1632.66   638.9 1634.73   651.6 1634.88
#Mann= 3 ,-1,0
       0      .1       0  169.31    .045       0   251.9      .1       0
Bank Sta=169.31,251.9
XS Rating Curve= 0 ,0
Exp/Cntr(USF)=0,0
Exp/Cntr=0.3,0.1

Type RM Length L Ch R = 1 ,52846   ,194.7,199.9,205
XS GIS Cut Line= 4
2164509.99645948660649.6862977442164582.92742362660818.579056795
2164817.07420321660947.1678619822164905.35905453 661085.35284666
#Sta/Elev= 30
       0  1652.7    16.9 1650.52    22.6 1648.44    34.3 1642.09    38.7 1640.91
    64.8 1636.92    77.9 1636.21   107.8 1632.32   143.2 1622.07   177.8 1618.78
     231 1611.78   248.7 1610.84   257.5 1609.23   266.3 1606.08   281.8 1605.84
   290.4 1606.27   301.1 1609.21   313.5 1611.91   345.1 1614.17   354.2 1614.52
   384.2 1613.45   413.6 1614.71   454.8 1618.33   501.1 1624.22   524.7 1626.47
   535.9 1632.14   553.2 1638.41     562 1647.15   565.8 1649.16   615.1 1664.55
#Mann= 5 ,-1,0
       0      .1       0   257.5    .045       0   301.1      .1       0
  433.97     .06       0   501.1      .1       0
Bank Sta=257.5,301.1
XS Rating Curve= 0 ,0
Exp/Cntr(USF)=0,0
Exp/Cntr=0.3,0.1

Type RM Length L Ch R = 1 ,52646   ,512.5,561.9,552.5
XS GIS Cut Line= 3
2164473.36559866660746.9140788982164496.25453075 660974.24195627
 2164796.7823048661241.144499928
#Sta/Elev= 30
       0 1640.05    30.4 1634.19    82.7  1626.5    94.7 1622.92   106.8 1617.16
   114.8 1615.91   126.9 1615.92   134.9 1614.01     147 1613.47   233.3 1614.53
   255.1 1613.02   276.5 1609.32  299.651608.366   321.2 1605.69   332.5 1606.02
  346.231608.365   360.8 1611.78   383.5 1609.84   389.2 1610.72   399.6 1614.77
   410.3  1615.8   425.7 1623.44   437.3 1627.14   457.2 1632.71   469.1  1634.7
   485.2 1640.55     522 1647.71   560.1 1658.34   610.2  1673.3   630.4 1682.17
#Mann= 5 ,-1,0
       0      .1       0  299.65    .045       0  346.23      .1       0
  398.48     .06       0  508.48      .1       0
Bank Sta=299.65,346.23
XS Rating Curve= 0 ,0
Exp/Cntr=0.3,0.1