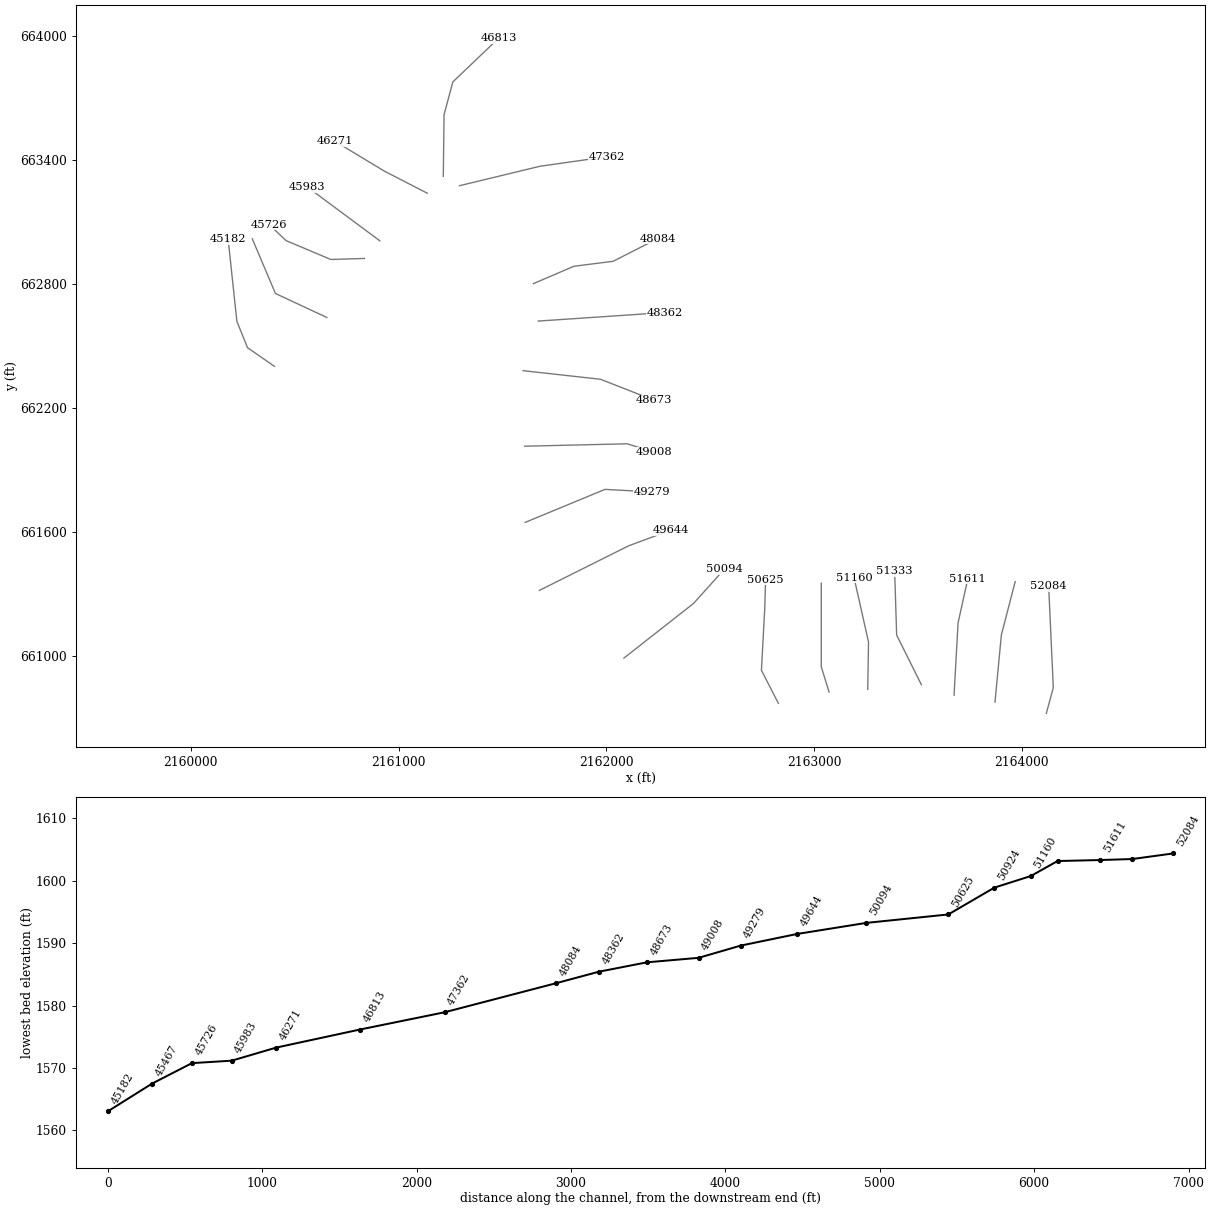
HEC-RAS study LIKANARV.prj: LIKANARV

--- LIKANARV.g01 (geometry) --- (continued)

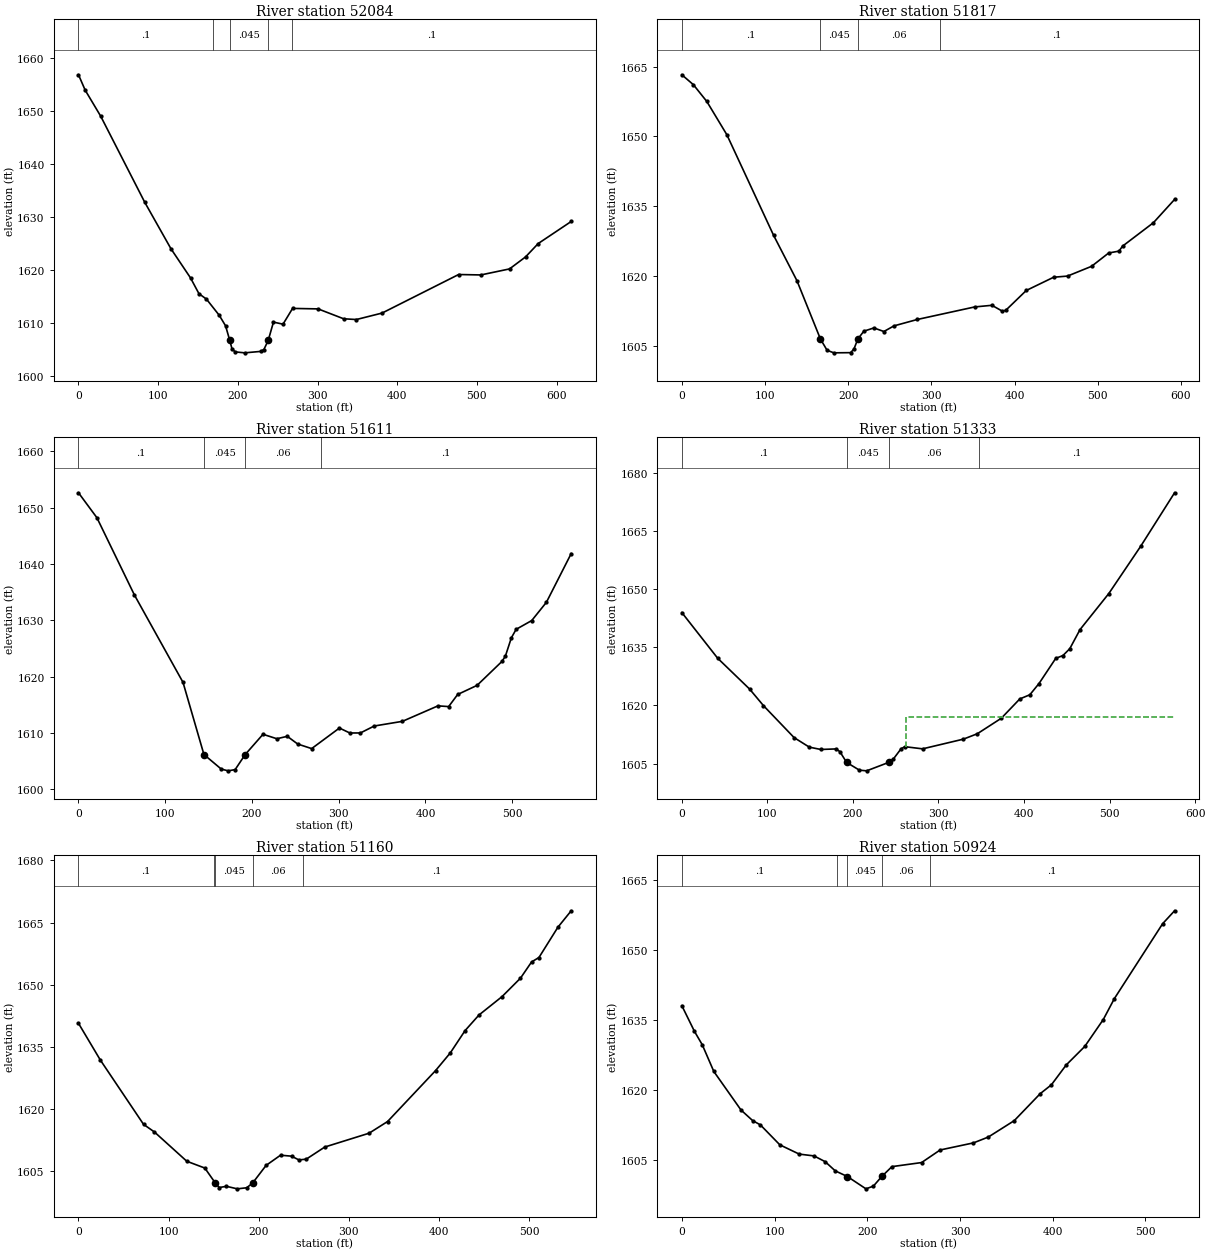
Type RM Length L Ch R = 1 ,52084   ,268,266.9,260.4
XS GIS Cut Line= 3
2164118.19299125660725.100956104 2164151.8507566 660849.09387283
2164129.51982893661338.489585533
#Sta/Elev= 30
       0 1656.92     8.4 1654.01    27.8 1649.11    83.2  1632.8   116.1 1624.01
   140.6 1618.51   151.2 1615.52   160.6  1614.5   176.6 1611.45   184.6 1609.45
  189.841606.697   192.6 1605.13   196.6 1604.52   208.6 1604.34   228.7 1604.61
   232.7 1604.97  238.131606.695   244.7 1610.15   256.7 1609.76   268.7 1612.74
   300.7 1612.65   332.8 1610.78   348.8 1610.64     381 1611.86   477.1 1619.15
     505 1619.07     541 1620.21   561.1 1622.48     577 1625.01   618.4 1629.18
#Mann= 5 ,-1,0
       0      .1       0  168.48     .06       0  189.84    .045       0
  238.13     .06       0  268.48      .1       0
Bank Sta=189.84,238.13
XS Rating Curve= 0 ,0
Exp/Cntr=0.3,0.1

Type RM Length L Ch R = 1 ,51817   ,205.2,206,206.9
XS GIS Cut Line= 3
2163871.07645805660779.324484324 2163901.8332214661103.913272181
 2163968.4017272661361.818430952
#Sta/Elev= 30
       0 1663.28    13.9 1661.14      30 1657.54    54.1 1650.38   110.3 1628.73
   138.4 1618.96   166.6 1606.42   174.6 1603.99   182.7 1603.44   202.8 1603.48
   206.8 1604.21  211.63 1606.43   218.8  1608.1   230.9  1608.8   242.9 1608.03
     255 1609.24   283.1 1610.62   352.1 1613.32   372.8 1613.67   385.2 1612.42
   389.3 1612.57   414.1 1616.86     447 1619.71   463.7 1619.96   492.6 1622.06
   513.2 1624.93   525.6 1625.33   529.8 1626.39     567 1631.45   592.4 1636.45
#Mann= 4 ,-1,0
       0      .1       0   166.6    .045       0  211.63     .06       0
     310      .1       0
Bank Sta=166.6,211.63
XS Rating Curve= 0 ,0
Exp/Cntr=0.3,0.1

Type RM Length L Ch R = 1 ,51611   ,265.9,278,290.8
XS GIS Cut Line= 3
2163674.16922577  660812.82134912163693.36158475661162.122282593
2163740.38286426661375.157467305
#Sta/Elev= 30
       0 1652.66    21.2 1648.24    64.5  1634.5   120.5 1618.99   144.6 1606.18
   164.6 1603.59   172.6 1603.28   180.6  1603.5   192.1 1606.16   212.7 1609.77
   228.7 1608.98   240.7 1609.41   252.7 1608.04   268.8 1607.23   300.8 1610.88
   312.8    1610     325 1610.01   340.9 1611.24   373.4 1612.07   414.4 1614.82
   426.7 1614.69   437.1 1616.84   459.5 1618.46   488.1  1622.7   492.1 1623.64
     499  1626.9   504.5 1628.41   522.5 1629.97   539.4 1633.21     568 1641.87
#Mann= 4 ,-1,0
       0      .1       0   144.6    .045       0   192.1     .06       0
     280      .1       0
Bank Sta=144.6,192.1
XS Rating Curve= 0 ,0
Exp/Cntr(USF)=0,0
Exp/Cntr=0.3,0.1

Type RM Length L Ch R = 1 ,51333   ,181,173.1,159.5
XS GIS Cut Line= 3
2163516.79188211660863.6811004052163397.79925641661103.585587694
2163388.20307692661411.622949373
#Sta/Elev= 30
       0 1643.92    41.9 1632.14    79.2  1624.2    95.4 1619.93   131.2 1611.69
     149 1609.23   162.4 1608.63   180.3 1608.77   184.7 1608.08   192.6  1605.3
   207.5  1603.3     216 1603.12     242 1605.31   247.2 1606.15   256.2 1608.79
   260.6 1609.35   281.4 1608.79   329.1 1611.29   345.4 1612.68   373.4 1616.67
   395.1 1621.66   406.8 1622.73   417.5 1625.62   437.1 1632.12   445.5 1632.84
   453.5 1634.61   465.5 1639.54   499.1 1648.82   536.3 1660.98     576  1674.8
#Mann= 4 ,-1,0
       0      .1       0   192.6    .045       0     242     .06       0
  347.79      .1       0
#XS Ineff= 2 , 0
                          261.63         1616.98
Permanent Ineff=
       F       F
Bank Sta=192.6,242
XS Rating Curve= 0 ,0
Exp/Cntr(USF)=0,0
Exp/Cntr=0.3,0.1

Type RM Length L Ch R = 1 ,51160   ,230.8,235.6,231.3
XS GIS Cut Line= 3
2163258.61904608660841.0127236412163262.38975441661069.786355258
2163192.96311186661380.063701765
#Sta/Elev= 30
       0 1640.68    24.2 1631.83    72.2 1616.29    84.3 1614.44   120.2 1607.38
   140.2 1605.74  151.851602.124   156.2 1601.04   164.2 1601.33   176.2 1600.72
   186.7 1600.98  193.261602.126   208.2 1606.38   224.2 1608.84   236.4 1608.61
   244.6  1607.7   252.8 1607.89   273.3 1610.81   322.5 1614.15     343 1616.97
   396.2 1629.25   412.6 1633.53     429 1638.92   444.5  1642.7     470 1647.12
   490.5 1651.58   502.8 1655.49     511 1656.57     532 1663.87   546.8 1667.85
#Mann= 5 ,-1,0
       0      .1       0     150     .06       0  151.85    .045       0
  193.26     .06       0   248.8      .1       0
Bank Sta=151.85,193.26
XS Rating Curve= 0 ,0
Exp/Cntr=0.3,0.1

Type RM Length L Ch R = 1 ,50924   ,295.2,299,291.3
XS GIS Cut Line= 3
2163072.48877165660828.1752362862163035.06367163660950.046715829
2163035.06367163661354.045872424
#Sta/Elev= 30
       0 1638.04    13.6 1632.55      22 1629.69    34.5 1623.97    63.8 1615.73
    76.4 1613.46    84.7 1612.55   105.7 1608.28   126.6  1606.3   142.6 1605.91
   154.6 1604.68   165.5 1602.71   178.6  1601.5   198.6 1598.87   206.6 1599.45
   215.7 1601.52   226.6 1603.62   258.6 1604.49   278.6 1607.18   314.6  1608.7
   330.6 1609.95   358.6 1613.46   386.6 1619.23   398.6 1621.11   414.6 1625.36
   434.6 1629.32   454.6 1635.08   466.6 1639.57   518.6 1655.57   531.5 1658.34
#Mann= 5 ,-1,0
       0      .1       0  167.49     .06       0   178.6    .045       0
   215.7     .06       0  267.49      .1       0
Bank Sta=178.6,215.7
XS Rating Curve= 0 ,0
Exp/Cntr(USF)=0,0
Exp/Cntr=0.3,0.1

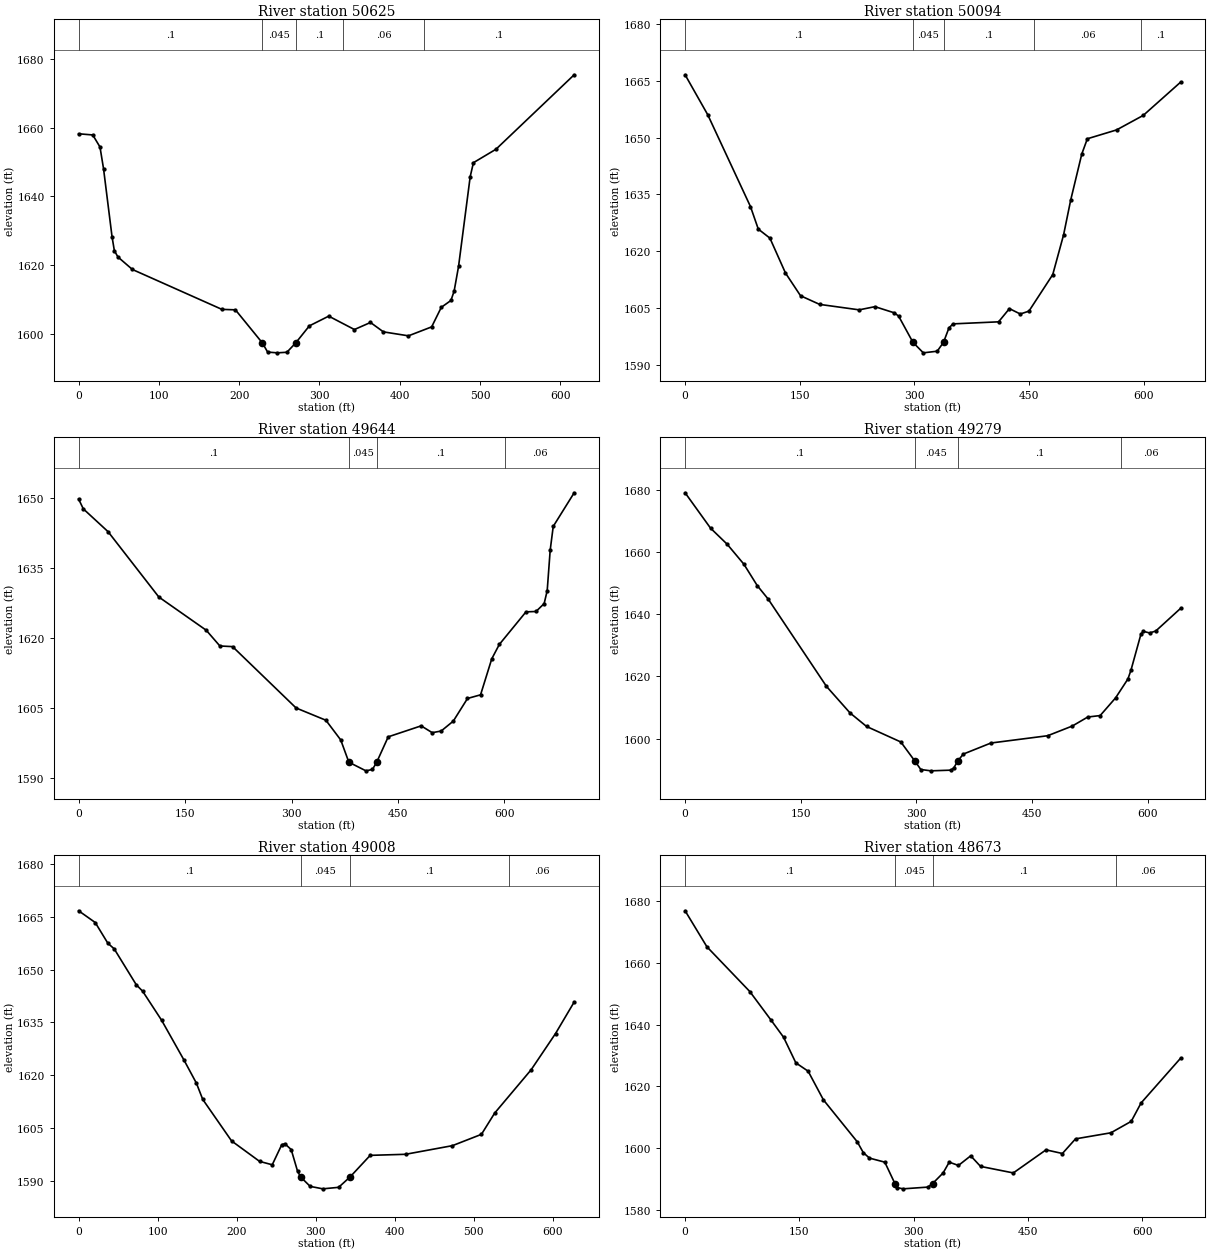
Type RM Length L Ch R = 1 ,50625   ,526.8,531.5,482.8
XS GIS Cut Line= 4
2162828.53108779660773.5290723352162746.88568679660933.483129523
2162762.87407904661229.7160175012162766.84114044661370.637995625
#Sta/Elev= 30
       0  1658.2    17.6 1657.86    26.6 1654.36      31  1648.1    41.6 1628.32
    44.5 1624.24      49  1622.4      67 1618.78   178.4  1607.2   195.3 1607.06
  228.961597.416   235.4 1594.79   247.4 1594.57   259.4 1594.74  270.251597.417
   287.4 1602.41   311.5 1605.23   343.5 1601.34   363.5 1603.39   379.6 1600.66
   410.8 1599.51   439.7 1602.11   451.7 1607.79   463.7 1609.78   467.7 1612.51
   473.2 1619.69   487.7 1645.75   491.7  1649.8   519.8 1653.71   617.2 1675.34
#Mann= 5 ,-1,0
       0      .1       0  228.96    .045       0  270.25      .1       0
  329.59     .06       0  429.59      .1       0
Bank Sta=228.96,270.25
XS Rating Curve= 0 ,0
Exp/Cntr=0.3,0.1

Type RM Length L Ch R = 1 ,50094   ,448.9,449.9,442.9
XS GIS Cut Line= 3
2162084.96234042660992.175840038 2162420.4651645661256.577717078
 2162568.0937566661421.652287297
#Sta/Elev= 30
       0 1666.57    29.6 1656.04    85.6 1631.79    95.8 1625.86     111 1623.48
   131.4 1614.27   151.1 1608.28   176.1    1606   227.8 1604.56   248.5  1605.4
     274 1603.76   279.5  1602.9  298.22 1595.99   311.8 1593.22     330 1593.65
  338.231595.992   345.3 1599.77   350.6 1600.86   410.3  1601.4   424.5 1604.88
   438.7 1603.47     450 1604.21   481.2 1613.86   495.4 1624.35   504.7 1633.52
   519.2 1645.66   526.5 1649.69   564.7 1652.02   599.7 1655.86   648.6 1664.63
#Mann= 5 ,-1,0
       0      .1       0  298.22    .045       0  338.23      .1       0
  457.17     .06       0  597.17      .1       0
Bank Sta=298.22,338.23
XS Rating Curve= 0 ,0
Exp/Cntr=0.3,0.1

Type RM Length L Ch R = 1 ,49644   ,349.4,364.5,349
XS GIS Cut Line= 3
     2161678.285      661319.4332162108.27747586661535.038885956
2162311.79520693661610.756399189
#Sta/Elev= 30
       0 1649.67     6.6 1647.58    41.5 1642.69     113 1628.69   179.8 1621.57
     199  1618.2   216.9 1618.06   306.4 1604.91   348.4 1602.28   369.3 1598.06
  380.721593.293   404.8 1591.44     414 1591.74  419.981593.292   436.2 1598.73
   482.6 1601.08   498.2 1599.62   510.8 1599.97   527.9  1602.1   547.9 1606.95
   566.3 1607.73   582.1 1615.45   592.7 1618.52   630.3 1625.51   644.4 1625.59
   655.9 1627.28   660.2 1630.06   664.4 1638.72   668.7 1643.83   698.2 1651.03
#Mann= 4 ,-1,0
       0      .1       0  380.72    .045       0  419.98      .1       0
  601.02     .06       0
Bank Sta=380.72,419.98
XS Rating Curve= 0 ,0
Exp/Cntr=0.3,0.1

Type RM Length L Ch R = 1 ,49279   ,271.6,271.7,252.3
XS GIS Cut Line= 3
2161609.72557276 661647.873704452161993.83071341661807.470547165
 2162220.4846486661795.168454574
#Sta/Elev= 30
       0 1679.22      33 1667.82    54.6 1662.63    76.3 1656.19    93.6  1649.3
   107.7 1644.98   183.4 1616.81     214 1608.24   235.4 1603.89   279.9 1598.88
  298.37 1592.64   305.8 1590.01   318.9 1589.58   344.8  1589.8   348.7 1590.54
   353.5 1592.68   360.9 1594.98   396.8 1598.55   470.4  1600.9   502.4 1604.03
   522.4 1606.93   538.5  1607.4   558.5  1613.1   574.5 1619.19   578.5 1622.06
   591.3 1633.56   594.5 1634.56   602.6 1634.03   610.6 1634.65   642.9 1641.97
#Mann= 4 ,-1,0
       0      .1       0  298.37    .045       0   353.5      .1       0
  565.94     .06       0
Bank Sta=298.37,353.5
XS Rating Curve= 0 ,0
Exp/Cntr=0.3,0.1

Type RM Length L Ch R = 1 ,49008   ,331.7,334.9,328.7
XS GIS Cut Line= 3
2161607.15216329662016.182257341 2162101.3554071662027.697672731
2162228.02497639661987.393718867
#Sta/Elev= 30
       0 1666.77      21 1663.43      37 1657.53      45 1655.94      73  1645.7
      81 1643.89   105.1 1635.59   133.1 1624.39   149.1  1617.7   157.1 1613.09
   193.6 1601.27   229.1 1595.44   245.1 1594.48   257.1 1600.18   261.1 1600.46
   269.1  1598.8   277.1 1592.67   281.1 1590.99   293.1 1588.33   309.1 1587.63
   329.1 1588.06   343.6 1591.01   369.1 1597.16   413.8 1597.46   473.2 1599.92
   509.9 1603.14   526.7  1609.2   572.9 1621.54   603.7 1631.83   627.3  1640.8
#Mann= 4 ,-1,0
       0      .1       0   281.1    .045       0   343.6      .1       0
  544.34     .06       0
Bank Sta=281.1,343.6
XS Rating Curve= 0 ,0
Exp/Cntr(USF)=0,0
Exp/Cntr=0.3,0.1

Type RM Length L Ch R = 1 ,48673   ,298.8,311.1,310.1
XS GIS Cut Line= 3
2161599.78570514662381.0988845932161972.46130665662339.527620904
2162228.49479377662238.750630003
#Sta/Elev= 30
       0 1676.77    28.6 1665.14    84.9 1650.67   113.1 1641.32   129.2  1635.9
   145.3 1627.62   161.4 1624.93   181.5 1615.65   225.8 1602.13   233.8 1598.61
   241.9 1596.84     262 1595.53  275.281588.603   278.1 1587.32   285.9 1586.91
   318.4 1587.47  324.631588.602   338.5 1592.05   346.5 1595.53   358.6 1594.47
   374.7 1597.58   387.6 1594.16   430.6 1592.05   473.5 1599.51     495 1598.33
   512.2 1603.06   558.6 1605.02   585.3 1608.72   598.2 1614.66   650.1 1629.14
#Mann= 4 ,-1,0
       0      .1       0  275.28    .045       0  324.63      .1       0
  564.99     .06       0
Bank Sta=275.28,324.63
XS Rating Curve= 0 ,0
Exp/Cntr=0.3,0.1

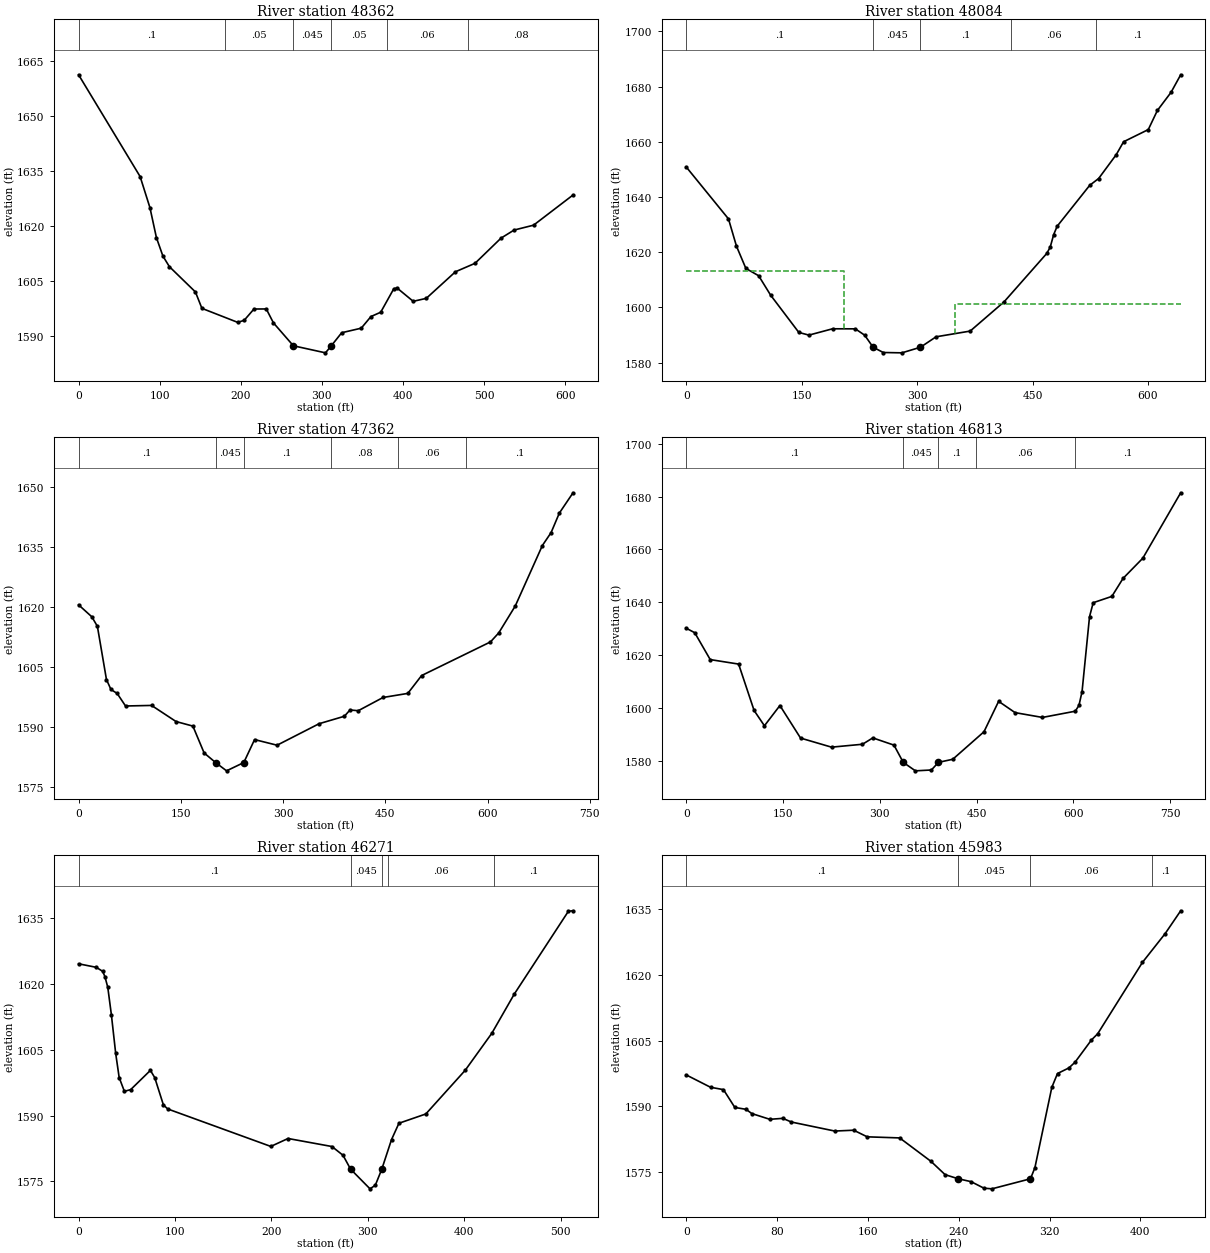
Type RM Length L Ch R = 1 ,48362   ,264.2,277.2,270.7
XS GIS Cut Line= 2
2161672.40618383 662620.741565312162280.80396359662662.005137123
#Sta/Elev= 30
       0  1661.3    75.9 1633.52      88 1625.04      96 1616.85     104 1611.82
     112 1608.93   144.1 1602.03   152.1 1597.55   196.2 1593.73   204.2 1594.28
   216.3 1597.37   231.5 1597.39   240.3 1593.59   264.91587.337   304.5 1585.41
   311.8 1587.37   324.5  1590.9   348.6 1592.14   360.6 1595.32   372.6 1596.49
   388.7 1602.89   392.7 1603.12   412.7 1599.47   428.8 1600.28   464.8 1607.54
   488.9 1609.84     521 1616.72   537.1 1618.92   561.1 1620.25   609.8 1628.49
#Mann= 6 ,-1,0
       0      .1       0     180     .05       0   264.9    .045       0
   311.8     .05       0     380     .06       0     480     .08       0
Bank Sta=264.9,311.8
XS Rating Curve= 0 ,0
Exp/Cntr(USF)=0,0
Exp/Cntr=0.3,0.1

Type RM Length L Ch R = 1 ,48084   ,685,722.1,711.1
XS GIS Cut Line= 4
 2161649.7545021 662801.823662172161844.28373027662885.528297844
 2162033.0652502 662909.678976422162247.09680286663018.860259493
#Sta/Elev= 30
       0 1650.89    54.9 1632.08    65.3 1622.19    77.5 1614.14    94.1 1611.49
   109.7 1604.44   146.3 1590.96   159.4 1589.99   190.1 1592.28   219.7 1592.26
   231.8 1589.97  242.81  1585.6     256 1583.69   280.2 1583.57  304.311585.599
   324.6 1589.38   368.9 1591.45     413 1602.06   468.4 1619.57   472.9 1621.87
   477.4 1626.41   481.9 1629.42   524.2 1644.24   535.8 1646.71   558.7 1655.36
   568.2 1660.02   600.3 1664.43   612.1 1671.35   629.9 1677.93   642.4 1684.28
#Mann= 5 ,-1,0
       0      .1       0  242.81    .045       0  304.31      .1       0
  422.09     .06       0  532.09      .1       0
#XS Ineff= 2 , 0
          204.82 1613.37  349.07         1601.31
Permanent Ineff=
       F       F
Bank Sta=242.81,304.31
XS Rating Curve= 0 ,0
Exp/Cntr=0.3,0.1

Type RM Length L Ch R = 1 ,47362   ,514.7,549.8,559.3
XS GIS Cut Line= 3
2161293.20632604663274.8083773962161680.86539259663368.788207233
2162004.14618365663414.952730416
#Sta/Elev= 30
       0 1620.44    19.5 1617.44    27.6 1615.06    40.9 1601.76    47.5 1599.27
    56.6 1598.28    68.9 1595.14   107.1 1595.28     143 1591.25   167.7 1590.11
   184.2 1583.39  201.05 1580.99   217.1 1578.92  242.371580.989   258.2 1586.74
   291.2 1585.33   352.9 1590.71   389.9 1592.57   398.2 1594.14   410.3 1593.96
   446.7 1597.27     483 1598.29   503.2 1602.75   604.3 1611.17   616.4 1613.42
   640.6 1620.14   680.4 1635.28   693.2 1638.51   705.3 1643.39   725.4 1648.47
#Mann= 6 ,-1,0
       0      .1       0  201.05    .045       0  242.37      .1       0
     370     .08       0  468.89     .06       0  568.89      .1       0
Bank Sta=201.05,242.37
XS Rating Curve= 0 ,0
Exp/Cntr=0.3,0.1

Type RM Length L Ch R = 1 ,46813   ,507.6,542.1,570.9
XS GIS Cut Line= 4
2161215.61657624663319.956525678 2161219.2860774663618.347183233
  2161261.539877663776.2498828932161481.38485761663986.992601519
#Sta/Elev= 30
       0 1630.17    13.2 1628.47    37.2 1618.29    81.2 1616.59   105.2 1599.01
   121.2 1593.22   145.2 1600.89   177.2 1588.56   225.2 1585.12   273.2 1586.22
   289.2 1588.63     322 1585.89  336.361579.362   355.2 1576.15     380 1576.47
  390.911579.363   413.1 1580.53   461.5 1590.95   484.2 1602.48   509.7  1598.2
   552.1 1596.38     603 1598.74   608.7 1600.93   613.5 1606.13   625.1 1634.56
   630.8 1639.84   659.7 1642.23   677.1 1649.06   707.7  1656.7   766.4 1681.48
#Mann= 5 ,-1,0
       0      .1       0  336.36    .045       0  390.91      .1       0
  448.41     .06       0  601.87      .1       0
Bank Sta=336.36,390.91
XS Rating Curve= 0 ,0
Exp/Cntr=0.3,0.1

Type RM Length L Ch R = 1 ,46271   ,282.6,287.7,284.8
XS GIS Cut Line= 3
2161138.36231992663238.587898965 2160932.9932929663344.810198782
2160692.05584649663490.690942265
#Sta/Elev= 30
       0 1624.63    18.4 1623.82      25  1622.9    27.3 1621.72    30.3 1619.25
      34 1613.05    38.5 1604.17    42.1 1598.67    47.5 1595.52      54  1595.9
    74.5  1600.3      79 1598.65      88 1592.41    92.5 1591.49   199.4 1582.94
   217.3 1584.75   262.8 1582.92   274.3 1580.92  282.151577.754   302.3 1573.26
   307.8 1574.08  314.531577.752   324.6 1584.49   332.3 1588.23   360.2 1590.35
     401 1600.31   428.6 1608.75   451.9  1617.7   508.1 1636.63   512.9 1636.73
#Mann= 5 ,-1,0
       0      .1       0  282.15    .045       0  314.53      .1       0
  321.21     .06       0  431.21      .1       0
Bank Sta=282.15,314.53
XS Rating Curve= 0 ,0
Exp/Cntr=0.3,0.1

Type RM Length L Ch R = 1 ,45983   ,246,257.2,259.8
XS GIS Cut Line= 2
 2160910.4695322663008.4272167692160561.16859871 663268.48368099
#Sta/Elev= 30
       0 1597.19    21.4 1594.37    32.8 1593.83    42.8 1589.76    52.7 1589.33
    57.7 1588.37    73.6 1587.05    85.1 1587.27    92.6 1586.43   130.8 1584.37
   147.5 1584.56   159.4 1583.05     188  1582.8   215.6 1577.44     228 1574.41
   239.4 1573.48   250.9 1572.81   262.2 1571.32   269.2 1571.17  303.21 1573.47
   307.1 1576.01     322 1594.35     327 1597.51     337 1598.78   342.4 1600.08
   356.9 1605.17   362.4 1606.59   401.8 1622.89   421.8 1629.46   435.5 1634.68
#Mann= 4 ,-1,0
       0      .1       0   239.4    .045       0  303.21     .06       0
     410      .1       0
Bank Sta=239.4,303.21
XS Rating Curve= 0 ,0
Exp/Cntr(USF)=0,0
Exp/Cntr=0.3,0.1

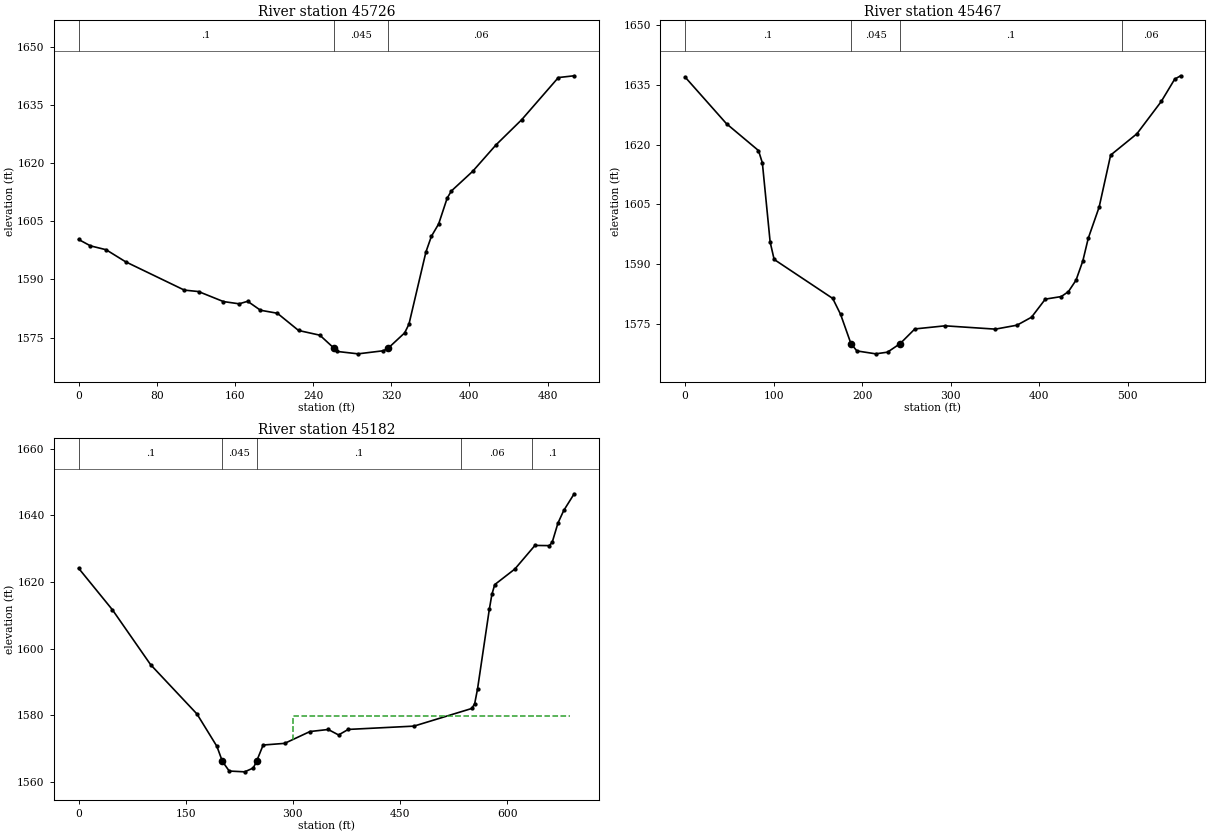
Type RM Length L Ch R = 1 ,45726   ,258.8,258.9,256.6
XS GIS Cut Line= 4
2160836.28304483 662923.355079812160673.94821309662918.496010294
2160458.52052963663009.7227150622160378.32738224663086.249030396
#Sta/Elev= 30
       0 1600.34    12.1 1598.69    28.1 1597.69    48.1 1594.57   108.2 1587.25
   122.7 1586.88   148.2 1584.29   164.3 1583.71     173 1584.36   186.1 1582.05
   203.4 1581.27   225.1 1576.82   246.9  1575.6  261.051572.311   264.2 1571.41
     286 1570.78     312 1571.58  317.121572.312   333.7  1576.2   338.1 1578.45
   355.5 1597.14   361.1 1601.17   368.5 1604.36   377.2 1611.02   381.5 1612.87
   403.3 1617.95   427.2 1624.79   453.5  1631.3     491 1642.19   507.2 1642.65
#Mann= 3 ,-1,0
       0      .1       0  261.05    .045       0  317.12     .06       0
Bank Sta=261.05,317.12
XS Rating Curve= 0 ,0
Exp/Cntr=0.3,0.1

Type RM Length L Ch R = 1 ,45467   ,300.1,285.2,260.6
XS GIS Cut Line= 3
2160655.21115772662638.0146883942160407.62972684662754.128460242
2160296.31404474 663018.02339626
#Sta/Elev= 30
       0 1636.96    46.8 1625.24    82.9 1618.52    87.3 1615.42    96.1 1595.55
   100.6 1591.19   166.8  1581.4   175.7  1577.4  187.35 1570.08   194.1 1568.23
   215.4  1567.5   228.7 1567.92     243 1570.07   259.6 1573.75   293.7 1574.53
   350.6  1573.7     375 1574.69   391.4 1576.69     407 1581.23     425 1581.87
   433.1 1583.11   441.7 1585.98   449.4 1590.82   455.5 1596.49   467.8 1604.31
   480.8 1617.37   510.5 1622.73     538 1630.83   553.2 1636.44   559.9 1637.28
#Mann= 4 ,-1,0
       0      .1       0  187.35    .045       0     243      .1       0
  493.46     .06       0
Bank Sta=187.35,243
XS Rating Curve= 0 ,0
Exp/Cntr(USF)=0,0
Exp/Cntr=0.3,0.1

Type RM Length L Ch R = 1 ,45182   ,528.5,538.1,504.8
XS GIS Cut Line= 4
2160402.97443362 662402.016193322160273.26648181662492.087729048
2160222.07869305662619.3077836182160180.03567274663015.689113084
#Sta/Elev= 30
       0 1624.13    47.4 1611.65   100.8 1595.21   165.7 1580.42   193.6 1570.71
   201.2 1566.23   210.8 1563.32   232.4 1563.08   244.5 1564.23  249.01  1566.2
   258.3 1571.12   288.4 1571.62   323.9 1575.17   349.4 1575.78   363.9 1574.14
   377.4  1575.8   469.4 1576.79   550.3 1582.08   554.4  1583.5   558.4 1587.91
   574.9  1611.8   578.5 1616.28   582.5 1619.23   610.7 1623.91   638.8 1630.98
   658.9 1630.92     663 1631.96     671 1637.68   679.1 1641.46   693.7 1646.47
#Mann= 5 ,-1,0
       0      .1       0   201.2    .045       0  249.01      .1       0
  535.05     .06       0  635.05      .1       0
#XS Ineff= 1 ,-1
  299.68   687.5 1579.91
Permanent Ineff=
       F
Bank Sta=201.2,249.01
XS Rating Curve= 0 ,0
Exp/Cntr=0.3,0.1