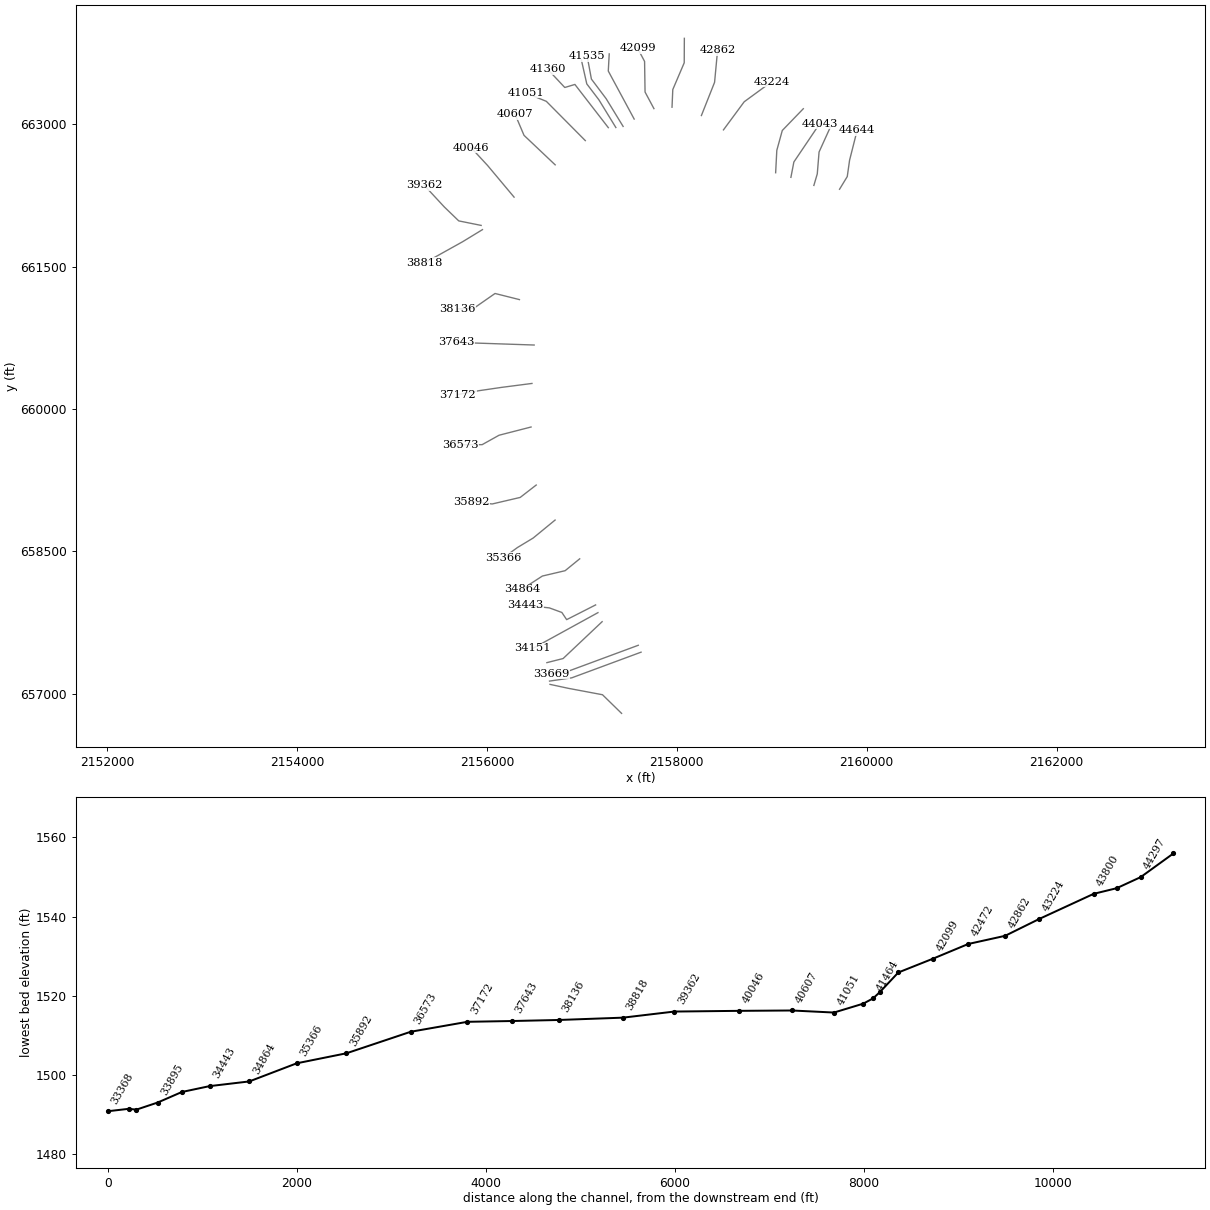
HEC-RAS study LIKANARV.prj: LIKANARV

--- LIKANARV.g01 (geometry) --- (continued)

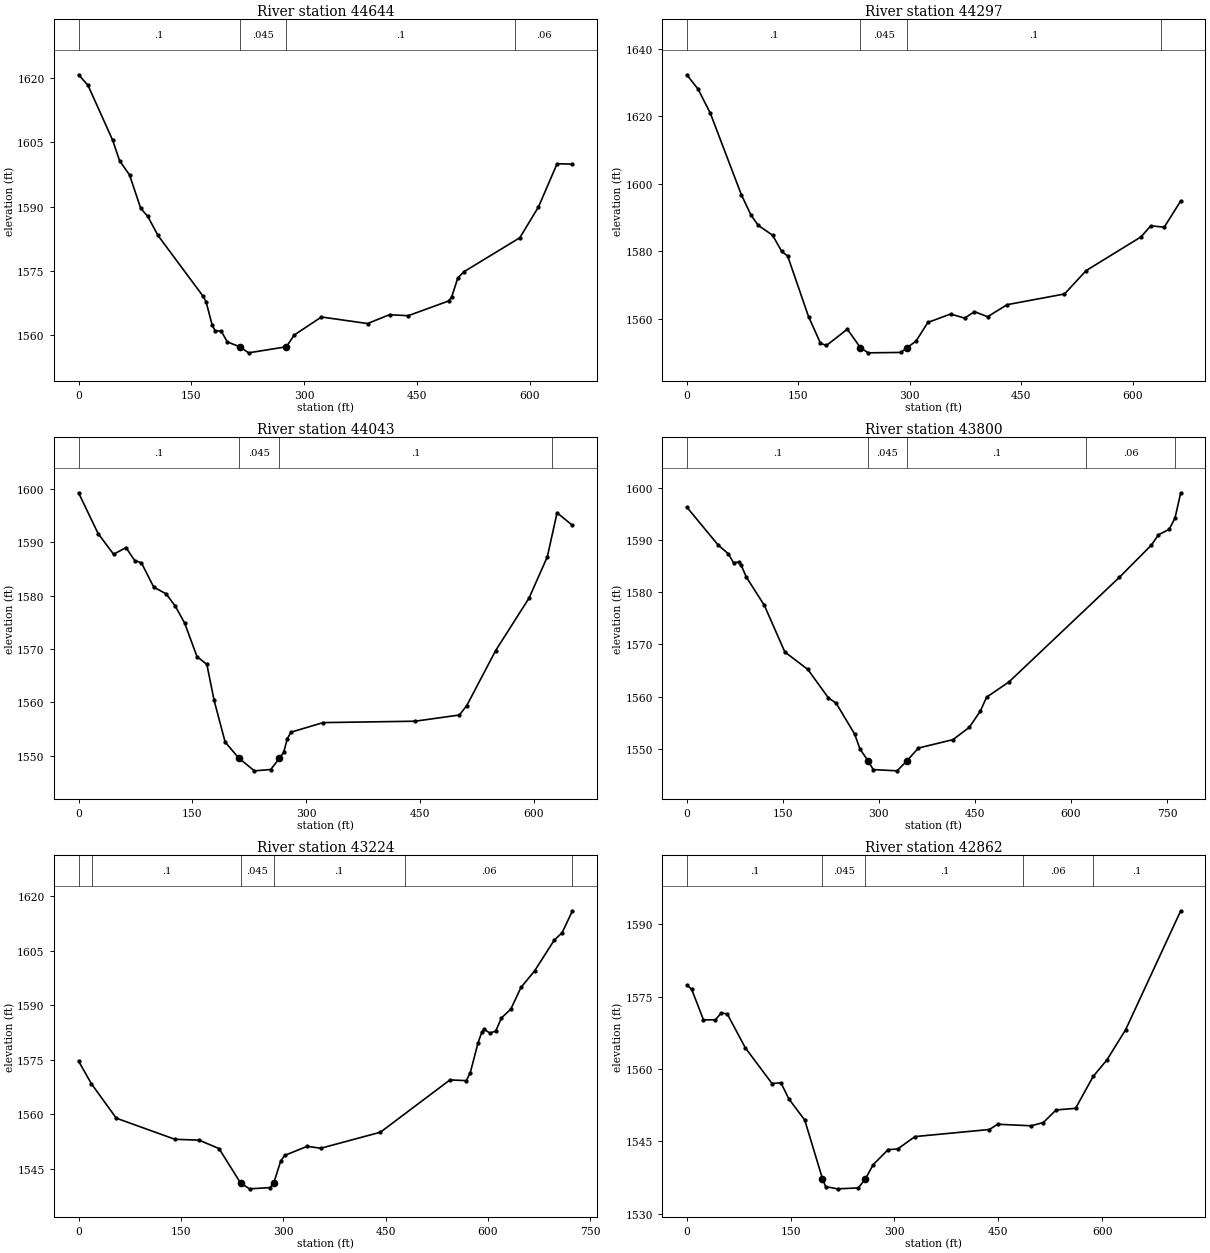
Type RM Length L Ch R = 1 ,44644   ,330.2,346.7,336.2
XS GIS Cut Line= 4
2159713.66885881662314.5128345322159794.92206267662447.943002655
2159819.35293076662620.2143066552159899.52987995662936.973810702
#Sta/Elev= 30
       0 1620.67    12.5 1618.24    45.3 1605.47    54.6 1600.65    67.8 1597.37
    82.7 1589.59    92.1 1587.71   105.6 1583.28   165.6 1569.15   169.6 1567.86
   177.7 1562.45   181.7  1561.1   189.8 1561.01   197.9  1558.5  214.391557.372
   226.2 1555.96  276.481557.371   286.8  1560.1   323.1  1564.3   384.4 1562.78
   413.7 1564.84   438.5  1564.6   492.1 1568.02   496.3 1568.96   504.5 1573.39
   512.7 1574.84     587 1582.75   611.8 1589.92   636.5 1599.96     657 1599.89
#Mann= 4 ,-1,0
       0      .1       0  214.39    .045       0  276.48      .1       0
  580.22     .06       0
Bank Sta=214.39,276.48
XS Rating Curve= 0 ,0
Exp/Cntr=0.3,0.1

Type RM Length L Ch R = 1 ,44297   ,262.9,254.2,235.2
XS GIS Cut Line= 4
2159443.34588534662354.644989208 2159479.1337749662475.903423968
2159498.00261871662706.4824932552159624.82342671662985.915730665
#Sta/Elev= 30
       0 1632.26    15.2 1628.01    31.7 1620.85    73.5 1596.72    86.4 1590.72
    96.1 1587.71   115.4 1584.78   127.7 1579.99   135.7 1578.63   163.8  1560.7
   179.9 1552.81   187.9 1552.15     216 1556.97  233.72 1551.48   244.1 1549.97
   288.2 1550.09  296.05 1551.48   308.3  1553.4   324.4 1558.97   354.9 1561.45
   373.9 1560.25   387.1 1562.16   404.7 1560.65     431 1564.22   508.2 1567.39
   537.3  1574.3   611.1 1584.28   624.3 1587.56   642.4 1587.16   664.6 1594.92
#Mann= 4 ,-1,0
       0      .1       0  233.72    .045       0  296.05      .1       0
  637.78     .06       0
Bank Sta=233.72,296.05
XS Rating Curve= 0 ,0
Exp/Cntr=0.3,0.1

Type RM Length L Ch R = 1 ,44043   ,234.4,243,253.9
XS GIS Cut Line= 3
2159201.60755713662439.8451572642159232.69917869662601.348858107
2159504.75086727663004.676282137
#Sta/Elev= 30
       0 1599.28    25.8 1591.63    46.2 1587.76    62.5    1589    74.1 1586.57
    82.8 1586.17    99.1  1581.6   115.4 1580.34   127.6 1578.02   139.9 1574.85
   156.1 1568.58   169.1 1567.13   178.7 1560.36   193.2 1552.57  211.21 1549.56
   231.8 1547.17   253.3 1547.42   264.8 1549.53   270.4 1550.64   275.2 1553.22
   280.1 1554.42   322.4 1556.21   443.5 1556.47     502 1557.63   511.7 1559.41
   549.8 1569.72   593.7 1579.53   617.8 1587.26   630.7 1595.53     651 1593.17
#Mann= 4 ,-1,0
       0      .1       0  211.21    .045       0   264.8      .1       0
  624.47     .06       0
Bank Sta=211.21,264.8
XS Rating Curve= 0 ,0
Exp/Cntr(USF)=0,0
Exp/Cntr=0.3,0.1

Type RM Length L Ch R = 1 ,43800   ,582.1,575.5,555.3
XS GIS Cut Line= 4
2159040.80603192662488.2915705932159053.06723741662723.668616007
2159110.71410583662933.1385489662159331.93742671663162.254455935
#Sta/Elev= 30
       0 1596.31      49 1589.04      65 1587.34      73 1585.64      81 1585.81
      85 1585.16      93 1582.89   121.1 1577.48   153.1 1568.54   189.1 1565.18
   221.2 1559.73   233.2 1558.73   262.2 1552.78   270.5 1549.92   282.9  1547.7
   291.2 1545.99   328.5 1545.75     3441547.702   361.7 1550.12   415.7 1551.73
   441.2 1554.09   458.6 1557.24   468.2 1559.87   503.1 1562.79   675.4 1582.83
   725.5 1589.02   736.6    1591   753.3 1592.05   762.4 1594.18   771.4 1599.06
#Mann= 5 ,-1,0
       0      .1       0   282.9    .045       0     344      .1       0
  622.95     .06       0  762.95      .1       0
Bank Sta=282.9,344
XS Rating Curve= 0 ,0
Exp/Cntr=0.3,0.1

Type RM Length L Ch R = 1 ,43224   ,353.9,362,362.6
XS GIS Cut Line= 3
2158491.35898921662939.5972266182158709.74667716 663235.53796268
2158997.03239433663445.632090828
#Sta/Elev= 30
       0 1574.61    18.9 1568.34    55.3 1558.88   141.2 1553.06   176.5 1552.83
   205.8 1550.51  237.511540.984   250.5 1539.41   280.4 1539.75  285.981540.983
   296.3 1547.12   302.1 1548.62     335 1551.13   354.9 1550.59   442.3 1555.01
   544.2 1569.42   568.2 1569.22     574 1571.42   585.4 1579.69   591.1 1582.64
     594 1583.43   602.6 1582.31   611.2 1582.87   619.7  1586.5   633.4 1588.93
   648.3 1594.91   668.4  1599.5     697 1607.93   708.5 1609.96   723.7 1616.02
#Mann= 6 ,-1,0
       0     .06       0      20      .1       0  237.51    .045       0
  285.98      .1       0   477.8     .06       0  723.71      .1       0
Bank Sta=237.51,285.98
XS Rating Curve= 0 ,0
Exp/Cntr=0.3,0.1

Type RM Length L Ch R = 1 ,42862   ,383.8,389.9,381.1
XS GIS Cut Line= 3
2158259.08030665 663090.765949192158397.80941862663440.431029226
2158429.22888804663776.360647931
#Sta/Elev= 30
       0 1577.39     6.9 1576.59    24.1  1570.2    41.3  1570.2    49.9 1571.65
    58.5 1571.42    84.4 1564.43   123.1 1556.99     136 1557.15   147.5 1553.79
   170.4 1549.41  195.98 1537.26   200.5  1535.6   217.8 1535.14   247.9 1535.33
  258.171537.257   269.4 1540.18   290.9 1543.28   304.6  1543.4   329.6 1545.98
   437.2 1547.45   449.2 1548.54   497.5 1548.22     515 1548.89   533.6 1551.51
   561.7 1551.84   587.1 1558.46   606.8 1561.85     634 1568.15   713.6 1592.83
#Mann= 5 ,-1,0
       0      .1       0  195.98    .045       0  258.17      .1       0
  486.18     .06       0  586.18      .1       0
Bank Sta=195.98,258.17
XS Rating Curve= 0 ,0
Exp/Cntr=0.3,0.1

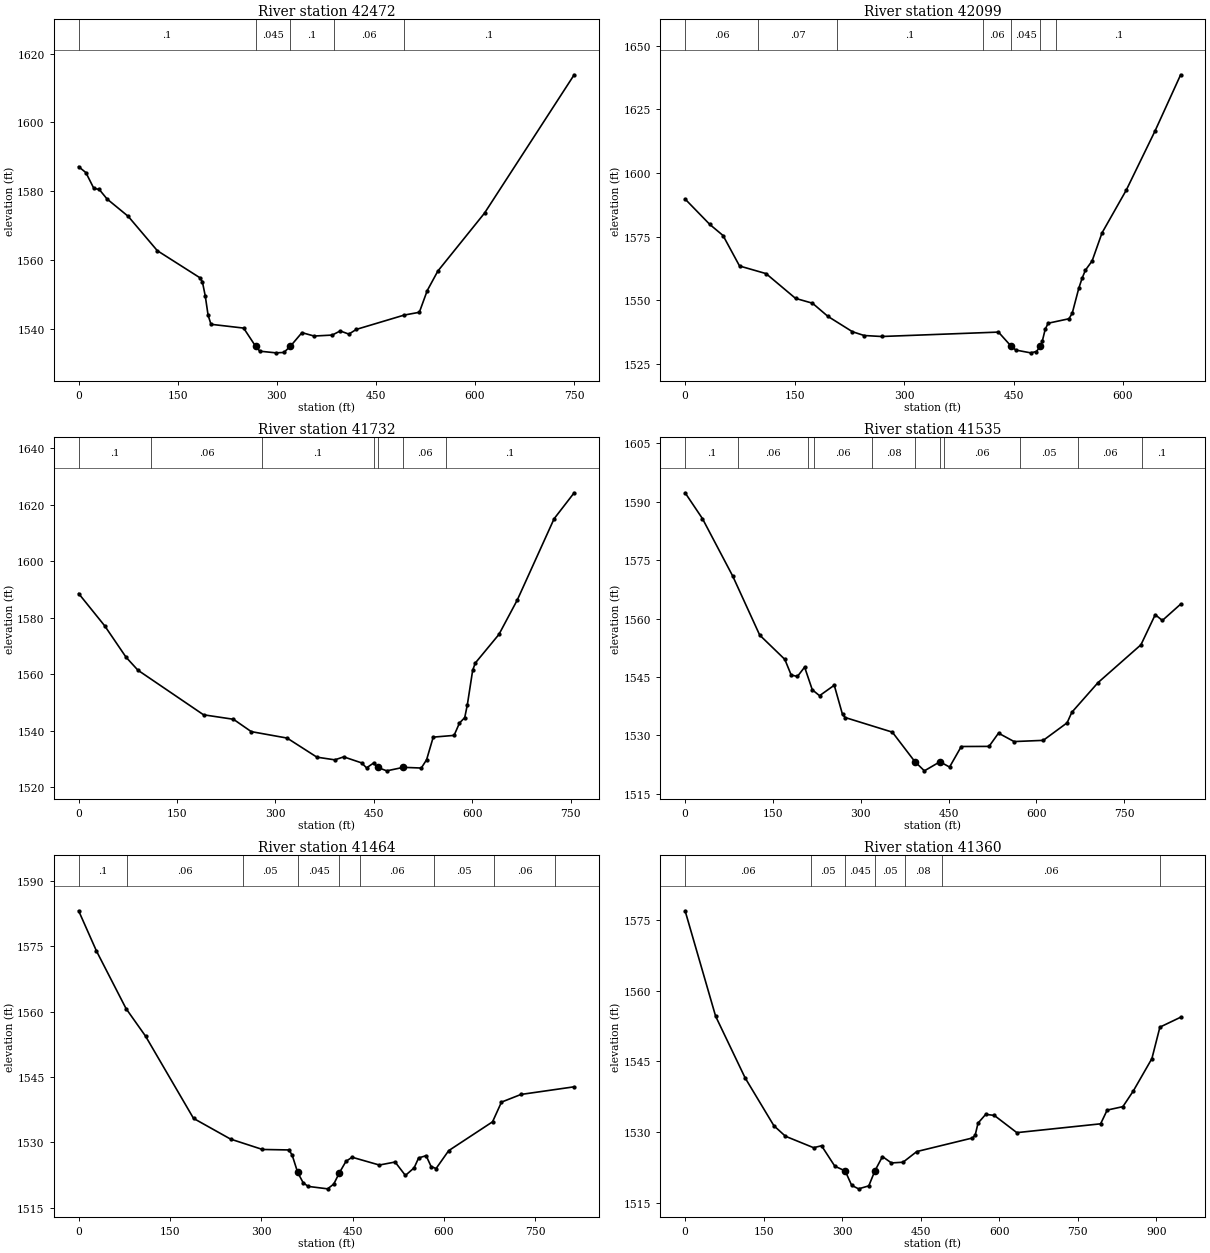
Type RM Length L Ch R = 1 ,42472   ,361.9,373,378.9
XS GIS Cut Line= 4
 2157949.6391812663178.1426506292157957.75790935663364.057983317
2158078.19664523663646.2343758992158079.46797859663903.529641588
#Sta/Elev= 30
       0 1587.16      11 1585.43    23.1 1580.82    31.1 1580.56    43.1 1577.76
    75.1 1572.72   119.1 1562.76   183.2 1554.94   187.3 1553.78   191.7 1549.61
     196    1544   200.4 1541.37   249.8 1540.27  267.88    1535   274.3 1533.56
   298.5 1533.08   310.7 1533.19  320.621534.999   338.1 1538.95   356.4 1537.96
   383.9 1538.24     396 1539.44   409.1 1538.52   420.4 1539.89   492.9 1544.05
   515.8 1544.86   527.8 1551.18   543.8 1556.83   614.5 1573.67   750.2 1613.85
#Mann= 5 ,-1,0
       0      .1       0  267.88    .045       0  320.62      .1       0
  386.09     .06       0   492.9      .1       0
Bank Sta=267.88,320.62
XS Rating Curve= 0 ,0
Exp/Cntr=0.3,0.1

Type RM Length L Ch R = 1 ,42099   ,356.5,367.1,374.9
XS GIS Cut Line= 4
2157759.15954563  663163.36072182157665.68192694663338.071888573
2157660.70340494663660.6253555152157586.53251531663800.288511319
#Sta/Elev= 30
       0  1589.8    33.8 1579.83      52 1575.46    74.6 1563.49   110.9  1560.5
   151.3 1550.77   174.5 1548.87   195.6 1543.71   229.3 1537.66   245.3 1536.18
   269.3 1535.79   429.3 1537.52  446.931531.894   453.3 1530.45   473.3 1529.37
   481.3 1529.88  486.641531.895   489.3 1533.88   493.3 1538.55   497.3    1541
   525.9 1542.76   530.4 1544.95   539.3 1554.68     544 1558.76   548.5 1561.88
   557.6 1565.46   571.2  1576.5   604.4  1593.3   643.7 1616.47   678.9 1638.62
#Mann= 7 ,-1,0
       0     .06       0     100     .07       0  208.15      .1       0
  408.15     .06       0  446.93    .045       0  486.64     .06       0
  508.15      .1       0
Bank Sta=446.93,486.64
XS Rating Curve= 0 ,0
Exp/Cntr=0.3,0.1

Type RM Length L Ch R = 1 ,41732   ,189.9,197.1,194.6
XS GIS Cut Line= 3
2157551.04158111663053.5573909992157278.50241571663559.004102029
2157288.36165843663739.737870082
#Sta/Elev= 30
       0  1588.6    39.8 1577.15    72.3 1566.06    90.4 1561.47   190.4  1545.7
   235.9 1544.12   263.1 1539.75   317.7 1537.47   363.1 1530.72   390.4 1529.77
     404 1530.82   431.3 1528.69   438.8 1526.93   449.5 1528.64   455.5 1527.11
   469.6 1525.88   494.9 1527.12   522.2 1526.87   530.3 1529.81   540.4  1537.8
   572.2 1538.42   580.4  1542.8   588.4  1544.7   592.4 1549.25   600.5 1561.42
   604.4 1563.98   640.5 1574.12   668.6 1586.35   724.6 1615.04   755.2 1624.23
#Mann= 7 ,-1,0
       0      .1       0     110     .06       0     280      .1       0
     450     .06       0   455.5    .045       0   494.9     .06       0
     560      .1       0
Bank Sta=455.5,494.9
XS Rating Curve= 0 ,0
Exp/Cntr=0.3,0.1

Type RM Length L Ch R = 1 ,41535   ,68.7,70.5,75
XS GIS Cut Line= 4
2157434.70163372662975.9503168582157256.06101394663267.802771228
2157100.70125267 663474.658258572157056.05127867663715.922893728
#Sta/Elev= 30
       0 1592.31    29.6 1585.68    81.3 1570.92   127.4 1555.75   170.3 1549.51
   181.1 1545.51   191.8 1545.12   204.1 1547.52   217.2  1541.7   229.6 1540.18
   254.7 1542.87   268.8 1535.36   273.5 1534.57   353.9 1530.82  392.28 1523.26
   408.6 1520.88   435.2 1523.21   451.6 1521.85   471.6 1527.13     519 1527.16
   535.2 1530.56   561.8  1528.4   611.6 1528.71   652.3 1533.21   660.4 1535.92
   705.1 1543.54   778.4 1553.26   802.8 1560.99     815 1559.51   846.2  1563.7
#Mann= 11 ,-1,0
       0      .1       0      90     .06       0     210     .08       0
     220     .06       0     320     .08       0  392.28    .045       0
   435.2     .05       0  442.18     .06       0  572.18     .05       0
  670.88     .06       0  780.88      .1       0
Bank Sta=392.28,435.2
XS Rating Curve= 0 ,0
Exp/Cntr=0.3,0.1

Type RM Length L Ch R = 1 ,41464   ,103.4,104.2,104.3
XS GIS Cut Line= 4
2157358.30653602662964.1991474442157179.66591625663256.051601814
2157052.07498309663423.8577703032156994.65788838663678.365678425
#Sta/Elev= 30
       0  1583.1    29.3 1573.87    77.9 1560.66   109.9 1554.35   188.7 1535.49
   249.5 1530.74   301.9 1528.36   345.5 1528.25   350.8 1527.04   359.8 1523.08
   368.7 1520.75   376.9 1519.89   408.9 1519.33     419 1520.42  428.46 1523.06
   439.1 1525.64   449.1 1526.58   493.9 1524.79   519.8 1525.48   536.7  1522.4
     551 1524.14   558.4 1526.41   570.7 1526.94   578.9 1524.45   587.1 1523.99
   607.8 1528.09   679.8  1534.7   694.5 1539.22   726.6 1540.98   813.9 1542.73
#Mann= 9 ,-1,0
       0      .1       0      80     .06       0     270     .05       0
   359.8    .045       0  428.46     .05       0  462.18     .06       0
  582.99     .05       0  682.99     .06       0  782.99     .07       0
Bank Sta=359.8,428.46
XS Rating Curve= 0 ,0
Exp/Cntr=0.3,0.1

Type RM Length L Ch R = 1 ,41360   ,306.3,309.2,313.4
XS GIS Cut Line= 4
 2157278.8058499662963.0323474042156926.94593521663417.962338114
2156820.32171864663385.9750731432156642.61469101663575.529235939
#Sta/Elev= 30
       0 1576.93    58.3 1554.58   114.6 1541.52   169.6 1531.37   191.6 1529.15
   245.4 1526.72   260.6 1527.13   285.9  1522.8   305.7  1521.8   318.1 1518.74
   331.3    1518   350.8 1518.63  362.32 1521.79   376.9 1524.84     394 1523.49
   416.2 1523.64   442.4  1525.9   548.8 1528.78   553.9 1529.36   559.4 1531.93
   574.1 1533.79   590.5 1533.56   633.5 1529.91   793.5 1531.78     806 1534.69
     836 1535.42   855.8 1538.72   891.4  1545.6   906.7 1552.27   946.3 1554.37
#Mann= 7 ,-1,0
       0     .06       0     240     .05       0   305.7    .045       0
  362.32     .05       0     420     .08       0     490     .06       0
  906.44      .1       0
Bank Sta=305.7,362.32
XS Rating Curve= 0 ,0
Exp/Cntr(USF)=0,0
Exp/Cntr=0.3,0.1

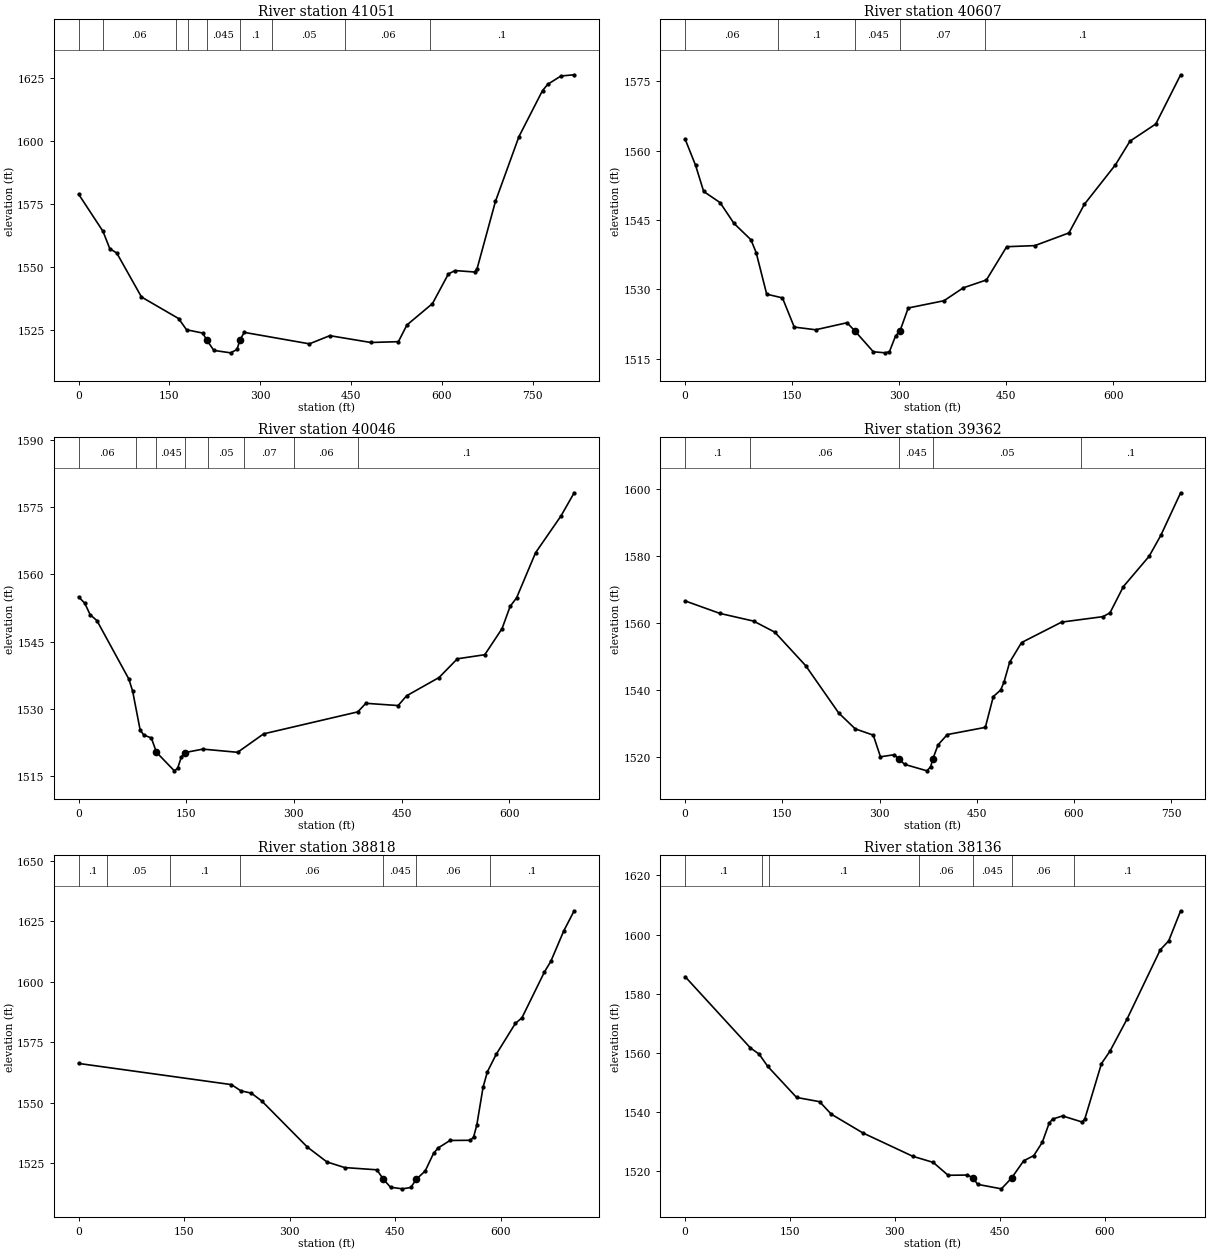
Type RM Length L Ch R = 1 ,41051   ,433.5,443.9,440.5
XS GIS Cut Line= 3
2157036.47769275662826.6660399612156626.06988817663240.229338563
2156407.75201362663329.240491084
#Sta/Elev= 30
       0 1578.86    40.2 1564.11    51.5 1557.17    62.9  1555.5   103.8 1537.97
   165.1  1529.4   178.2 1524.94   204.9 1523.63  211.62 1520.85   223.3 1516.73
   250.9 1515.76   261.6 1517.09266.27981520.851   273.5  1523.9   381.1 1519.34
   414.9 1522.59   482.5 1519.88   528.1  1520.2   542.2 1526.85   584.4 1535.36
   610.6 1547.12   621.6 1548.49   653.8 1547.92   658.1 1549.26   688.4 1576.02
   727.2 1601.79   766.1 1620.08   774.8  1622.6   796.6  1625.9   818.4 1626.38
#Mann= 9 ,-1,0
       0      .1       0      40     .06       0     160     .07       0
     180      .1       0  211.62    .045       0266.2798      .1       0
     320     .05       0     440     .06       0     580      .1       0
Bank Sta=211.62,266.2798
XS Rating Curve= 0 ,0
Exp/Cntr=0.3,0.1

Type RM Length L Ch R = 1 ,40607   ,550.6,560.9,555.4
XS GIS Cut Line= 3
2156719.21108593662571.4733790962156391.15052738662882.025138987
 2156296.4448694663105.225273779
#Sta/Elev= 30
       0 1562.51    14.7 1556.82      26 1551.18      49 1548.77    68.4 1544.29
    92.3 1540.72    99.6 1537.93   114.3 1528.97   136.4 1528.16   152.9 1521.85
   182.9 1521.27   226.9 1522.79   238.2 1520.95   263.7 1516.51   280.6 1516.28
   286.3 1516.54   294.8 1519.92  301.121521.053   312.6 1525.98   362.7 1527.55
   389.7 1530.34   422.1 1532.04   450.5 1539.23     490 1539.47   537.7 1542.21
   559.4 1548.41   602.9 1556.95   623.2 1562.05   659.4 1565.77   694.2 1576.41
#Mann= 5 ,-1,0
       0     .06       0     130      .1       0   238.2    .045       0
  301.12     .07       0     420      .1       0
Bank Sta=238.2,301.12
XS Rating Curve= 0 ,0
Exp/Cntr=0.3,0.1

Type RM Length L Ch R = 1 ,40046   ,650,684.5,675.3
XS GIS Cut Line= 3
2156286.41705476662231.4791389872156007.04269335662565.160525678
2155833.66208593662752.642630995
#Sta/Elev= 30
       0 1554.95     8.5 1553.56      16    1551    25.5 1549.67      70 1536.64
    75.3 1533.92    85.7 1525.32    90.8 1524.16   101.3 1523.53  108.471520.322
   133.4 1516.19   137.9 1516.74   143.1 1519.24   148.3 1520.27   173.2 1521.03
   221.6 1520.32   257.8 1524.43     389 1529.33   400.3 1531.24   445.3 1530.74
     457 1532.91   502.3 1536.99   527.8 1541.16     566 1542.07   590.1 1547.89
   601.4 1552.86   610.3 1554.73   636.8  1564.8   672.2 1572.99   690.6 1578.16
#Mann= 8 ,-1,0
       0     .06       0      80      .1       0  108.47    .045       0
   148.3      .1       0     180     .05       0     230     .07       0
     300     .06       0     390      .1       0
Bank Sta=108.47,148.3
XS Rating Curve= 0 ,0
Exp/Cntr=0.3,0.1

Type RM Length L Ch R = 1 ,39362   ,475.9,543.7,555
XS GIS Cut Line= 4
2155939.81993345 661933.642974722155703.95503707661981.168460832
 2155552.6016767662127.0794138282155339.43661501662357.117417866
#Sta/Elev= 30
       0 1566.66    53.6 1562.94   105.7 1560.64   138.5 1557.33   186.1 1547.34
     237 1533.25   262.5 1528.52   290.3 1526.65   301.4  1520.2   322.5 1520.81
  329.921519.554   338.6 1517.94   373.2 1516.01   378.9 1517.28  382.141519.551
   390.3 1523.77   404.5 1526.82   463.2 1528.97   475.5 1538.15   486.8 1540.09
   491.9  1542.4   500.7 1548.37   519.1 1554.25   580.9 1560.34   644.6 1561.97
   655.5  1563.1   676.2 1570.94   715.9 1579.97   733.9 1586.19   764.5 1598.89
#Mann= 5 ,-1,0
       0      .1       0     100     .06       0  329.92    .045       0
  382.14     .05       0  610.84      .1       0
Bank Sta=329.92,382.14
XS Rating Curve= 0 ,0
Exp/Cntr=0.3,0.1

Type RM Length L Ch R = 1 ,38818   ,671.5,681.4,676.3
XS GIS Cut Line= 3
2155953.62255266661889.1525450632155745.00977758 661762.00433783
2155343.30511541661538.172288969
#Sta/Elev= 30
       0 1566.23   217.2 1557.49   230.5 1554.94   245.3 1553.98   260.2 1550.75
   324.9 1531.75   352.8 1525.58   378.1 1523.25   423.8 1522.33  432.981518.491
   443.2 1515.12   460.2 1514.47     472 1515.03  480.111518.489   492.5 1521.84
   504.3 1529.08   510.8 1531.33   527.8 1534.44   556.6 1534.51   561.2 1535.79
   565.8 1540.75   574.7 1556.35   580.8 1562.75   593.3 1569.95   620.7 1582.79
   629.9 1585.02     662 1604.02   671.1 1608.43   689.4 1620.94   704.2 1629.25
#Mann= 7 ,-1,0
       0      .1       0      40     .05       0     130      .1       0
     230     .06       0  432.98    .045       0  480.11     .06       0
  584.31      .1       0
Bank Sta=432.98,480.11
XS Rating Curve= 0 ,0
Exp/Cntr=0.3,0.1

Type RM Length L Ch R = 1 ,38136   ,503.9,493.7,465.5
XS GIS Cut Line= 4
2156342.81504886 661152.395976422156086.00406065661216.836017685
2155863.27302462661061.6594383132155691.03722662661054.227722821
#Sta/Elev= 30
       0 1585.74    93.5 1561.58   105.8 1559.51   118.2 1555.34   159.4 1544.83
   192.4 1543.39   208.9 1539.18   254.3  1532.8   325.5 1524.91   354.8 1522.83
   376.1 1518.47   403.8 1518.55  412.151517.519   418.2  1515.4   452.3 1513.88
  466.791517.517   484.2 1523.38   498.6 1525.13   510.8 1529.65   520.5 1536.08
   525.4 1537.49   539.7 1538.57   567.4 1536.53   571.4 1537.41   595.4 1556.31
   607.4 1560.44   631.8  1571.3   679.5 1594.83   691.5 1597.83   708.6 1608.04
#Mann= 7 ,-1,0
       0      .1       0     110     .06       0     120      .1       0
  334.77     .06       0  412.15    .045       0  466.79     .06       0
  556.23      .1       0
Bank Sta=412.15,466.79
XS Rating Curve= 0 ,0
Exp/Cntr=0.3,0.1

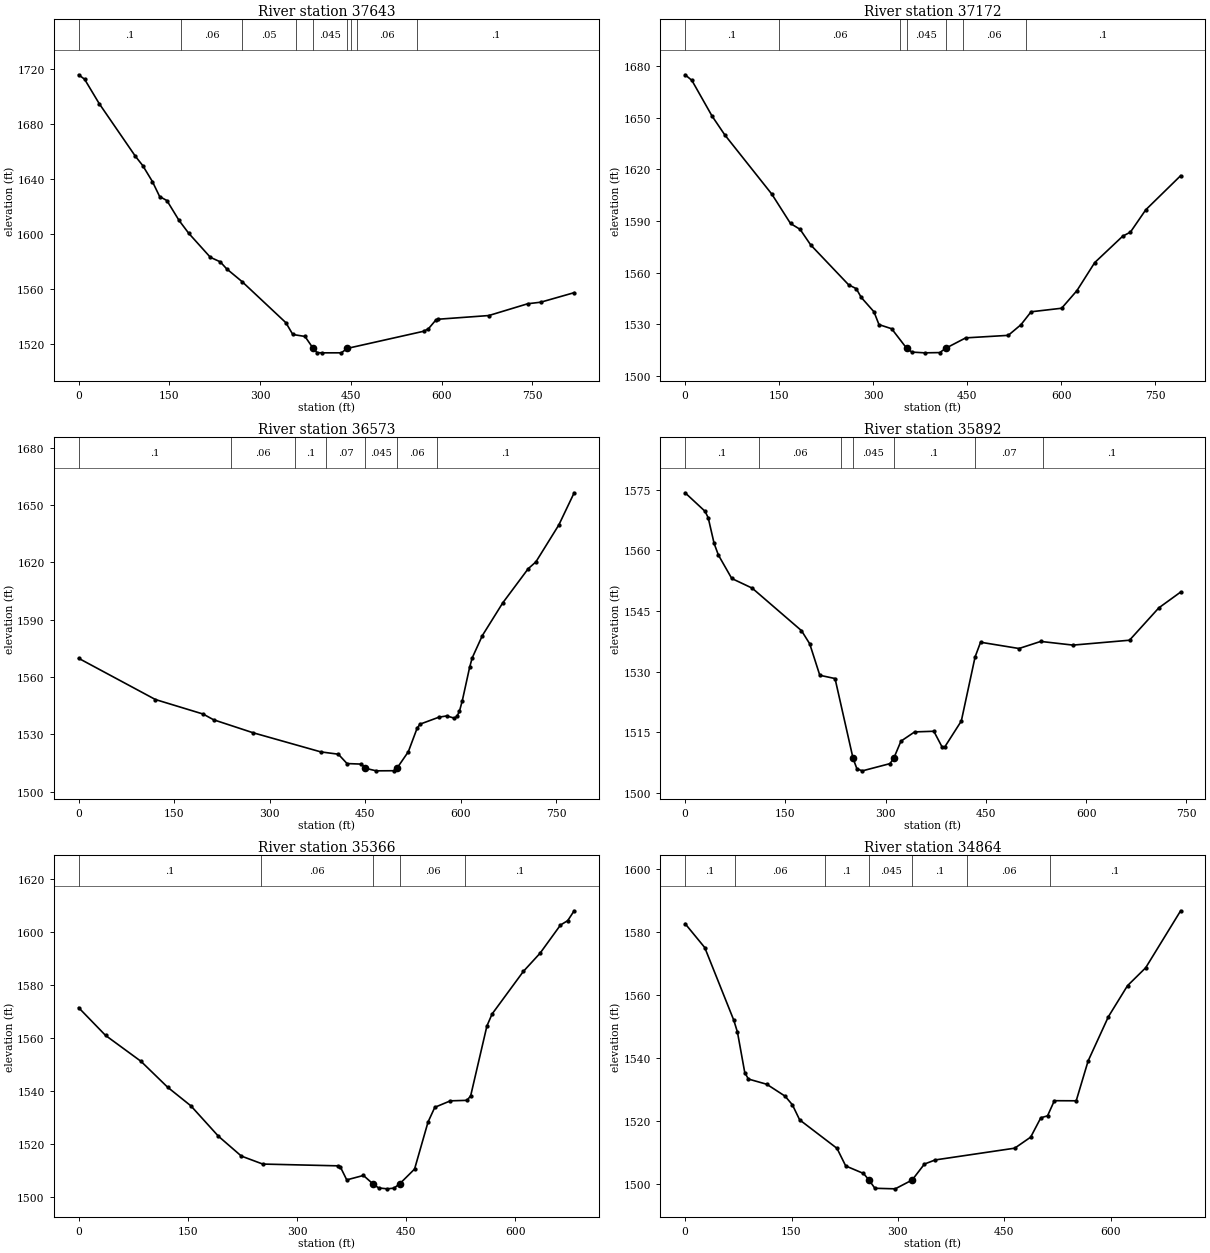
Type RM Length L Ch R = 1 ,37643   ,466.1,470.6,476.8
XS GIS Cut Line= 3
     2156498.017      660674.096     2156088.749      660687.851
      2155679.48      660701.607
#Sta/Elev= 30
       0 1715.98     9.8 1712.77    33.9 1695.07    93.9 1656.62   105.9 1649.94
   121.9  1638.3   133.9 1627.36   145.9 1624.44   165.9 1610.03   181.9 1600.66
   217.7 1583.15     234 1579.86   244.8 1574.69     270  1565.5   342.5 1535.57
     354 1526.97   374.1 1525.55  387.661516.852   394.1 1513.78   402.1 1513.62
   434.1 1513.63     4441516.853   570.2 1529.32   578.2 1531.18   590.2  1537.4
   594.2 1538.08   677.9 1540.76   742.3 1549.35   763.7 1550.47     819 1557.41
#Mann= 9 ,-1,0
       0      .1       0     170     .06       0     270     .05       0
     360     .06       0  387.66    .045       0     444     .06       0
   449.5     .05       0   459.5     .06       0   559.5      .1       0
Bank Sta=387.66,444
XS Rating Curve= 0 ,0
Exp/Cntr=0.3,0.1

Type RM Length L Ch R = 1 ,37172   ,594.9,599.4,604.6
XS GIS Cut Line= 4
2156474.84190881660269.5049232472156154.46856156660228.049939209
2155917.59180052660193.328455513     2155693.406      660152.677
#Sta/Elev= 30
       0 1674.95    10.8  1671.7      43 1650.97    63.2 1640.08   138.4 1605.57
   168.1 1588.57   183.4 1585.15   200.3 1576.11   260.8 1552.94   272.9 1550.72
     281 1545.58   301.2 1537.27   309.2 1529.83   329.4 1527.42  353.391516.059
   361.7 1513.86     382 1513.42   406.2 1513.57  415.55 1516.06   447.5 1522.11
   515.4 1523.58   535.6 1529.75   551.8 1537.27   600.5 1539.33   624.9 1549.56
   653.3 1565.86     698 1581.22   710.2 1583.53   734.6 1596.48   790.3 1616.33
#Mann= 7 ,-1,0
       0      .1       0     150     .06       0  343.04     .05       0
  353.39    .045       0  415.55     .05       0  443.04     .06       0
  543.04      .1       0
Bank Sta=353.39,415.55
XS Rating Curve= 0 ,0
Exp/Cntr=0.3,0.1

Type RM Length L Ch R = 1 ,36573   ,681.7,680.6,662.9
XS GIS Cut Line= 4
2156465.38142401659810.8117743252156128.32006232659724.158697572
2155950.15746769 659624.909537532155724.11216794659624.173137545
#Sta/Elev= 30
       0 1569.82   120.6 1548.23   195.4 1540.64   211.9 1537.64   273.8 1530.85
   380.2 1520.83   407.7 1519.62   421.4 1514.72   444.1 1514.43  450.181512.256
   467.2 1510.91   494.4 1510.97  499.741512.254   517.6  1520.9   531.3 1533.11
   535.9 1535.33   565.6 1538.99   577.9 1539.66   589.9 1538.48   593.9 1539.36
   597.9 1542.12   602.4 1547.69   613.9 1565.15   617.9 1570.03   633.9 1581.75
   665.9 1598.84   705.9 1616.74   717.9 1620.28   753.9 1639.62     778 1656.46
#Mann= 7 ,-1,0
       0      .1       0     240     .06       0     340      .1       0
  388.02     .07       0  450.18    .045       0  499.74     .06       0
  561.96      .1       0
Bank Sta=450.18,499.74
XS Rating Curve= 0 ,0
Exp/Cntr=0.3,0.1

Type RM Length L Ch R = 1 ,35892   ,510.4,525.9,520.1
XS GIS Cut Line= 4
2156519.53142648659199.7750944342156350.91135862659069.230896544
2156056.14391177659000.3888565482155832.18662255659025.077076049
#Sta/Elev= 30
       0 1574.25    29.9 1569.66    34.6 1568.05    43.4 1561.73    49.8 1558.85
    69.8 1553.05   100.4 1550.66   174.1 1540.15   186.4  1536.9   201.5 1529.11
   224.3  1528.3  251.291508.534   257.1 1505.94   265.3 1505.47   306.4 1507.25
  312.031508.531   322.9 1512.81   343.4  1515.1   372.1 1515.26   384.5 1511.35
   388.6 1511.42   413.2 1517.79   433.8 1533.64     442 1537.28   499.5 1535.73
     532 1537.48   580.3 1536.57   664.8 1537.78   708.7 1545.79   741.3 1549.69
#Mann= 7 ,-1,0
       0      .1       0     110     .06       0  233.25      .1       0
  251.29    .045       0  312.03      .1       0  433.25     .07       0
  535.95      .1       0
Bank Sta=251.29,312.03
XS Rating Curve= 0 ,0
Exp/Cntr=0.3,0.1

Type RM Length L Ch R = 1 ,35366   ,507.4,502.1,481.1
XS GIS Cut Line= 4
2156718.36902471658831.041506972 2156487.8494962658641.880228772
2156322.49078353658542.0036384042156168.94078835       658430.93
#Sta/Elev= 30
       0 1571.32      37 1560.84    85.6 1551.08   122.3 1541.29   154.3 1534.25
   192.1 1522.79   223.6  1515.3     253 1512.29   356.7 1511.62   359.7 1511.16
   368.4 1506.32   391.3 1507.99  404.161504.882   412.1 1503.29     424 1502.94
   433.3 1503.21  441.32 1504.88   461.6  1510.4   480.1 1528.15   489.4 1533.71
   510.8 1536.15   533.7 1536.34   538.7 1538.07     561  1564.4   568.1 1568.92
   611.1    1585     634 1591.85   662.1  1602.5     672 1604.15   680.9 1607.88
#Mann= 5 ,-1,0
       0      .1       0     250     .06       0  404.16    .045       0
  441.32     .06       0  531.38      .1       0
Bank Sta=404.16,441.32
XS Rating Curve= 0 ,0
Exp/Cntr=0.3,0.1

Type RM Length L Ch R = 1 ,34864   ,429.4,421,393.7
XS GIS Cut Line= 4
2156977.33646831658422.6960215392156824.22983777658297.818619771
2156584.42937099658241.4849489132156370.78195057658103.022911915
#Sta/Elev= 30
       0  1582.7    27.7 1575.09    68.6    1552    73.8 1548.19    84.1 1535.34
    89.2 1533.28   115.1 1531.62   140.9 1527.84   151.2  1525.1   161.5 1520.29
   214.1 1511.24   226.4 1505.64   251.4 1503.26  259.231501.165   267.5 1498.54
   296.2 1498.36  320.031501.165   337.3 1506.23   352.5 1507.55   464.6 1511.29
   487.1  1514.8   501.4 1520.95   510.9 1521.58   520.5 1526.39   551.3 1526.36
   568.1 1539.04   596.7 1553.12   623.6 1562.97   649.2 1568.66   698.5 1586.79
#Mann= 7 ,-1,0
       0      .1       0      70     .06       0  197.58      .1       0
  259.23    .045       0  320.03      .1       0  397.58     .06       0
   513.9      .1       0
Bank Sta=259.23,320.03
XS Rating Curve= 0 ,0
Exp/Cntr=0.3,0.1

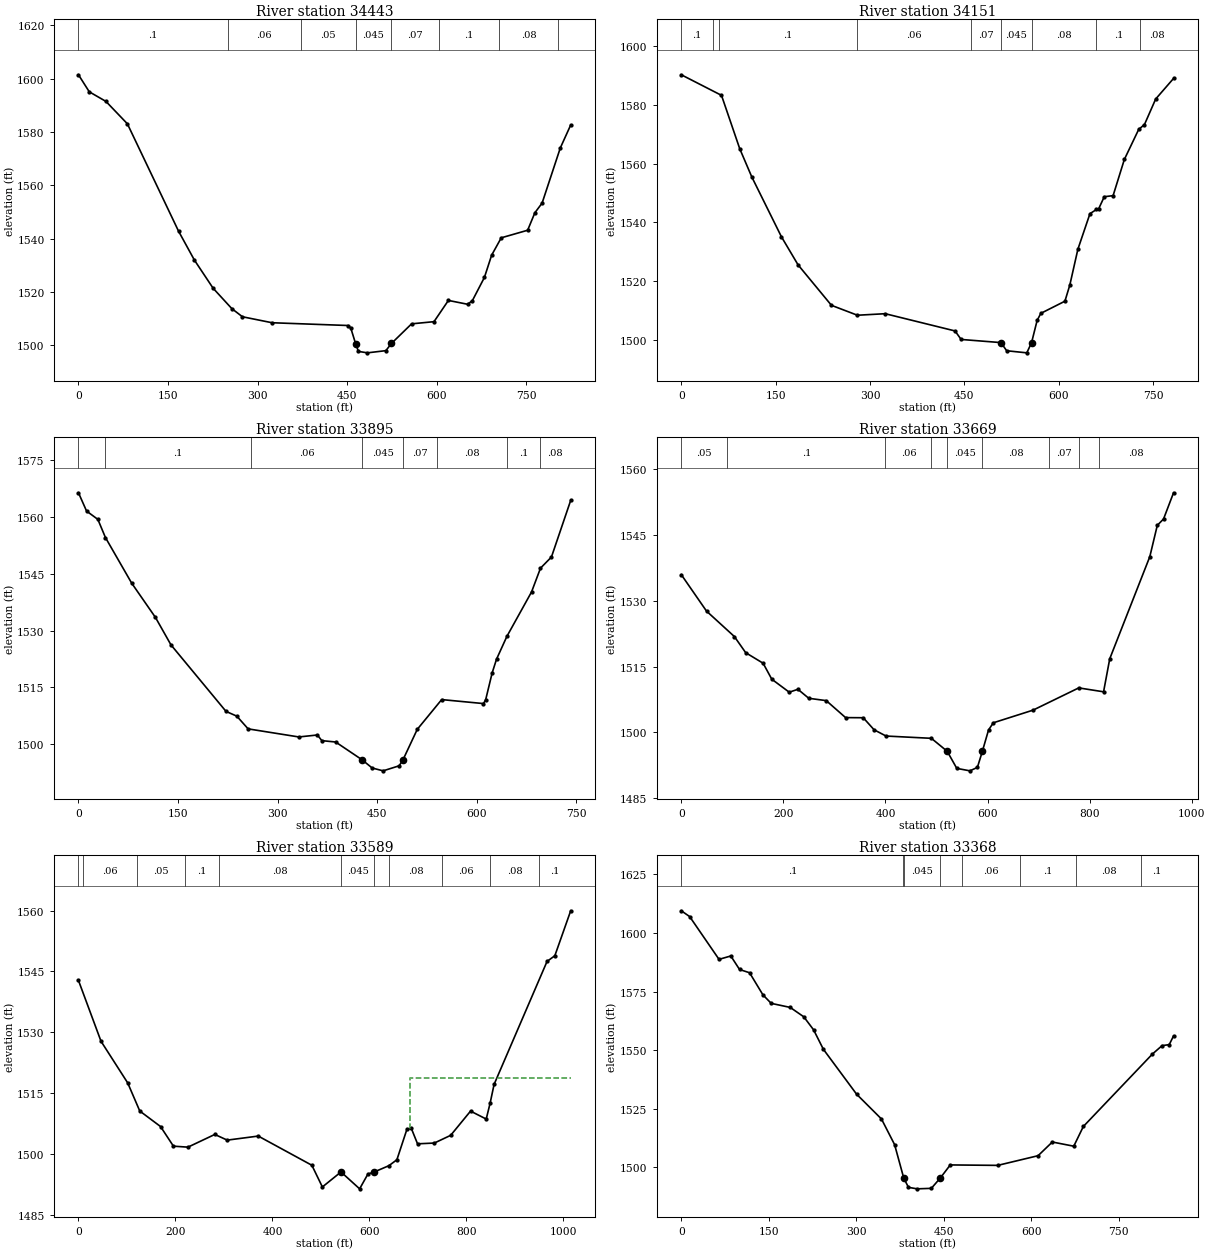
Type RM Length L Ch R = 1 ,34443   ,263.1,292.6,307
XS GIS Cut Line= 5
2157145.20017186657937.3741028232156840.11114995657782.327570533
2156789.73062654657857.8423623542156657.75382899657906.240459624
2156408.48907194657932.606501349
#Sta/Elev= 30
       0 1601.48    18.1 1595.09      46 1591.49    81.9 1583.09   167.5 1542.85
   194.1 1531.97   225.5 1521.39   256.9 1513.73   274.6  1510.7   324.2 1508.46
   451.7 1507.42     456 1506.43  463.98 1500.66   468.7 1497.71   483.8 1497.17
   514.7 1497.99     524 1500.68   557.8 1508.05   595.3 1508.86   619.4 1516.83
   651.6 1515.39   659.6 1516.77   679.7 1525.45   691.8  1533.8   707.9 1540.32
   752.1 1543.16   764.2 1549.72   776.3 1553.34   806.8 1574.04   824.2 1582.64
#Mann= 8 ,-1,0
       0      .1       0     250     .06       0  372.23     .05       0
  463.98    .045       0     524     .07       0  603.58      .1       0
  703.58     .08       0  803.58      .1       0
Bank Sta=463.98,524
XS Rating Curve= 0 ,0
Exp/Cntr=0.3,0.1

Type RM Length L Ch R = 1 ,34151   ,237.3,255.7,248.2
XS GIS Cut Line= 2
2157169.59953821657855.9420818722156483.65041159657479.203183315
#Sta/Elev= 30
       0 1590.19    63.9  1583.2    92.9 1565.06   112.1 1555.46   159.2 1535.13
   185.7 1525.57   238.7 1511.84     280 1508.47   324.2 1508.99   435.2 1503.13
   444.9 1500.24   508.2 1499.17   517.3  1496.4   549.3 1495.69   556.9 1499.17
   565.7 1506.69   571.6 1509.11   609.9 1513.24   617.7 1518.73   630.5 1530.89
   649.7 1542.98     660 1544.41   663.3 1544.54   672.5 1548.75   686.5 1549.11
   704.4 1561.42   727.2 1571.62   736.4 1573.28   754.2 1581.95   782.6 1588.94
#Mann= 9 ,-1,0
       0      .1       0      50     .06       0      60      .1       0
     280     .06       0     460     .07       0   508.2    .045       0
   556.9     .08       0     660      .1       0     730     .08       0
Bank Sta=508.2,556.9
XS Rating Curve= 0 ,0
Exp/Cntr(USF)=0,0
Exp/Cntr=0.3,0.1

Type RM Length L Ch R = 1 ,33895   ,250.4,225.7,223.9
XS GIS Cut Line= 3
2157213.72392266657760.8511892982156802.88277608657372.819810702
2156632.03487995657329.608642535
#Sta/Elev= 30
       0 1566.32    12.2  1561.5    29.2 1559.31    40.6 1554.53    80.1 1542.51
     116 1533.45   139.3 1526.23   222.2  1508.7   238.5 1507.44   255.5 1504.09
   331.9 1501.96   359.8 1502.48   366.5 1500.99   387.3 1500.63  427.071495.945
   442.3 1493.78   458.8 1493.03     483 1494.36  488.751495.945   510.2 1503.96
     547 1511.81   609.9 1510.76   613.2 1511.74     623 1518.84   629.6 1522.46
   645.2 1528.47   682.3 1540.17   695.8 1546.45   712.3 1549.39   741.3 1564.32
#Mann= 8 ,-1,0
       0     .06       0      40      .1       0     260     .06       0
  427.07    .045       0  488.75     .07       0     540     .08       0
  645.12      .1       0  695.12     .08       0
Bank Sta=427.07,488.75
XS Rating Curve= 0 ,0
Exp/Cntr=0.3,0.1

Type RM Length L Ch R = 1 ,33669   ,81.3,80.7,82.5
XS GIS Cut Line= 3
2157594.47794305657512.4787869122156864.13177224657242.077242723
2156680.83520268657212.302050874
#Sta/Elev= 30
       0 1535.93    49.4 1527.63     104 1521.83   126.2 1518.15   160.3 1515.75
   177.3 1512.11   211.5 1509.15   228.5 1509.81   249.8 1507.76     284 1507.23
   321.9 1503.36   356.5 1503.33   377.8 1500.58   401.2 1499.16     490 1498.64
  521.021495.686   539.8 1491.79   565.5 1491.23   580.2 1492.02  589.931495.684
     602 1500.54   611.4 1502.18   689.2 1505.06   778.8 1510.13   827.4 1509.24
   839.5 1516.77     918 1540.03   932.7 1547.18   944.9 1548.61   964.5 1554.59
#Mann= 9 ,-1,0
       0     .05       0      90      .1       0     400     .06       0
     490     .08       0  521.02    .045       0  589.93     .08       0
     720     .07       0   778.8     .06       0   818.8     .08       0
Bank Sta=521.02,589.93
XS Rating Curve= 0 ,0
Exp/Cntr=0.3,0.1

Type RM Length L Ch R = 1 ,33589   ,242.8,220.6,207.2
XS GIS Cut Line= 3
 2157623.8041458  657439.92694252156893.45797499657169.525398311
2156659.83264707657135.309433666
#Sta/Elev= 30
       0 1542.78    46.5 1527.79   101.5 1517.54   126.4 1510.61   169.2 1506.79
   195.8 1501.95   225.7 1501.71   281.1 1504.84   306.7 1503.44   370.7 1504.44
   481.2 1497.25   502.9  1491.9   541.3  1495.6   579.7 1491.44   596.8 1495.09
  610.071495.613     640 1497.14   656.5  1498.6   677.3 1506.14   686.3 1506.33
   699.1 1502.53   733.7 1502.72   767.4 1504.62   808.4 1510.59   840.7 1508.63
   848.8 1512.57   856.9 1517.16   966.1 1547.46   982.2 1548.87  1014.9 1559.94
#Mann= 11 ,-1,0
       0     .05       0      10     .06       0     120     .05       0
     220      .1       0     290     .08       0   541.3    .045       0
  610.07     .03       0     640     .08       0     750     .06       0
   848.8     .08       0   948.8      .1       0
#XS Ineff= 2 , 0
                          684.17         1518.76
Permanent Ineff=
       F       F
Bank Sta=541.3,610.07
XS Rating Curve= 0 ,0
Exp/Cntr=0.3,0.1

Type RM Length L Ch R = 1 ,33368   ,693.1,656.1,639.8
XS GIS Cut Line= 4
 2157418.4337122656795.3413467212157217.59048321656991.585890366
2156856.93019322657059.3058717422156664.92383575657100.726246048
#Sta/Elev= 30
       0 1609.46    14.3 1606.99    64.7 1588.74    84.9 1590.18    99.9 1584.41
   117.1 1583.02     140 1573.59   154.2 1569.96   186.8 1568.23   210.1 1564.22
   226.9 1558.66   243.6 1550.39   300.6 1531.22   343.3 1520.63   365.8  1509.7
  381.511495.414   389.6 1491.47   404.3 1490.83   428.8 1491.04   444.11495.418
   461.3 1501.03   542.7 1500.84   611.9 1504.97   636.3 1510.81   673.1 1509.02
   689.5 1517.43   808.1 1548.37   824.5 1551.92   836.8 1552.36   844.2 1556.05
#Mann= 8 ,-1,0
       0      .1       0   380.8     .05       0  381.51    .045       0
   444.1     .05       0   480.8     .06       0   580.8      .1       0
  677.77     .08       0  787.77      .1       0
Bank Sta=381.51,444.1
XS Rating Curve= 0 ,0
Exp/Cntr=0.3,0.1