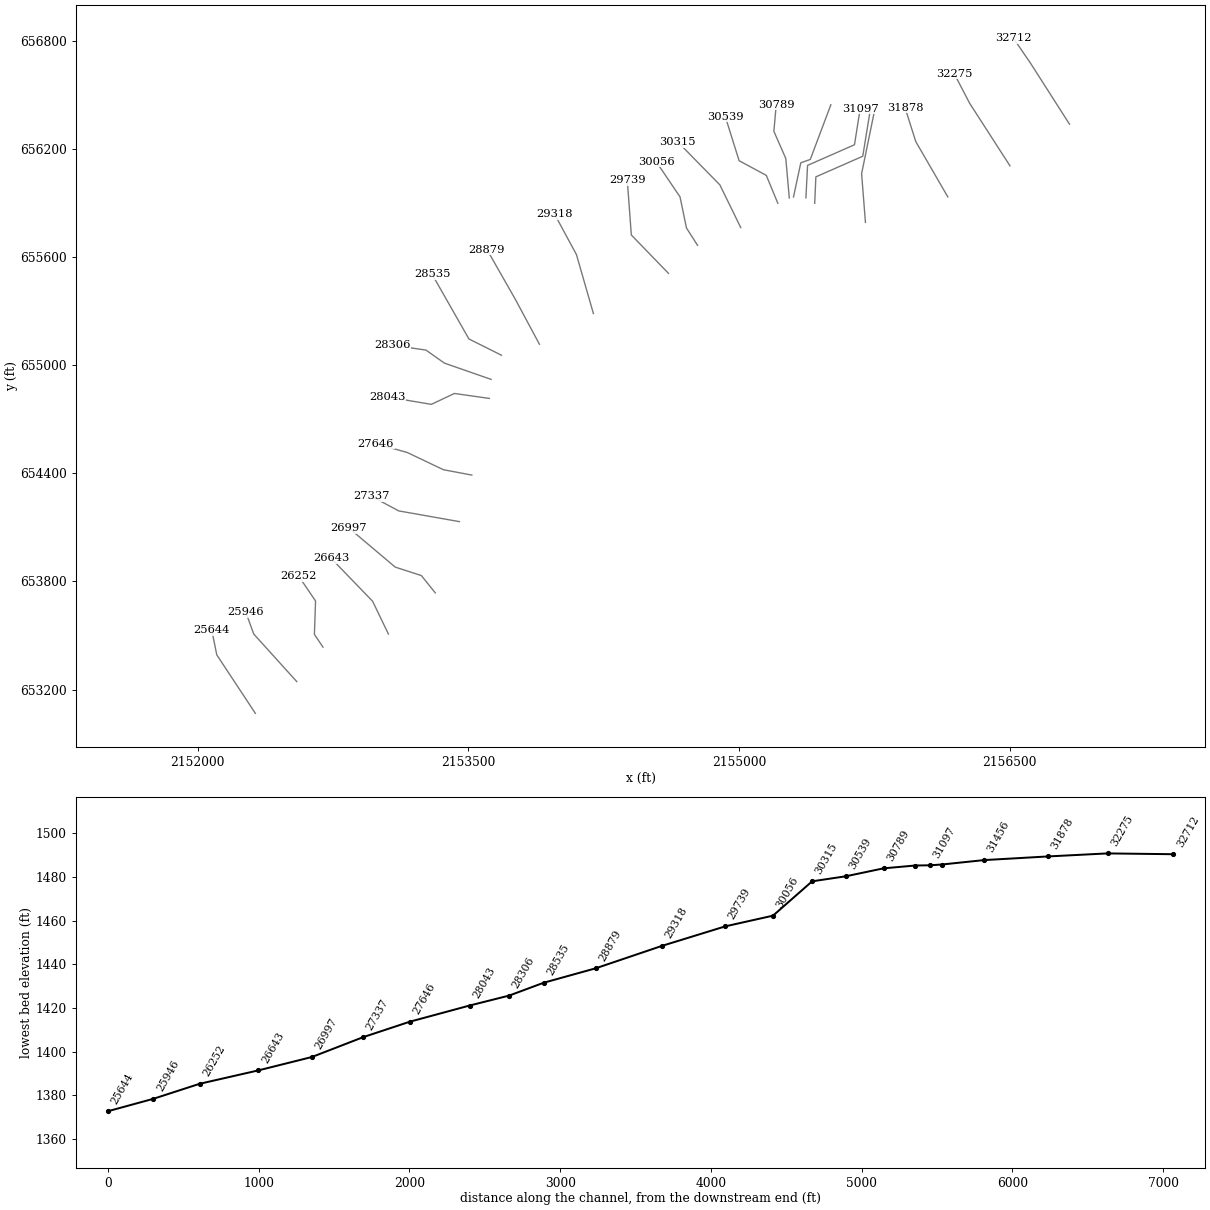
HEC-RAS study LIKANARV.prj: LIKANARV

--- LIKANARV.g01 (geometry) --- (continued)

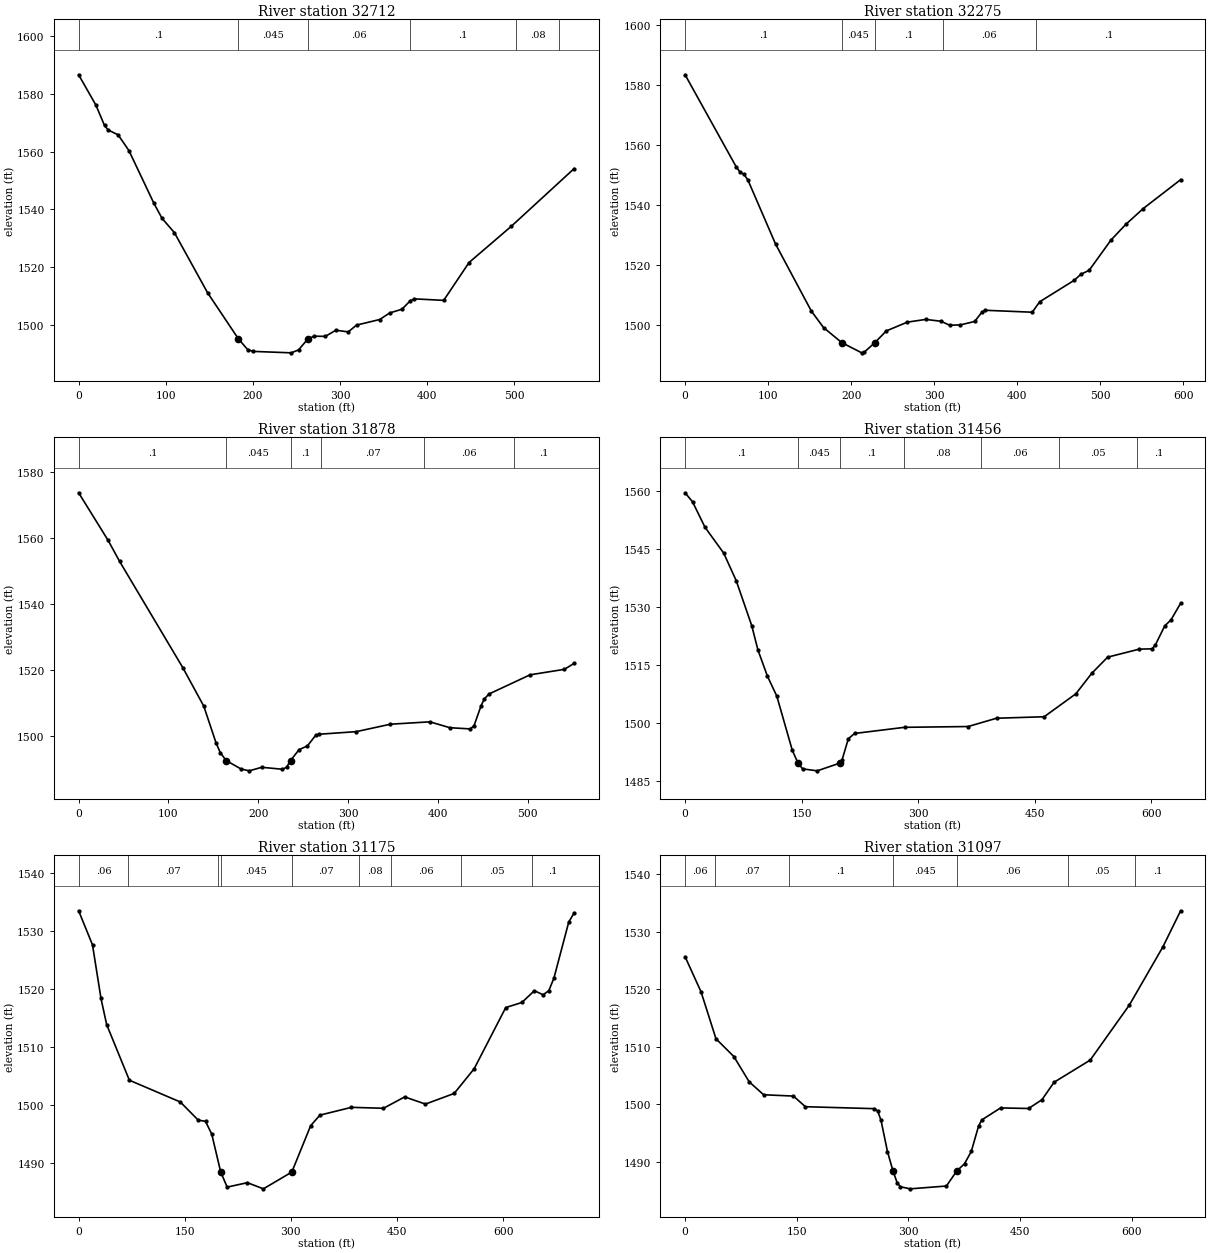
Type RM Length L Ch R = 1 ,32712   ,418,437.4,429
XS GIS Cut Line= 3
2156832.55536817656336.5285054662156616.36239649656674.972653611
     2156522.124 656812.74810674
#Sta/Elev= 30
       0 1586.67    19.8 1576.16    29.7 1569.11      34 1567.51    45.3 1565.86
    57.7  1560.4    86.2 1542.22    95.7 1536.92   109.9 1531.95   147.9 1511.15
  183.361495.125   193.9 1491.44   200.1 1490.81     244 1490.31   252.3 1491.33
  263.031495.127   270.1 1496.08   283.1 1496.02   295.1 1498.15   309.3 1497.57
   318.8 1499.92   345.4 1501.86     357 1504.15     371 1505.43   380.5 1508.38
   385.2 1509.02   418.8 1508.49   447.9 1521.61   496.4 1534.17   568.5 1554.17
#Mann= 6 ,-1,0
       0      .1       0  183.36    .045       0  263.03     .06       0
     380      .1       0   501.6     .08       0   551.6      .1       0
Bank Sta=183.36,263.03
XS Rating Curve= 0 ,0
Exp/Cntr=0.3,0.1

Type RM Length L Ch R = 1 ,32275   ,383,396.6,387.2
XS GIS Cut Line= 3
2156502.45686055656105.5045751922156278.99109366656452.489631833
2156194.01602832656615.700479298
#Sta/Elev= 30
       0 1583.36    61.5  1552.7    66.2 1550.91      71 1550.15    75.7 1548.23
     109  1526.9     152 1504.61   166.7  1499.1   188.61494.097   212.7 1490.68
   215.6 1490.86  228.561494.097   242.3 1497.99   267.7 1500.92   289.8 1501.82
   308.2  1501.2   318.4  1499.9   331.3 1499.98   348.7 1501.14   357.4 1504.24
   361.2 1504.87     418 1504.22     427  1507.7   468.7 1514.88   476.6 1516.88
   486.5 1518.17   512.7 1528.23   530.7  1533.5   551.7 1538.78   596.7  1548.4
#Mann= 5 ,-1,0
       0      .1       0   188.6    .045       0  228.56      .1       0
     310     .06       0  422.72      .1       0
Bank Sta=188.6,228.56
XS Rating Curve= 0 ,0
Exp/Cntr=0.3,0.1

Type RM Length L Ch R = 1 ,31878   ,427.4,422.2,402.5
XS GIS Cut Line= 3
2156158.13554902655932.8254967722155980.40730937 656239.75700439
2155920.85452724656427.497021778
#Sta/Elev= 30
       0 1573.83    32.8 1559.37    45.6 1552.97     116 1520.64   139.3 1508.96
   152.9 1497.84   157.6 1494.86  164.221492.419   180.7 1489.86   189.9 1489.29
   203.8 1490.37   226.9 1489.77   231.5 1490.38  235.861492.422   245.4 1495.74
   254.6 1496.85   263.9 1500.11   267.3 1500.41   309.1 1501.21   347.1 1503.47
     391 1504.19   413.3  1502.4   435.9 1502.04   440.1    1503     448 1509.09
   451.6 1511.17   456.9 1512.67   502.5 1518.48   540.7 1520.15   551.6 1521.97
#Mann= 6 ,-1,0
       0      .1       0  164.22    .045       0  235.86      .1       0
     270     .07       0  384.67     .06       0  484.67      .1       0
Bank Sta=164.22,235.86
XS Rating Curve= 0 ,0
Exp/Cntr=0.3,0.1

Type RM Length L Ch R = 1 ,31456   ,313,281.1,221
XS GIS Cut Line= 3
2155701.27904509655791.6191274862155680.00702157656062.333800017
2155753.75408823656421.335847052
#Sta/Elev= 30
       0 1559.49     9.6 1557.15    25.6 1550.58    49.7  1543.9    65.8 1536.78
    85.8 1525.15    93.8 1518.84   105.9 1512.14   118.1 1506.91     138 1492.94
  145.321489.624   151.3 1488.13   170.1 1487.62  199.321489.625   202.2 1490.51
   210.2 1495.93   218.2 1497.28   282.6 1498.87   364.3 1499.07     401 1501.22
   462.3  1501.6   503.1 1507.53   523.5 1512.81     544    1517   584.8 1519.08
   601.1 1519.15   605.2 1520.06   617.5 1525.07   625.6 1526.65     638 1530.93
#Mann= 7 ,-1,0
       0      .1       0  145.32    .045       0  199.32      .1       0
  281.55     .08       0  381.55     .06       0  481.55     .05       0
  581.55      .1       0
Bank Sta=145.32,199.32
XS Rating Curve= 0 ,0
Exp/Cntr=0.3,0.1

Type RM Length L Ch R = 1 ,31175   ,82,78.2,78.2
XS GIS Cut Line= 4
2155420.02428189655897.5878111032155426.39186814 656044.22613654
2155686.38185736656158.624711803 2155729.5421106656424.598927034
#Sta/Elev= 30
       0 1533.47    19.6  1527.6    31.6 1518.37    39.6 1513.88    71.7  1504.3
   143.7 1500.55     169 1497.43   179.3 1497.22   188.1 1495.03  200.791488.487
   209.9  1485.9   238.5 1486.66   261.1  1485.6  301.261488.488   327.9 1496.47
     341 1498.29   385.6 1499.63   430.8 1499.47   460.8 1501.43   490.1 1500.19
   530.7 1502.02     559 1506.28   603.6 1516.81   626.4 1517.68   644.1 1519.71
   656.3 1519.01   664.4  1519.7   671.7 1521.88   692.6 1531.52   700.3 1533.12
#Mann= 9 ,-1,0
       0     .06       0      70     .07       0  196.78      .1       0
  200.79    .045       0  301.26     .07       0  396.78     .08       0
  440.82     .06       0  540.82     .05       0  640.82      .1       0
Bank Sta=200.79,301.26
XS Rating Curve= 0 ,0
Exp/Cntr=0.3,0.1

Type RM Length L Ch R = 1 ,31097   ,73.5,98,133.1
XS GIS Cut Line= 4
2155371.15769266655927.7752908272155380.44304968656107.967980291
2155640.43303891656222.3665555552155671.92220901656421.232042729
#Sta/Elev= 30
       0 1525.63    21.4 1519.54    41.5 1511.36    65.5 1508.27    86.1 1503.87
   105.5 1501.62   145.6 1501.39   161.6 1499.54   254.4  1499.2   258.8 1498.78
   263.2 1497.18   271.9 1491.74  279.261488.377     285 1486.28   289.4 1485.61
   302.4 1485.25   351.1 1485.74   365.11488.376   375.4 1489.61   384.5 1491.75
   394.3 1496.17   398.6 1497.24   423.9 1499.33   461.5 1499.23   479.5 1500.76
   495.7 1503.79   544.3 1507.65   596.9 1517.23   641.9 1527.34   665.8 1533.63
#Mann= 7 ,-1,0
       0     .06       0      40     .07       0     140      .1       0
  279.26    .045       0   365.1     .06       0  514.48     .05       0
  604.48      .1       0
Bank Sta=279.26,365.1
XS Rating Curve= 0 ,0
Exp/Cntr=0.3,0.1

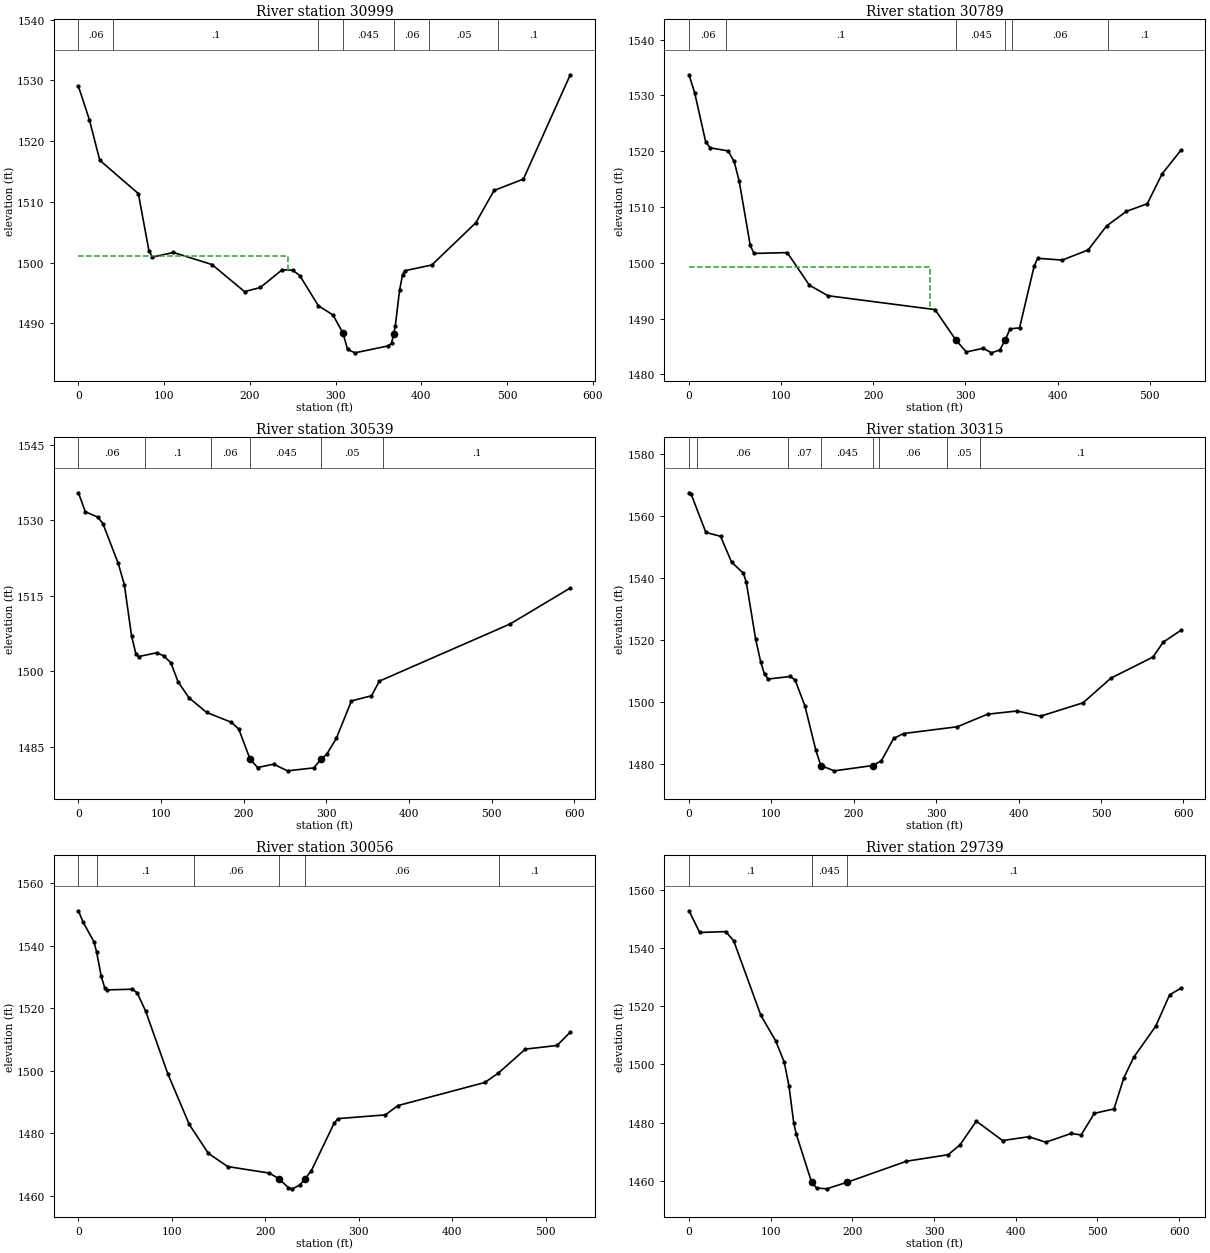
Type RM Length L Ch R = 1 ,30999   ,193.7,209.8,233.8
XS GIS Cut Line= 4
2155302.39321223655932.7935182792155342.85467672656122.327496277
2155395.41414704656140.844498618 2155509.6050749656444.386823271
#Sta/Elev= 30
       0 1529.03    12.7 1523.55    24.9 1516.85    69.9 1511.36    82.2 1501.99
    86.3  1500.9   110.8 1501.67   155.8 1499.68   193.8 1495.22   212.2  1495.9
   237.6 1498.81   249.9 1498.77   258.4 1497.83   279.8 1492.91   296.9 1491.38
   308.5 1488.44     314 1485.71   322.5 1485.14     361 1486.27   365.3 1486.69
   367.81488.321   369.6  1489.5   374.6 1495.41   378.1 1498.01   380.8 1498.66
   412.3 1499.61   463.6 1506.56   484.9 1511.88   519.1 1513.75   573.8 1530.93
#Mann= 7 ,-1,0
       0     .06       0      40      .1       0  279.53     .06       0
   308.5    .045       0   367.8     .06       0  409.53     .05       0
  489.53      .1       0
#XS Ineff= 2 , 0
          244.54 1501.08
Permanent Ineff=
       F       F
Bank Sta=308.5,367.8
XS Rating Curve= 0 ,0
Exp/Cntr=0.3,0.1

Type RM Length L Ch R = 1 ,30789   ,204,250.1,245
XS GIS Cut Line= 4
2155279.10349998655927.0040984852155259.67123651656146.200030431
2155193.60154071 656296.994394962155206.81547987656445.456887874
#Sta/Elev= 30
       0  1533.7     6.2 1530.44    18.2  1521.6    23.1  1520.6    42.3 1520.06
      49 1518.16    54.4 1514.68    66.4 1503.15    70.5 1501.67   106.6 1501.82
   130.7 1495.97   150.8 1494.09     267  1491.6   289.71486.115   300.9 1484.01
   319.4 1484.67   328.1 1483.85   337.3 1484.36  343.251486.208   348.4 1488.15
   358.7 1488.33   374.5 1499.36   378.3  1500.8     405 1500.48   433.1 1502.29
   453.1 1506.59   474.6 1509.21   497.3 1510.58   513.4 1515.94   533.7 1520.15
#Mann= 6 ,-1,0
       0     .06       0      40      .1       0   289.7    .045       0
  343.25      .1       0  350.06     .06       0  454.69      .1       0
#XS Ineff= 2 , 0
          261.06 1499.16
Permanent Ineff=
       F       F
Bank Sta=289.7,343.25
XS Rating Curve= 0 ,0
Exp/Cntr(USF)=0,0
Exp/Cntr=0.3,0.1

Type RM Length L Ch R = 1 ,30539   ,246.1,223.4,205
XS GIS Cut Line= 4
2155215.56729104655897.7931026462155151.56916279656052.570893038
2155000.85435262656133.8076576942154924.25495032656378.758363868
#Sta/Elev= 30
       0 1535.44     8.3 1531.68    23.6 1530.58    29.6 1529.32    48.1 1521.44
    55.6 1517.17    64.3 1506.99    69.5 1503.48    72.9 1502.92    94.6 1503.66
   103.1 1503.08   111.9 1501.68   120.5 1497.93   133.8 1494.72   155.2 1491.82
     185 1489.87   194.1  1488.5   207.7 1482.56   216.8 1480.88   236.2 1481.54
   253.1 1480.22   284.9 1480.81     294 1482.61   300.4 1483.48   312.2 1486.69
   330.4  1494.1   354.7 1495.13   364.3 1498.04   522.4 1509.38   595.3 1516.53
#Mann= 6 ,-1,0
       0     .06       0      80      .1       0     160     .06       0
   207.7    .045       0     294     .05       0   368.7      .1       0
Bank Sta=207.7,294
XS Rating Curve= 0 ,0
Exp/Cntr(USF)=0,0
Exp/Cntr=0.3,0.1

Type RM Length L Ch R = 1 ,30315   ,264,259.7,254.9
XS GIS Cut Line= 3
2155009.96132155655762.7691510032154894.30455097655999.624274511
2154661.13199019656237.760749006
#Sta/Elev= 30
       0  1567.5     2.7 1566.98    20.5 1554.72    38.3 1553.48    51.6 1545.18
    65.9  1541.6    69.5 1538.73    80.9 1520.33    86.9 1513.13    91.7    1509
    96.2  1507.5   122.9 1508.32   128.8 1507.18   140.7 1498.81     154  1484.5
  159.971479.624   176.3 1477.92  222.741479.623   233.4 1481.12   248.4 1488.38
   260.4 1489.94   325.6 1492.12   362.4 1496.17   398.1  1497.2   426.7 1495.53
   478.3 1499.85   512.1 1507.79   563.2 1514.59   575.4 1519.35   596.9 1523.18
#Mann= 8 ,-1,0
       0      .1       0      10     .06       0     120     .07       0
  159.97    .045       0  222.74     .07       0     230     .06       0
  313.58     .05       0  353.58      .1       0
Bank Sta=159.97,222.74
XS Rating Curve= 0 ,0
Exp/Cntr=0.3,0.1

Type RM Length L Ch R = 1 ,30056   ,307.9,316.2,320.1
XS GIS Cut Line= 4
2154770.34346254655664.5735295212154709.11226955655760.529143543
2154673.38617933655932.8697812592154541.02127688656128.976262709
#Sta/Elev= 30
       0 1551.18     4.9 1547.59    16.5 1541.32    19.4 1538.06    24.4  1530.2
    28.1 1526.56      31 1525.87    57.7 1526.08    62.8 1524.95    71.9 1519.09
    95.6 1499.07   118.6 1482.83     139 1473.57   159.8 1469.33   204.4 1467.25
  214.16  1465.5   224.8 1462.58   228.9 1462.21     237 1463.43   242.81465.502
   249.3 1468.05   273.8 1483.29   277.9 1484.68   328.4 1485.87     342 1488.85
     435 1496.25   449.5 1499.26   478.4 1506.92   512.2 1508.08   526.4 1512.35
#Mann= 6 ,-1,0
       0     .06       0      20      .1       0  123.83     .06       0
  214.16    .045       0   242.8     .06       0  449.83      .1       0
Bank Sta=214.16,242.8
XS Rating Curve= 0 ,0
Exp/Cntr=0.3,0.1

Type RM Length L Ch R = 1 ,29739   ,424.3,421.1,402.4
XS GIS Cut Line= 3
2154609.26148774655508.9376884742154403.36433459655721.742552257
2154380.74718799656026.817177384
#Sta/Elev= 30
       0 1552.75    13.1  1545.3    44.9  1545.6    54.7 1542.47    87.9 1516.88
   106.1 1508.11   116.6 1500.78   122.4 1492.54   128.2 1479.97   131.1 1476.29
  150.131459.541   156.2 1457.63   168.4 1457.33  193.071459.545   266.2  1466.8
   317.2 1469.04   331.6 1472.39   351.7 1480.56   383.8  1473.9   415.9 1475.21
   436.7 1473.33     468 1476.35     480  1475.8   496.1 1483.25   520.2 1484.75
   532.2 1495.37   544.2 1502.41   571.2 1513.11   588.3  1523.9     602 1526.18
#Mann= 3 ,-1,0
       0      .1       0  150.13    .045       0  193.07      .1       0
Bank Sta=150.13,193.07
XS Rating Curve= 0 ,0
Exp/Cntr=0.3,0.1

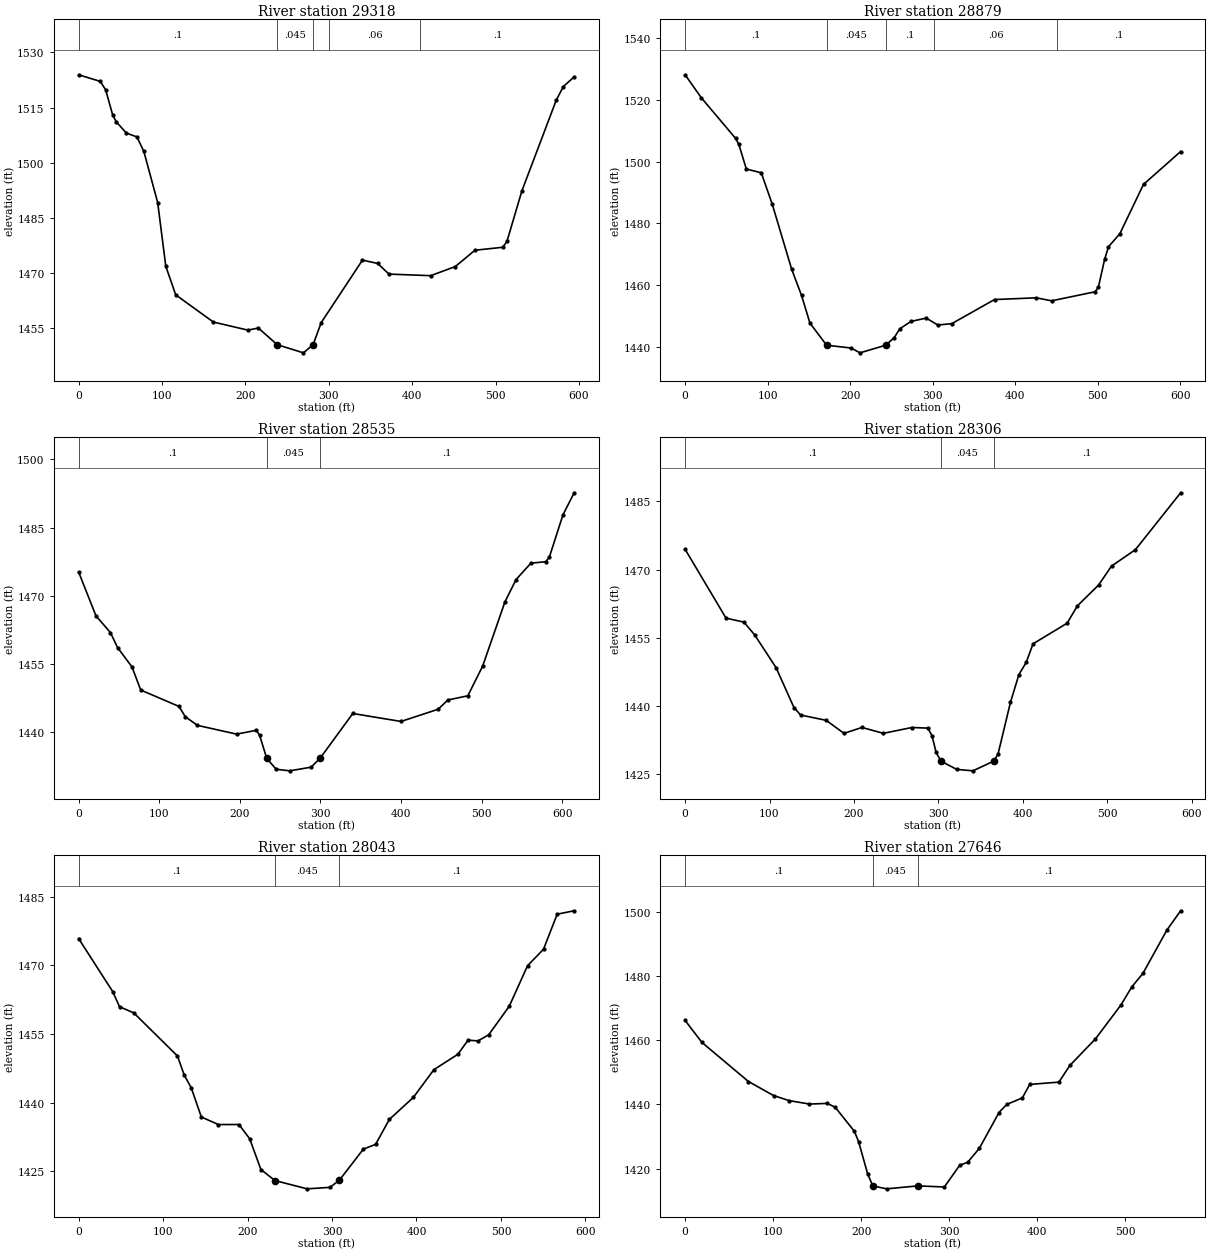
Type RM Length L Ch R = 1 ,29318   ,416.3,438.9,425.4
XS GIS Cut Line= 3
2154193.06813846655286.0465783382154099.10308181 655612.79382693
2153978.37996539655836.619166777
#Sta/Elev= 30
       0 1523.91    25.9 1522.12    32.4 1519.83    40.7 1513.11    44.9 1511.18
    57.4 1508.05    69.9 1507.04    78.2  1503.1    94.8 1489.21   104.5 1471.93
   116.4 1464.14   161.6 1456.74     203 1454.55   215.5 1455.12  238.191450.593
   269.6 1448.38  281.211450.595   290.9 1456.58   340.4 1473.57   358.6 1472.66
   372.2 1469.77   422.2 1469.34   451.7 1471.81   475.3 1476.25   508.6 1477.05
   513.7 1478.65   531.5 1492.31   572.7 1516.95   581.3 1520.72   594.3 1523.34
#Mann= 5 ,-1,0
       0      .1       0  238.19    .045       0  281.21      .1       0
     300     .06       0  409.99      .1       0
Bank Sta=238.19,281.21
XS Rating Curve= 0 ,0
Exp/Cntr=0.3,0.1

Type RM Length L Ch R = 1 ,28879   ,341.7,344.7,341.3
XS GIS Cut Line= 3
2153893.77168599655115.8098898642153760.90535558655363.736034614
2153602.80103147655641.165122722
#Sta/Elev= 30
       0  1528.1    19.7 1520.65    61.3 1507.49    65.1 1505.61    74.2 1497.62
    92.3 1496.39   105.6 1486.25   129.2 1465.15   141.1 1456.74   151.3 1447.77
  171.511440.605   201.2  1439.7     212 1438.14   243.11440.606   253.3 1443.01
   260.2 1445.92   273.8 1448.31   292.2 1449.38   306.3 1447.14   323.2 1447.58
     375 1455.38   425.7 1455.94   444.2 1454.97     497  1457.9   500.9 1459.39
   508.5 1468.41   513.1 1472.42     527 1476.73   555.6 1492.64   600.6 1503.27
#Mann= 5 ,-1,0
       0      .1       0  171.51    .045       0   243.1      .1       0
  301.28     .06       0  451.28      .1       0
Bank Sta=171.51,243.1
XS Rating Curve= 0 ,0
Exp/Cntr=0.3,0.1

Type RM Length L Ch R = 1 ,28535   ,212.4,228.7,236.1
XS GIS Cut Line= 3
2153683.42549895655054.7630909982153503.00322942655144.888378313
2153298.68314169655503.871498222
#Sta/Elev= 30
       0 1475.24    21.5 1465.61    39.4 1461.94    48.3 1458.64    66.2 1454.38
      77 1449.31   124.4 1445.71   132.4 1443.43   147.4 1441.54   195.9 1439.62
   220.4 1440.45   224.5 1439.36   233.3 1434.31     245  1431.9   261.8 1431.55
   288.3 1432.35  299.451434.292   340.1 1444.15   399.9  1442.4   445.9 1445.08
   458.1 1447.12   482.8 1448.04   501.2 1454.57   528.8 1468.67   542.6 1473.58
     561 1477.18   579.4  1477.5     584 1478.56   600.8 1487.81   614.7 1492.65
#Mann= 3 ,-1,0
       0      .1       0   233.3    .045       0  299.45      .1       0
Bank Sta=233.3,299.45
XS Rating Curve= 0 ,0
Exp/Cntr=0.3,0.1

Type RM Length L Ch R = 1 ,28306   ,218.7,262.9,287.2
XS GIS Cut Line= 4
2153625.98147201 654920.662817492153367.22839742 655010.86602061
2153264.68734614655083.2950755212153079.09313846655110.326726894
#Sta/Elev= 30
       0 1474.46    48.5  1459.3    69.7 1458.42    82.4 1455.61   107.8 1448.39
     129  1439.6   136.9 1437.97   167.1  1436.8   188.3 1433.93   209.5 1435.23
   234.9 1433.94   268.7 1435.22   287.6 1435.09   292.5 1433.42   297.4 1429.75
  303.051427.824   321.8    1426     341 1425.68  365.721427.825   370.8  1429.4
   385.5 1440.78   395.5 1446.88   404.1 1449.54   412.2 1453.64   452.6 1458.18
   464.8 1462.02   489.9 1466.59   505.2 1470.76   533.5 1474.37   587.1  1486.9
#Mann= 3 ,-1,0
       0      .1       0  303.05    .045       0  365.72      .1       0
Bank Sta=303.05,365.72
XS Rating Curve= 0 ,0
Exp/Cntr=0.3,0.1

Type RM Length L Ch R = 1 ,28043   ,421.9,396.9,357.5
XS GIS Cut Line= 4
2153616.05188799654815.1249892852153422.34058742654842.631516156
2153294.47570869654782.1356372392153048.40674197654823.783773436
#Sta/Elev= 30
       0 1475.86    40.3 1464.28    48.4 1460.96    65.4 1459.59     117 1450.18
   125.1 1445.96   133.2 1443.28   145.3 1436.83   165.5 1435.18   189.8 1435.19
   202.5 1432.08   215.8 1425.35 232.4141422.934   270.5 1421.12   297.5 1421.44
   308.7    1423   337.1 1429.81   351.6 1430.84   367.8 1436.29   396.2  1441.1
   420.6 1447.18     449 1450.55   461.1 1453.65   472.9 1453.47   485.5 1454.82
   509.8 1461.05   531.5 1469.92   550.4 1473.53   566.6  1481.2   586.7 1481.94
#Mann= 3 ,-1,0
       0      .1       0 232.414    .045       0   308.7      .1       0
Bank Sta=232.414,308.7
XS Rating Curve= 0 ,0
Exp/Cntr=0.3,0.1

Type RM Length L Ch R = 1 ,27646   ,302.5,309.2,311
XS GIS Cut Line= 4
2153518.96426348654389.8469517112153361.26716325654419.714712084
2153160.02874932654515.5897904822152986.86972539 654563.63637652
#Sta/Elev= 30
       0 1466.12    19.1 1459.28      72 1447.11   100.5 1442.75   118.2 1441.17
   141.3  1440.1   161.7  1440.3   170.6 1439.09   192.4 1431.61   197.2 1428.36
   207.4 1418.41  213.26 1414.63     229 1413.72   264.5 1414.64   294.6  1414.3
     312 1421.03   321.2    1422   334.5 1426.38   356.7 1437.47   365.5 1439.99
   383.2    1442   391.6 1446.21   424.8 1446.92   437.2 1452.11   466.3 1460.37
   495.1 1470.86   507.8 1476.62   520.2 1480.73   547.5 1494.24   563.1 1500.23
#Mann= 3 ,-1,0
       0      .1       0  213.26    .045       0   264.5      .1       0
Bank Sta=213.26,264.5
XS Rating Curve= 0 ,0
Exp/Cntr=0.3,0.1

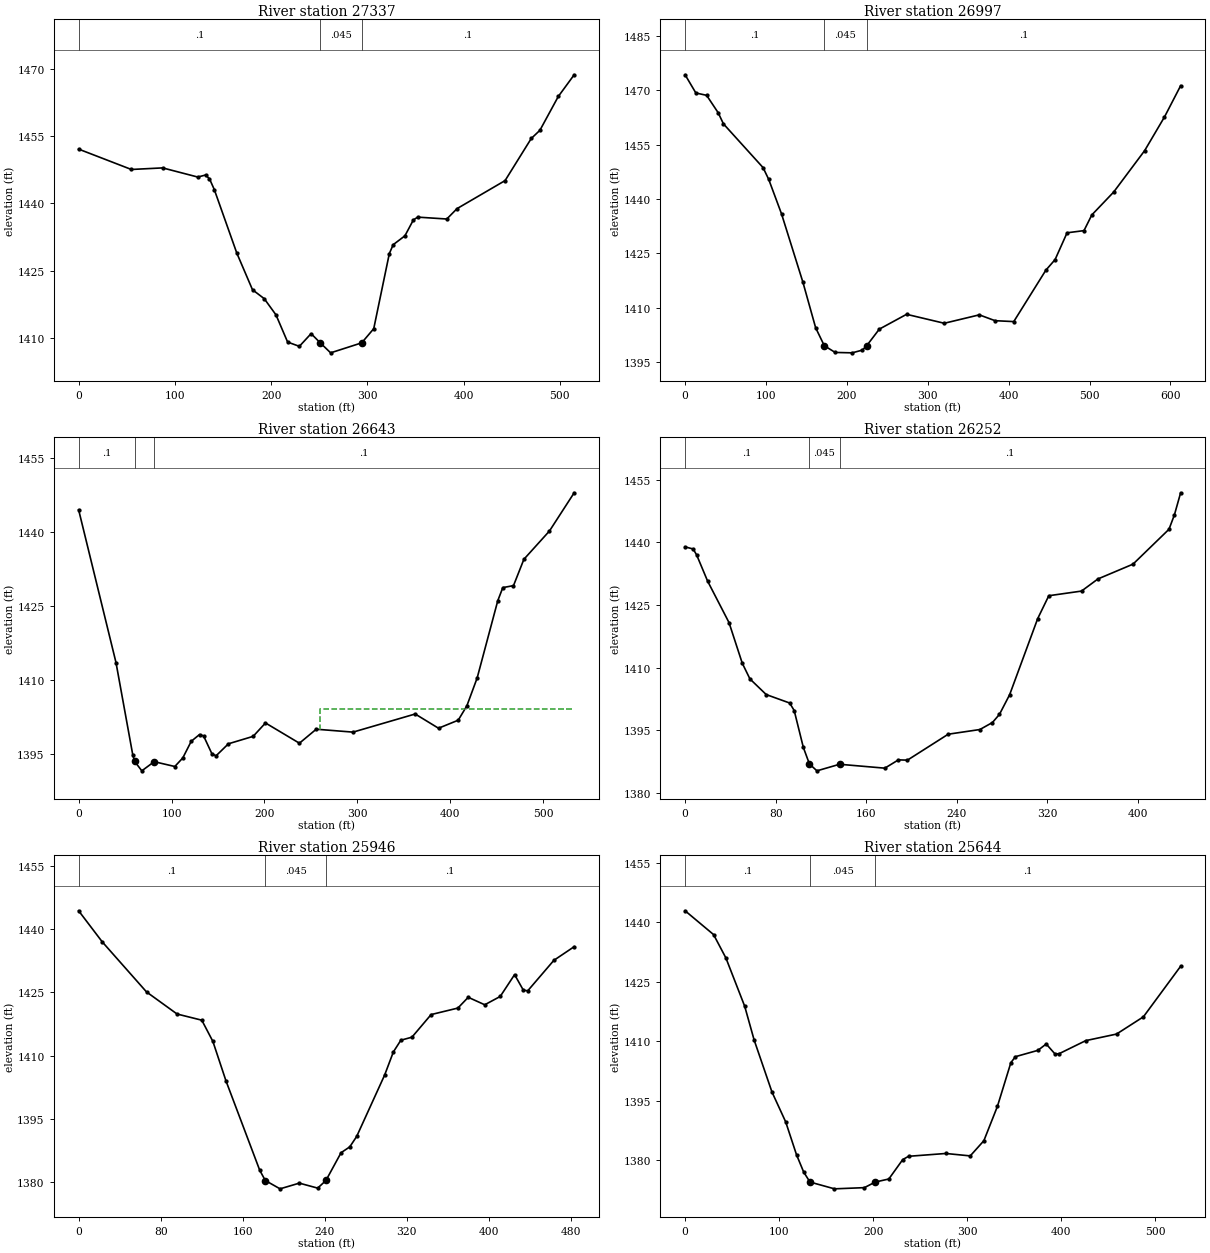
Type RM Length L Ch R = 1 ,27337   ,339.6,339.7,328.5
XS GIS Cut Line= 3
2153450.09569932      654131.626 2153113.8705294654191.160662305
2152960.84456865 654272.92059258
#Sta/Elev= 30
       0  1452.1    54.8 1447.56    87.3 1447.91   123.8 1445.87   131.9 1446.32
     136 1445.48     141 1443.07   164.4  1428.9   180.7 1420.73   192.9 1418.74
   205.1 1415.13   217.2 1409.06   229.4 1408.11   241.6 1410.94  251.221408.869
   261.9 1406.66  294.171408.886   306.7 1412.05   322.9  1428.8   326.9 1430.78
   339.1 1432.76   347.9 1436.31   352.4 1436.93   382.6 1436.51   393.3 1438.83
   443.2 1445.08   470.4 1454.47   479.4  1456.3   498.5 1463.84     515 1468.68
#Mann= 3 ,-1,0
       0      .1       0  251.22    .045       0  294.17      .1       0
Bank Sta=251.22,294.17
XS Rating Curve= 0 ,0
Exp/Cntr=0.3,0.1

Type RM Length L Ch R = 1 ,26997   ,356.1,354.7,331.4
XS GIS Cut Line= 4
2153316.50615878653736.1863411732153239.36165266653832.322344172
2153094.31224313653879.3377784452152836.88192158654096.591701971
#Sta/Elev= 30
       0 1474.31    13.3 1469.29    26.6 1468.64    40.8 1463.87    47.4 1460.77
    96.4 1448.69   103.4 1445.43   119.2 1435.94   145.6 1417.11   161.4  1404.5
  172.081399.565   185.5  1397.7   206.5 1397.59   219.1 1398.34   224.51399.568
   240.1 1404.13   273.8 1408.22   320.4 1405.75   363.7 1408.07   383.2 1406.46
   406.3 1406.21     446  1420.4   457.4 1423.32   472.2 1430.71   493.1 1431.31
   502.8 1435.64   529.8 1441.95   568.1 1453.38   592.6 1462.66   612.6 1471.29
#Mann= 3 ,-1,0
       0      .1       0  172.08    .045       0   224.5      .1       0
Bank Sta=172.08,224.5
XS Rating Curve= 0 ,0
Exp/Cntr=0.3,0.1

Type RM Length L Ch R = 1 ,26643   ,392.8,390.8,379.7
XS GIS Cut Line= 3
 2153056.5788301653507.954818826  2152969.046496653689.757897477
2152738.80343089653928.297138229
#Sta/Elev= 30
       0 1444.47    40.2 1413.47    58.2 1394.79   60.251393.402      68 1391.48
    81.3 1393.34   103.5 1392.36   112.1  1394.1   121.2 1397.48   130.1 1398.85
   134.5 1398.56   143.4 1394.96   147.9 1394.53   161.2 1396.97   187.8 1398.48
   201.1  1401.2   237.6 1397.09   255.7 1399.93   295.3 1399.34   362.2 1403.02
   387.3 1400.13   408.5 1401.76   417.8 1404.67   428.9 1410.34   451.1 1426.03
   456.5 1428.68     468 1429.08   479.2 1434.43   506.7 1440.17   533.3 1447.93
#Mann= 3 ,-1,0
       0      .1       0   60.25    .045       0    81.3      .1       0
#XS Ineff= 2 , 0
                           260.1         1404.11
Permanent Ineff=
       F       F
Bank Sta=60.25,81.3
XS Rating Curve= 0 ,0
Exp/Cntr=0.3,0.1

Type RM Length L Ch R = 1 ,26252   ,298.2,306.3,320.6
XS GIS Cut Line= 4
2152693.88999346653435.3162353452152646.25502148653505.845925682
2152652.67992158653691.2942374972152558.84585186653829.765466213
#Sta/Elev= 30
       0 1438.89     7.1 1438.39    10.2 1436.97    19.9  1430.7    38.8 1420.79
    50.5 1411.08    57.3 1407.31    71.7 1403.57    92.4 1401.55    96.4 1399.76
   104.5 1390.92  109.86 1386.98   116.5 1385.33   136.5  1386.9   176.5 1385.97
   188.5 1387.95   196.5 1387.89   232.5 1394.09   260.5 1395.21   271.6 1396.89
   277.8 1398.84   286.8 1403.54   311.6 1421.75   321.4 1427.21   350.3 1428.32
   364.8 1431.22   395.8 1434.76   427.6  1443.1   432.4 1446.55   437.9 1451.83
#Mann= 3 ,-1,0
       0      .1       0  109.86    .045       0   136.5      .1       0
Bank Sta=109.86,136.5
XS Rating Curve= 0 ,0
Exp/Cntr=0.3,0.1

Type RM Length L Ch R = 1 ,25946   ,297,301.8,272.7
XS GIS Cut Line= 3
2152548.52537471653244.1092723592152309.92953594653508.012723336
2152266.36881484653627.782838771
#Sta/Elev= 30
       0  1444.3      23 1436.95    66.2 1425.09      96 1419.86   120.1  1418.4
   130.9 1413.38   143.7 1404.02   176.6 1382.87  182.031380.454   196.4 1378.48
   215.2 1379.83   233.1 1378.65  241.141380.457   255.9 1387.03   264.4 1388.42
   271.1 1390.87   298.4 1405.42   306.9 1410.89   314.2 1413.66     325 1414.38
   343.7 1419.73   369.8 1421.27   379.9 1423.82     396 1422.05   411.1 1424.02
   425.1 1429.19   433.6 1425.52   437.9 1425.35   463.4 1432.57   483.2  1435.8
#Mann= 3 ,-1,0
       0      .1       0  182.03    .045       0  241.14      .1       0
Bank Sta=182.03,241.14
XS Rating Curve= 0 ,0
Exp/Cntr=0.3,0.1

Type RM Length L Ch R = 1 ,25644   ,363.3,349,297.7
XS GIS Cut Line= 3
2152319.07429414653067.9051350612152105.03771856653392.402997559
 2152077.6129499653528.002409572
#Sta/Elev= 30
       0 1442.86    30.3 1436.86    43.4 1430.97    63.4  1418.8    73.4 1410.32
    92.4 1397.19     107 1389.66   118.5 1381.39   126.1 1377.04   132.81374.503
   158.9 1372.79   190.7 1373.09  202.261374.503   216.7 1375.27   231.5 1380.16
   237.7 1380.99   277.3  1381.7   303.3 1381.09   317.8 1384.92   332.2 1393.56
   346.5 1404.57   351.3 1406.09   375.3 1407.69   384.1 1409.29   393.5 1406.77
   397.7 1406.83   426.2 1410.14   458.9 1411.79   487.5 1416.14   527.1 1428.88
#Mann= 3 ,-1,0
       0      .1       0   132.8    .045       0  202.26      .1       0
Bank Sta=132.8,202.26
XS Rating Curve= 0 ,0
Exp/Cntr=0.3,0.1