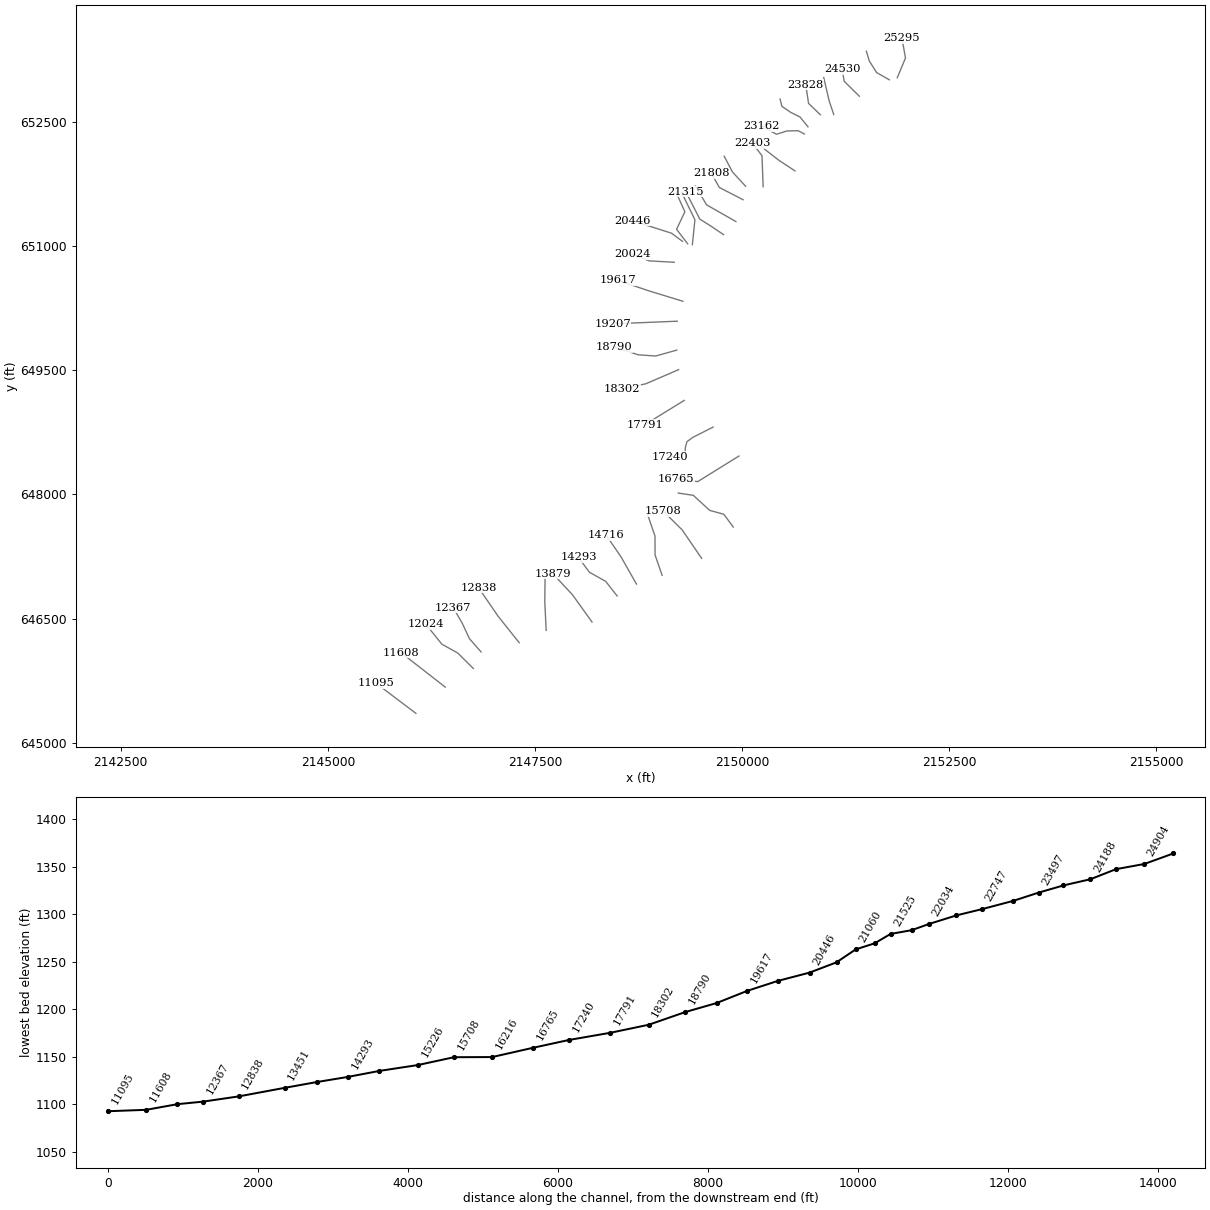
HEC-RAS study LIKANARV.prj: LIKANARV

--- LIKANARV.g01 (geometry) --- (continued)

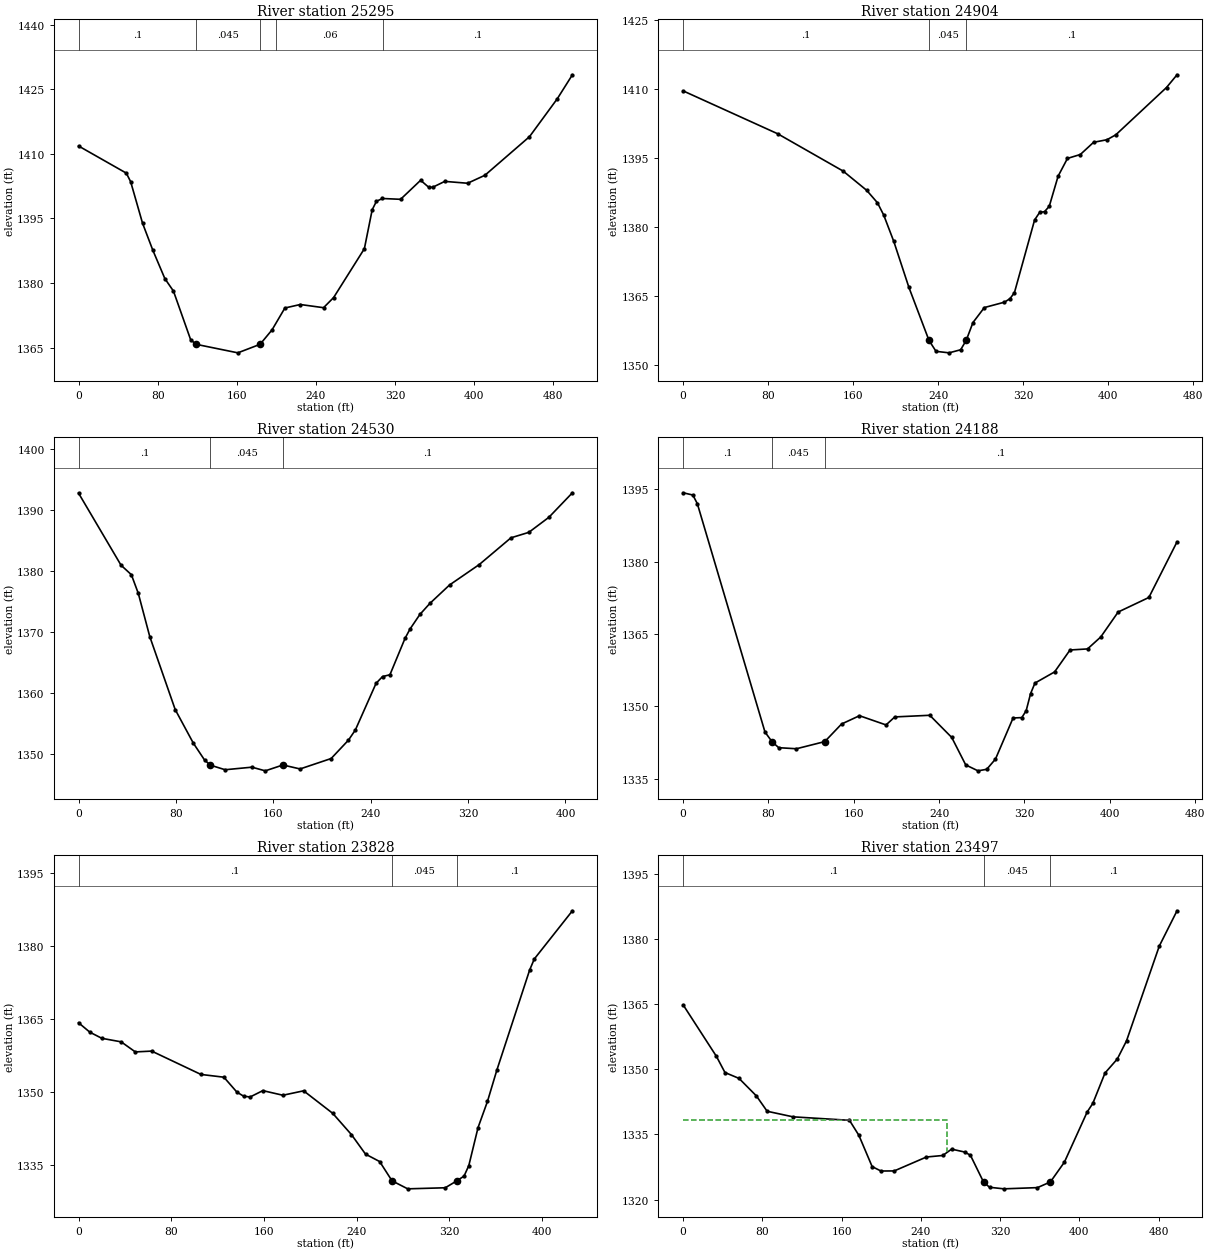
Type RM Length L Ch R = 1 ,25295   ,352.8,390.3,400.1
XS GIS Cut Line= 3
2151871.20003486653028.6052571232151970.88237256653266.874076267
2151928.14442266653504.239649221
#Sta/Elev= 30
       0 1411.82    48.3 1405.52    52.7 1403.53    64.7 1393.91    75.1 1387.64
    87.3 1381.03      96 1378.13   113.4 1366.84  118.89 1365.78   161.1  1363.8
   183.61365.779   195.7 1369.13   208.7 1374.21   224.3 1375.02   247.8 1374.28
     258 1376.64   289.1 1387.98     297 1397.02   301.3 1398.98   307.3 1399.63
   325.7 1399.44     346 1403.86   354.1 1402.25   358.2 1402.24   370.4  1403.6
   393.5 1403.17     411 1405.02   456.1 1413.98   484.2 1422.78   499.5 1428.35
#Mann= 5 ,-1,0
       0      .1       0  118.89    .045       0   183.6      .1       0
     200     .06       0  308.28      .1       0
Bank Sta=118.89,183.6
XS Rating Curve= 0 ,0
Exp/Cntr=0.3,0.1

Type RM Length L Ch R = 1 ,24904   ,368.4,374.8,377.5
XS GIS Cut Line= 4
2151775.91028105653003.4078627872151622.15695644653091.367359473
2151534.27798644653230.5104855512151498.98663838653348.319769045
#Sta/Elev= 30
       0 1409.66      89 1400.32   150.6 1392.19   172.7 1388.01   182.8 1385.31
   188.7 1382.63   198.2 1376.88   212.4 1366.89  231.281355.357   237.9 1352.96
   250.2 1352.63   261.1  1353.3  266.351355.356   272.7 1359.23   283.4 1362.49
   302.3 1363.66   307.5 1364.42   311.7 1365.73   330.7 1381.57   335.4 1383.19
   340.1 1383.38   344.5 1384.55   352.8 1391.09   361.6 1394.96   373.7 1395.81
   386.2 1398.47   398.8 1399.03   407.1  1400.1   454.8  1410.4   464.7 1413.17
#Mann= 3 ,-1,0
       0      .1       0  231.28    .045       0  266.35      .1       0
Bank Sta=231.28,266.35
XS Rating Curve= 0 ,0
Exp/Cntr=0.3,0.1

Type RM Length L Ch R = 1 ,24530   ,342.2,341.6,320
XS GIS Cut Line= 3
2151413.83089541652805.4145316352151231.29224619652985.689483688
2151204.73118086653132.440015236
#Sta/Elev= 30
       0 1392.78    34.9 1380.96    43.4  1379.4    49.1 1376.33    58.5 1369.26
    79.4 1357.28    94.3 1351.77   103.5 1349.01  108.281348.163   120.4 1347.41
   142.4 1347.83   153.4 1347.23   167.9 1348.19     182 1347.54   207.5 1349.25
   221.7 1352.26   227.4 1353.93   244.4 1361.58   249.7 1362.69   255.8 1362.99
   268.2 1368.96   272.3 1370.49   280.4 1372.88   288.6 1374.69   304.8 1377.72
   329.2 1381.07   355.2 1385.45   369.9 1386.35   386.4 1388.82   405.7 1392.84
#Mann= 3 ,-1,0
       0      .1       0  108.28    .045       0   167.9      .1       0
Bank Sta=108.28,167.9
XS Rating Curve= 0 ,0
Exp/Cntr=0.3,0.1

Type RM Length L Ch R = 1 ,24188   ,348.1,359.7,338.6
XS GIS Cut Line= 3
2151105.19176035652584.5661721612151050.44643574652745.967069726
2150984.02985185 653030.87118516
#Sta/Elev= 30
       0 1394.28     9.1 1393.81    13.3 1392.01    76.7 1344.67    83.3 1342.66
    89.6 1341.42   106.2  1341.2  132.751342.683   148.5 1346.33   165.3 1348.05
   190.2 1346.14   198.4  1347.8   231.2 1348.14   251.8 1343.54   264.9 1337.85
   276.4 1336.62   284.6 1336.94   292.8 1339.06   309.3 1347.58   317.5 1347.66
   321.6 1349.11   325.7 1352.63   329.8 1354.82   348.2 1357.13   362.7 1361.68
   379.1  1361.9   391.5 1364.38   407.8 1369.55   436.6 1372.57     463  1384.1
#Mann= 3 ,-1,0
       0      .1       0    83.3    .045       0  132.75      .1       0
Bank Sta=83.3,132.75
XS Rating Curve= 0 ,0
Exp/Cntr=0.3,0.1

Type RM Length L Ch R = 1 ,23828   ,290.9,331.5,341.3
XS GIS Cut Line= 3
 2150942.6795843652582.3979608332150800.77506472652719.176166652
2150766.93734904652945.626235259
#Sta/Elev= 30
       0 1364.26     9.8 1362.31    20.1 1361.06    36.8 1360.33      49 1358.26
    63.1 1358.43   105.6 1353.63   125.4 1353.06   136.6    1350   142.4 1349.16
     148 1348.99     159  1350.3   176.3 1349.35   194.2 1350.26   219.3 1345.63
   235.5 1341.24   247.6 1337.24   259.8 1335.71  270.46 1331.75     284  1330.1
   316.4 1330.32  326.421331.751   332.6 1332.72   336.7 1334.87   344.7 1342.71
   352.8 1348.07   360.9 1354.51   389.2  1375.1   393.2 1377.37   426.1 1387.29
#Mann= 3 ,-1,0
       0      .1       0  270.46    .045       0  326.42      .1       0
Bank Sta=270.46,326.42
XS Rating Curve= 0 ,0
Exp/Cntr=0.3,0.1

Type RM Length L Ch R = 1 ,23497   ,283.7,335.1,333.9
XS GIS Cut Line= 5
2150794.26964115652435.9489078762150696.24642551652556.056045089
2150588.21123379652609.1741146472150478.66790632652683.621036227
2150457.19243533652771.780276457
#Sta/Elev= 30
       0  1364.8    33.6 1352.96    42.2 1349.25    56.4  1347.9    73.9 1343.88
    84.8 1340.34   110.9 1339.06   167.9 1338.26   177.4 1334.81   190.8 1327.61
   199.7  1326.6   213.1 1326.62   245.6 1329.82   262.1 1330.17     271 1331.63
   284.1 1330.97     290 1330.23  303.221324.085   309.3 1322.86   323.8  1322.5
   357.7 1322.78  370.751324.084   384.9 1328.64   407.9 1340.18   413.6 1342.16
   425.9 1349.14   438.3 1352.36   447.6 1356.53   480.7 1378.34   498.6 1386.45
#Mann= 3 ,-1,0
       0      .1       0  303.22    .045       0  370.75      .1       0
#XS Ineff= 2 , 0
          266.71 1338.33
Permanent Ineff=
       F       F
Bank Sta=303.22,370.75
XS Rating Curve= 0 ,0
Exp/Cntr=0.3,0.1

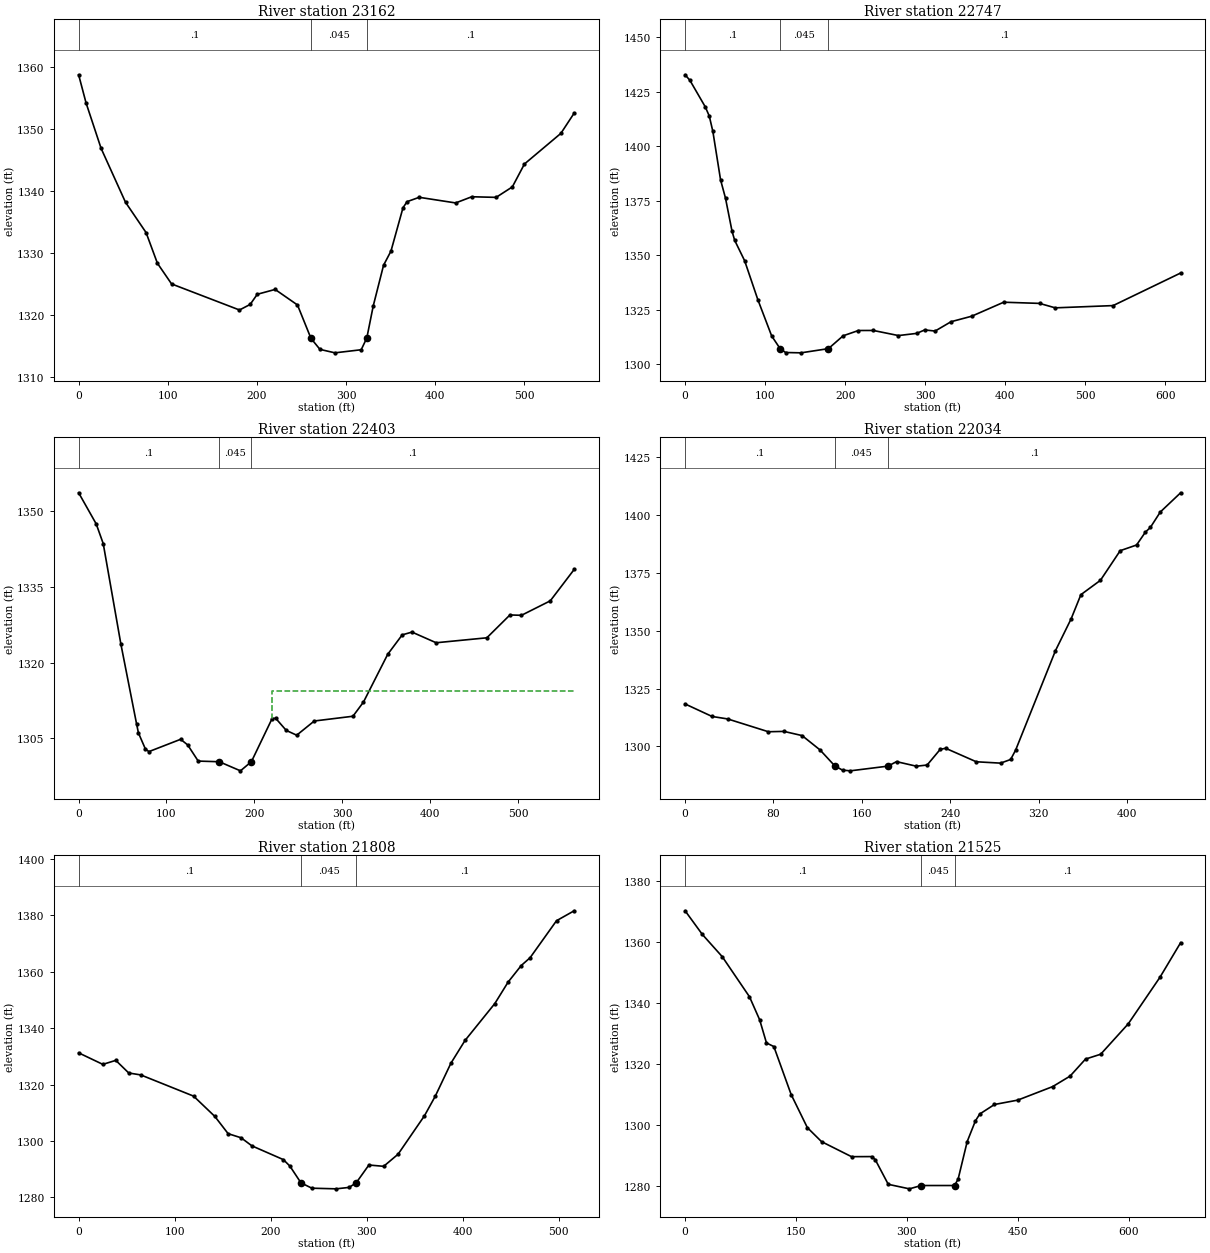
Type RM Length L Ch R = 1 ,23162   ,434.6,414.6,381.9
XS GIS Cut Line= 5
2150750.42040698652349.2139103212150675.79750266652389.524670159
 2150539.4652292652386.3088768952150414.41679581652346.583278653
2150235.03136885652443.096646262
#Sta/Elev= 30
       0 1358.82     8.3 1354.29    25.2 1346.94    52.6 1338.23    75.7 1333.33
    88.4 1328.38   104.3 1325.04   180.5 1320.83   192.5 1321.73   200.5 1323.37
   220.5 1324.15   245.6 1321.64260.72731316.248   270.8 1314.47   287.6 1313.91
   317.1 1314.41   323.4 1316.31   330.6 1321.48   342.2 1328.06   350.5 1330.34
     364 1337.34   368.6 1338.33   382.2 1339.03   423.1 1338.12   441.2 1339.12
   468.5 1339.02   486.7 1340.71   500.3 1344.41   541.2 1349.36   556.1 1352.63
#Mann= 3 ,-1,0
       0      .1       0260.7273    .045       0   323.4      .1       0
Bank Sta=260.7273,323.4
XS Rating Curve= 0 ,0
Exp/Cntr=0.3,0.1

Type RM Length L Ch R = 1 ,22747   ,366.1,344.1,316.2
XS GIS Cut Line= 3
2150637.19805879 651904.307601982150445.08242941 652030.61488825
2150137.54258041652269.239605871
#Sta/Elev= 30
       0 1432.72       6 1430.18    25.2 1418.01    30.2 1413.81    34.7 1406.73
    44.3 1384.58    50.5  1376.1    58.7 1360.91      62 1356.78    74.4 1347.46
    90.9  1329.6   108.2 1312.95  118.721307.159   125.6 1305.38   144.8 1305.23
  179.091307.158   197.5 1313.05   216.6 1315.47   235.2 1315.49   266.6 1313.15
   289.4 1314.15   299.4 1315.73   312.4 1315.22   332.3  1319.5   358.1 1322.02
   398.1 1328.44   442.9  1327.9   462.5 1325.86   534.8 1326.89   619.2 1341.83
#Mann= 3 ,-1,0
       0      .1       0  118.72    .045       0  179.09      .1       0
Bank Sta=118.72,179.09
XS Rating Curve= 0 ,0
Exp/Cntr=0.3,0.1

Type RM Length L Ch R = 1 ,22403   ,348.7,368.9,380
XS GIS Cut Line= 3
 2150252.8262374651713.154354615 2150238.8833813652087.811493042
2150123.54544082652237.685659978
#Sta/Elev= 30
       0 1353.59      20 1347.43      28 1343.53    48.1 1323.64    65.9 1307.91
    68.1 1306.06    76.1 1302.85    80.1 1302.39   116.1 1304.82   124.1 1303.71
   136.1 1300.51   160.1 1300.38   184.2 1298.58  196.681300.405   220.2 1308.92
   224.2 1308.99   236.3 1306.58   248.2 1305.63   268.2 1308.44   312.2 1309.38
   324.2 1312.19   351.8 1321.64   368.3 1325.48   379.4 1326.03   406.9 1323.92
   464.6  1324.9   490.9 1329.42     504 1329.35   536.8 1332.21     564 1338.42
#Mann= 3 ,-1,0
       0      .1       0   160.1    .045       0  196.68      .1       0
#XS Ineff= 2 , 0
                          220.42         1314.33
Permanent Ineff=
       F       F
Bank Sta=160.1,196.68
XS Rating Curve= 0 ,0
Exp/Cntr=0.3,0.1

Type RM Length L Ch R = 1 ,22034   ,218.8,226.5,236.4
XS GIS Cut Line= 3
2150040.93247463651719.4459190552149883.18353086651890.017015085
 2149782.5139657652081.466167351
#Sta/Elev= 30
       0 1318.36    24.4 1312.96    38.6 1311.88    75.4 1306.35    89.5  1306.5
   105.9 1304.69   122.2 1298.47  135.531291.586   142.5 1289.76   149.5 1289.45
   183.7 1291.49   191.4 1293.43   209.4 1291.45   219.1 1291.96     231 1298.76
   235.9  1299.2   263.6 1293.37   285.6 1292.78   294.7 1294.36   299.2 1298.39
   335.3 1341.42   349.5  1355.2   358.3 1365.61     376 1371.82   393.9 1384.63
   408.7 1387.08   416.7 1392.65   421.2 1394.68   430.2 1401.35   448.6 1409.66
#Mann= 3 ,-1,0
       0      .1       0  135.53    .045       0   183.7      .1       0
Bank Sta=135.53,183.7
XS Rating Curve= 0 ,0
Exp/Cntr=0.3,0.1

Type RM Length L Ch R = 1 ,21808   ,278.2,282.9,269.6
XS GIS Cut Line= 3
2150010.61852779651556.4736381062149724.25246058 651703.94043235
2149629.50229733651873.206285575
#Sta/Elev= 30
       0 1331.27    25.2 1327.18    38.7  1328.6    52.2 1324.12    64.7 1323.44
   119.7 1315.92   141.9  1308.7   155.7  1302.6   169.2 1301.14   180.5 1298.27
   213.2  1293.4     220 1291.11  231.54 1285.16   242.9 1283.26   268.2 1283.03
   281.7 1283.54  289.061285.157   302.3 1291.48   317.7 1291.02   332.7 1295.31
   360.2 1308.96   371.4 1315.87   387.7 1327.57   402.4 1335.65   433.5 1348.77
   447.3 1356.37     461 1362.25   470.2 1365.01   497.7 1378.13   516.1 1381.66
#Mann= 3 ,-1,0
       0      .1       0  231.54    .045       0  289.06      .1       0
Bank Sta=231.54,289.06
XS Rating Curve= 0 ,0
Exp/Cntr=0.3,0.1

Type RM Length L Ch R = 1 ,21525   ,209.2,210.2,205.3
XS GIS Cut Line= 3
2149923.85886162651293.0849778342149569.89786162651494.764977834
2149436.12463042 651721.30456876
#Sta/Elev= 30
       0 1370.33    23.3 1362.57    50.3 1355.25    87.1 1342.11   100.9 1334.53
   110.1 1326.94   120.1 1325.75   143.5    1310   165.4 1299.14   184.6 1294.54
   225.2  1289.6   252.8 1289.63   257.4 1288.57   274.9 1280.52   303.5 1279.04
   319.5 1280.13  364.52 1280.13   369.4 1282.21   381.7 1294.56   392.8 1301.34
   398.7 1303.61   418.6 1306.73   450.1 1308.17   497.3  1312.6   520.9 1316.05
   541.8 1321.64   562.3 1323.23   599.6 1333.21   642.5 1348.49   670.5 1359.86
#Mann= 3 ,-1,0
       0      .1       0   319.5    .045       0  364.52      .1       0
Bank Sta=319.5,364.52
XS Rating Curve= 0 ,0
Exp/Cntr=0.3,0.1

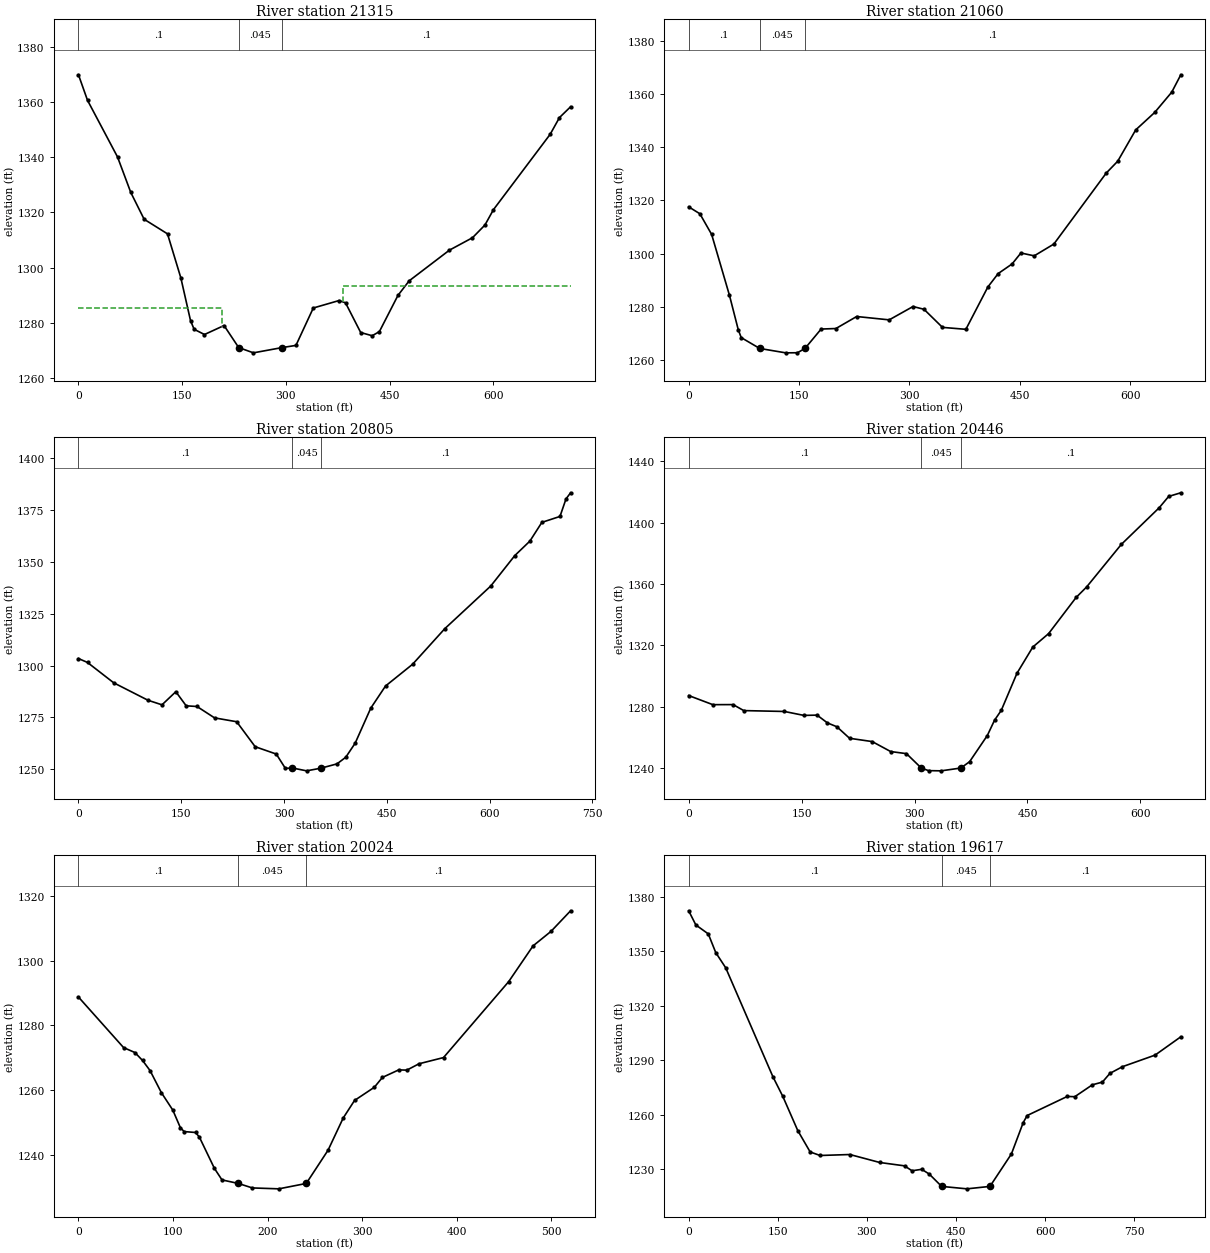
Type RM Length L Ch R = 1 ,21315   ,277.8,254.5,219
XS GIS Cut Line= 4
2149775.02156762651134.9912930252149607.17355303651247.889064746
2149488.28120936651322.8212141182149320.43319477 651651.52357603
#Sta/Elev= 30
       0  1369.8    13.1 1360.56    56.5 1340.08    75.7 1327.23      95 1317.54
   128.8 1312.26   148.1 1296.34   162.1 1280.89   167.3 1277.74   182.3 1275.85
   210.6  1279.1  231.791271.125   253.1 1269.22  294.611271.125   314.6 1271.91
   339.7 1285.44   376.9 1288.13   386.3 1287.32   408.3 1276.56   424.9 1275.41
   435.3  1276.9   462.2 1290.01   478.4 1295.27   536.6 1306.36     570 1310.86
     588 1315.45   600.3 1321.01   682.3 1348.25   695.8 1354.32   711.9 1358.23
#Mann= 3 ,-1,0
       0      .1       0  231.79    .045       0  294.61      .1       0
#XS Ineff= 2 , 0
          207.05 1285.38  382.46         1293.37
Permanent Ineff=
       F       F
Bank Sta=231.79,294.61
XS Rating Curve= 0 ,0
Exp/Cntr(USF)=0,0
Exp/Cntr=0.3,0.1

Type RM Length L Ch R = 1 ,21060   ,259.2,254.8,235.8
XS GIS Cut Line= 3
2149398.61312759651014.1057805172149429.29162011651314.880945582
2149268.60123731651644.195536354
#Sta/Elev= 30
       0 1317.59    15.2 1314.99    31.2 1307.24    55.4 1284.39    67.4 1271.44
    71.4 1268.49   96.531264.415   131.8 1262.77   147.8  1262.8  158.061264.416
     180  1271.7   200.1  1271.9   228.3 1276.41   272.5 1275.15   304.9 1280.16
   319.8 1279.12   344.9 1272.33   376.7  1271.6   406.6  1287.5   420.6 1292.53
   439.5 1296.14   451.5 1300.26   469.6 1299.19   496.3 1303.62   567.5 1330.28
   583.1 1334.73   607.5 1346.47   633.3 1353.02   656.5 1360.65   668.8 1367.17
#Mann= 3 ,-1,0
       0      .1       0   96.53    .045       0  158.06      .1       0
Bank Sta=96.53,158.06
XS Rating Curve= 0 ,0
Exp/Cntr=0.3,0.1

Type RM Length L Ch R = 1 ,20805   ,312.2,359.5,393.5
XS GIS Cut Line= 4
2149341.86209328651024.390517137 2149207.9327159651199.314581722
2149308.04496556651410.8920165562149199.43837175651651.350163218
#Sta/Elev= 30
       0 1303.39    13.2 1301.49    51.4 1291.68   101.5 1283.25   121.9 1281.05
   142.1 1287.38   157.2 1280.57     173 1280.24   198.6 1274.75   230.9 1272.89
   257.9 1260.83   288.7 1257.29     302 1250.36     312 1250.58   332.9 1249.19
   353.8 1250.47   377.3 1252.55   390.1 1255.75   403.8 1262.53   426.6 1279.45
   448.1 1290.12   487.6 1300.62   534.6 1317.79   601.7 1338.39   636.8 1353.08
   658.8 1360.06   676.3  1369.1   702.7 1371.96   711.5 1380.42   718.2 1383.38
#Mann= 3 ,-1,0
       0      .1       0     312    .045       0   353.8      .1       0
Bank Sta=312,353.8
XS Rating Curve= 0 ,0
Exp/Cntr=0.3,0.1

Type RM Length L Ch R = 1 ,20446   ,409.6,421.3,410.1
XS GIS Cut Line= 3
2149278.95902934651054.0224993242149145.87533373651152.850046924
2148680.78368008651300.538972495
#Sta/Elev= 30
       0 1287.36    32.1 1281.42      59 1281.46    73.2 1277.56   127.2 1276.99
   152.9 1274.44   170.6  1274.6   184.3 1269.54   196.9 1267.03   213.7 1259.53
   243.8 1257.39   268.3  1250.9   289.3 1249.53  308.951240.187   318.6 1238.47
   335.4 1238.34  361.611240.186   373.2 1244.32   396.7 1261.34   406.3 1271.32
   415.2 1277.69   436.1 1301.88   457.1 1318.93   478.1 1327.68   514.6 1351.19
   528.5    1358   574.6 1385.71     625 1409.62   637.6 1416.99   653.7 1419.36
#Mann= 3 ,-1,0
       0      .1       0  308.95    .045       0  361.61      .1       0
Bank Sta=308.95,361.61
XS Rating Curve= 0 ,0
Exp/Cntr=0.3,0.1

Type RM Length L Ch R = 1 ,20024   ,401.1,407.1,369.9
XS GIS Cut Line= 3
2149179.77191923 650801.355289062148878.79869727650818.134185904
2148675.33702772650899.215063164
#Sta/Elev= 30
       0 1288.75    47.7 1273.18    59.7 1271.65    67.8  1269.2    75.7  1266.1
    87.7 1259.29    99.8 1253.91   107.8 1248.49   111.8  1247.3   123.8 1247.02
   127.8 1245.65   143.8 1235.96   151.8 1232.41  169.121231.319   183.9 1229.94
   211.9 1229.66  240.941231.322     264 1241.57     280 1251.48     292 1256.89
   312.9 1260.94   321.5 1263.99   338.7  1266.3   347.3 1266.23   360.2 1268.19
   386.1  1270.1     455 1293.49   480.8 1304.51   499.8 1308.98   520.5 1315.32
#Mann= 3 ,-1,0
       0      .1       0  169.12    .045       0  240.94      .1       0
Bank Sta=169.12,240.94
XS Rating Curve= 0 ,0
Exp/Cntr=0.3,0.1

Type RM Length L Ch R = 1 ,19617   ,392.8,410,415.3
XS GIS Cut Line= 3
2149283.75072699650330.9723642812148881.08272699650453.943364281
2148495.13172699650584.654364281
#Sta/Elev= 30
       0 1372.37    12.1 1364.55      33 1359.64    45.6 1349.33    62.3 1340.99
   141.8 1280.97   158.5 1270.12   183.6 1251.35   204.5 1239.54   221.2 1237.59
   271.4 1238.12   321.6 1233.74   363.4 1231.88     376 1229.16   392.3 1229.98
   405.1 1227.33  425.851220.563   468.5 1219.22  507.211220.562   543.3 1238.42
   563.1 1255.62   569.8 1259.59   637.4 1270.12     650 1269.96   679.6 1276.52
   696.5 1278.01   709.2 1282.83   730.3  1286.5   785.2 1292.88   828.5 1302.96
#Mann= 3 ,-1,0
       0      .1       0  425.85    .045       0  507.21      .1       0
Bank Sta=425.85,507.21
XS Rating Curve= 0 ,0
Exp/Cntr=0.3,0.1

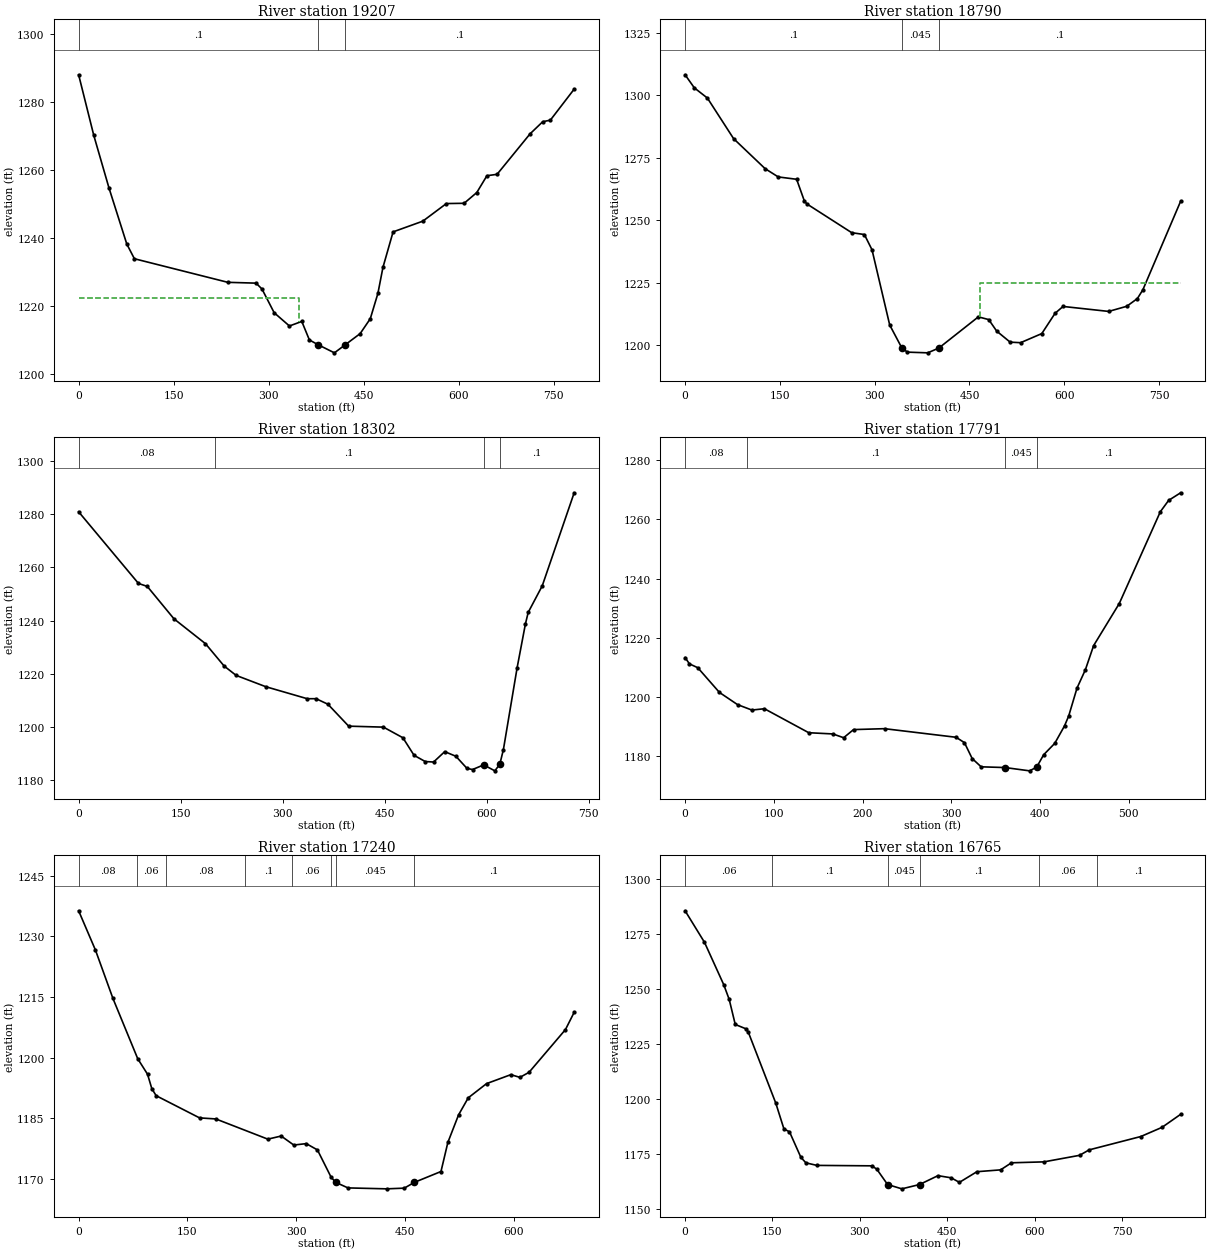
Type RM Length L Ch R = 1 ,19207   ,413.6,416.9,404.4
XS GIS Cut Line= 2
2149216.06890952 650090.234786782148434.59012747 650058.25427065
#Sta/Elev= 30
       0 1288.12    23.9  1270.3    47.9 1254.83      76 1238.34      88 1234.01
   235.5 1227.07   280.1 1226.83   289.4  1225.1   308.6 1218.13   332.7 1214.23
   352.2 1215.57   364.2 1210.12  378.161208.697   403.7 1206.33  420.741208.696
   444.3 1211.98   460.3 1216.36   472.3 1223.79   480.3 1231.47   496.3 1241.91
   543.2 1245.06   580.4 1250.24   608.4 1250.32   628.4 1253.48   644.4 1258.43
   660.4 1258.84   712.5 1270.75   732.5 1274.32   744.5 1274.77   782.1  1283.9
#Mann= 3 ,-1,0
       0      .1       0  378.16    .045       0  420.74      .1       0
#XS Ineff= 2 , 0
          348.53 1222.49
Permanent Ineff=
       F       F
Bank Sta=378.16,420.74
XS Rating Curve= 0 ,0
Exp/Cntr=0.3,0.1

Type RM Length L Ch R = 1 ,18790   ,478.5,488.2,462.6
XS GIS Cut Line= 4
2149210.15975846649741.1559394182148956.31186319649670.291002477
2148746.57463808649684.4465468152148450.91524233649779.228970103
#Sta/Elev= 30
       0 1308.17    14.6 1302.94    35.3 1298.85    76.8 1282.59   126.6  1270.6
   147.4 1267.28   176.5 1266.34   188.9 1257.54   193.1 1256.41   263.7 1244.96
   283.7 1244.23   295.8 1238.12   323.8 1208.01  343.071198.797   351.9 1197.15
     384 1196.87  401.581198.796   464.1 1211.27   480.5 1210.18   493.1 1205.57
   514.4 1201.15   530.9 1200.93   564.5 1204.58   585.5  1212.7   598.1 1215.44
   670.3 1213.45   698.9  1215.5   715.7 1218.58   724.4 1222.09   784.2 1257.55
#Mann= 3 ,-1,0
       0      .1       0  343.07    .045       0  401.58      .1       0
#XS Ineff= 2 , 0
                             467         1224.94
Permanent Ineff=
       F       F
Bank Sta=343.07,401.58
XS Rating Curve= 0 ,0
Exp/Cntr=0.3,0.1

Type RM Length L Ch R = 1 ,18302   ,499.7,510.9,508
XS GIS Cut Line= 3
2149232.95818175649505.6010582182148836.00318175649334.646058218
2148546.20593942649271.181630204
#Sta/Elev= 30
       0 1280.87      88 1253.94     101 1252.81   140.2 1240.64   186.6 1231.28
     214 1222.89   231.7 1219.36   275.2 1215.12   336.2  1210.6   349.3  1210.6
   366.7 1208.52   397.2 1200.28   448.4 1199.91     477 1195.91   493.4 1189.31
   509.8 1186.98   522.1 1186.79   538.5  1190.7   554.9 1188.96   571.2 1184.41
   579.4 1183.97   595.8 1185.72   612.2 1183.48  619.511185.942   624.8 1191.48
     645 1222.26   657.2 1238.72   661.3 1243.06   681.9 1253.01   728.9 1288.02
#Mann= 4 ,-1,0
       0     .08       0     200      .1       0   595.8    .045       0
  619.51      .1       0
Bank Sta=595.8,619.51
XS Rating Curve= 0 ,0
Exp/Cntr=0.3,0.1

Type RM Length L Ch R = 1 ,17791   ,490.1,551.2,556
XS GIS Cut Line= 2
2149300.33466719649134.2963335962148824.71318411648841.420607398
#Sta/Elev= 30
       0 1213.32     4.9 1211.19    14.3 1209.89    38.7 1201.54    59.1 1197.42
    75.3 1195.58    89.4 1196.03   139.4 1187.92   166.6 1187.51   178.7 1186.23
   189.9 1188.98   224.8 1189.29   305.5 1186.38   314.9 1184.56   323.6  1179.2
   333.7  1176.4   360.7 1176.15   388.3 1175.04   396.3 1176.28   404.2 1180.48
   416.7 1184.33   427.7 1190.23   432.4 1193.57   441.8 1203.02   451.2 1209.19
   460.5 1217.36   489.4 1231.57   535.7  1262.6   545.1 1266.45   558.6 1269.01
#Mann= 4 ,-1,0
       0     .08       0      70      .1       0   360.7    .045       0
   396.3      .1       0
Bank Sta=360.7,396.3
XS Rating Curve= 0 ,0
Exp/Cntr=0.3,0.1

Type RM Length L Ch R = 1 ,17240   ,493.7,475.5,429.6
BEGIN DESCRIPTION:
XS overtop dirt road
END DESCRIPTION:
XS GIS Cut Line= 6
2149648.84978836648812.1430904792149404.66541388648688.401646083
2149332.92114808648636.1134523612149313.46507599648564.369186556
2149311.03306698648506.000970309 2149132.6971206648450.797086045
#Sta/Elev= 30
       0 1236.32    23.2 1226.59    47.3 1214.62    81.5 1199.69      95 1195.86
   100.9 1192.29   106.9 1190.55   166.7 1185.06   189.1  1184.8   260.8  1179.8
   279.2 1180.57   296.6 1178.34   313.8 1178.69   329.2 1177.13   348.2 1170.32
  354.721169.079   371.3 1167.73   424.5  1167.5   448.9 1167.67  462.55 1169.08
   499.5 1171.79     509    1179   523.8 1185.83   537.1 1190.03   562.3 1193.54
   595.8 1195.76   608.3 1195.09   620.9 1196.34   671.1 1206.92   683.1 1211.19
#Mann= 8 ,-1,0
       0     .08       0      80     .06       0     120     .08       0
     230      .1       0  293.75     .06       0  348.51      .1       0
  354.72    .045       0  462.55      .1       0
Bank Sta=354.72,462.55
XS Rating Curve= 0 ,0
Exp/Cntr=0.3,0.1

Type RM Length L Ch R = 1 ,16765   ,567.5,549,513.7
XS GIS Cut Line= 3
2149960.50224312648462.5230605822149461.68606373648153.520425651
2149200.55787962648191.585694725
#Sta/Elev= 30
       0 1285.49    33.3 1271.17    66.3 1251.97    75.7 1245.28    86.1  1233.9
   103.9 1231.98   108.6 1230.35   155.7 1198.18   169.7 1186.46   179.2  1185.2
   198.8 1173.58   207.4  1171.1   226.2 1169.94   320.8 1169.74   329.2 1168.18
  347.611161.256   372.1  1159.3  402.461161.255   434.1 1165.28   456.8  1164.3
   470.9 1162.24     501 1167.08   541.6 1167.91   560.3 1171.12     616 1171.54
   677.2 1174.51   693.6 1176.98   782.3 1183.04   818.7  1187.2   850.7 1193.12
#Mann= 6 ,-1,0
       0     .06       0     150      .1       0  347.61    .045       0
  402.46      .1       0  606.77     .06       0  706.77      .1       0
Bank Sta=347.61,402.46
XS Rating Curve= 0 ,0
Exp/Cntr=0.3,0.1

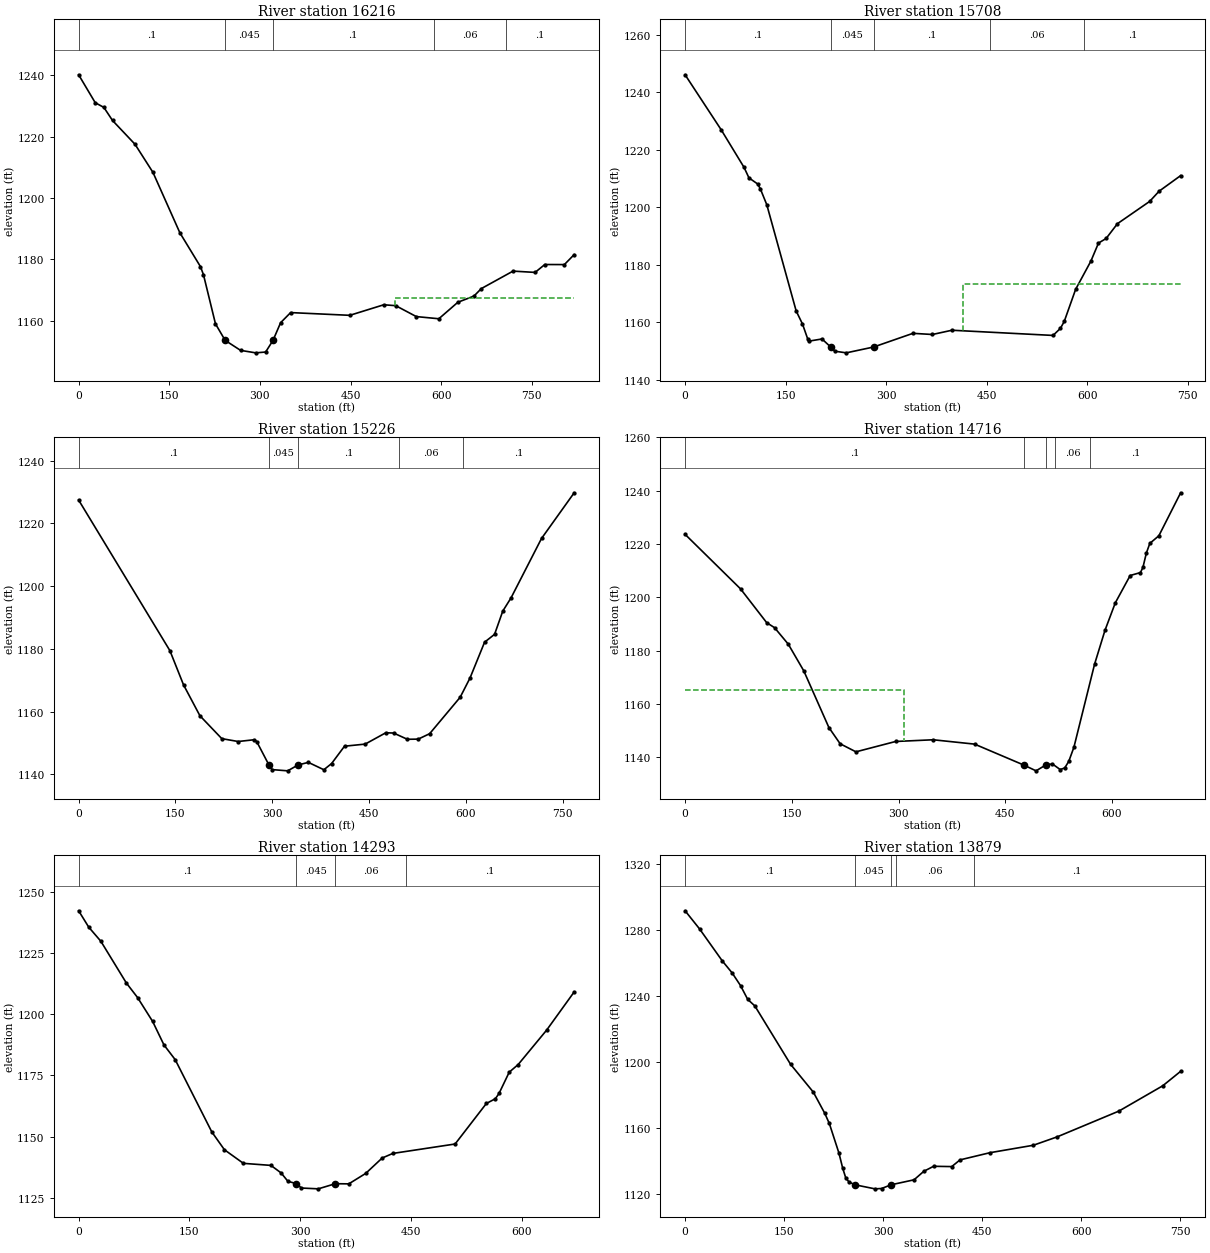
Type RM Length L Ch R = 1 ,16216   ,524.7,507.5,468.9
XS GIS Cut Line= 5
2149891.88928702647606.3873556272149777.44948709647760.595455706
2149608.25867962647806.7913855242149409.35331086647988.689240123
2149228.11373942648015.947413845
#Sta/Elev= 30
       0 1240.14    27.5 1231.03    41.8  1229.5    56.1 1225.24    93.3 1217.49
     123 1208.33   167.6 1188.62   201.6 1177.62   206.6    1175   226.5 1158.95
  242.511153.568     268 1150.31   292.9  1149.5   309.5 1149.76  321.751153.568
   334.3 1159.32   350.9 1162.62   448.8 1161.73   505.1 1165.17   524.9 1164.87
   558.9 1161.32   596.2 1160.61   627.7 1165.99   654.3    1168   666.5 1170.44
     719 1176.14   755.5 1175.72   771.6 1178.29     804 1178.27   820.2 1181.52
#Mann= 5 ,-1,0
       0      .1       0  242.51    .045       0  321.75      .1       0
  587.42     .06       0  706.95      .1       0
#XS Ineff= 2 , 0
                          523.93         1167.49
Permanent Ineff=
       F       F
Bank Sta=242.51,321.75
XS Rating Curve= 0 ,0
Exp/Cntr=0.3,0.1

Type RM Length L Ch R = 1 ,15708   ,482.4,482.3,435.3
XS GIS Cut Line= 3
2149510.01558805647228.5951930752149275.37639277647571.461311722
 2149045.0349742 647799.41359764
#Sta/Elev= 30
       0 1246.16      54 1226.95      88 1213.91    95.3 1210.26   108.2 1208.15
   112.2  1206.5   121.9 1200.92   165.8 1163.89   175.2 1159.37     183 1154.16
   184.9 1153.42   204.3 1154.17  217.241151.378   223.3 1149.91   240.6 1149.34
  281.411151.377     340 1156.13   369.1 1155.73   398.2 1157.21   549.1  1155.4
   560.1 1157.87   565.8 1160.27   582.8 1171.45   605.6 1181.29   616.9 1187.56
   628.3 1189.16   645.2 1194.31   693.3 1202.07   707.4 1205.63   739.5 1211.05
#Mann= 5 ,-1,0
       0      .1       0  217.24    .045       0  281.41      .1       0
  455.47     .06       0  595.47      .1       0
#XS Ineff= 2 , 0
                          414.67          1173.2
Permanent Ineff=
       F       F
Bank Sta=217.24,281.41
XS Rating Curve= 0 ,0
Exp/Cntr=0.3,0.1

Type RM Length L Ch R = 1 ,15226   ,494.8,510.3,509.2
XS GIS Cut Line= 4
2149033.36161164647023.6334001552148948.01951141647269.606941779
2148947.67744234647495.1071474942148856.54324391647761.816044217
#Sta/Elev= 30
       0 1227.48   141.4 1179.43   162.5 1168.52   187.9 1158.66   221.8 1151.35
   247.2 1150.44   271.9    1151   275.9 1150.41   294.71143.005   299.9 1141.47
   323.9 1141.08   339.9 1142.95   355.9 1143.78   379.9 1141.43   391.9 1143.41
   411.9 1148.94   443.9 1149.61   475.9 1153.23     488 1153.14   509.2 1151.15
   526.1  1151.2   543.8 1152.93   591.1 1164.56   606.4 1170.73   628.9 1182.13
   644.4 1184.64   657.1 1192.05   669.9 1196.27   717.1 1215.22   767.7  1229.8
#Mann= 5 ,-1,0
       0      .1       0   294.7    .045       0   339.9      .1       0
  495.86     .06       0  595.86      .1       0
Bank Sta=294.7,339.9
XS Rating Curve= 0 ,0
Exp/Cntr=0.3,0.1

Type RM Length L Ch R = 1 ,14716   ,406.7,422.8,419.7
XS GIS Cut Line= 3
     2148723.813      646917.4092148536.37214886647247.387913772
2148357.43906263647508.944827543
#Sta/Elev= 30
       0 1223.62    77.9 1203.18   114.7 1190.49   125.7 1188.63     145 1182.44
   166.8 1172.43   202.1 1151.17   217.9 1145.09   240.1 1142.07   295.9 1145.95
   348.7 1146.59   406.8 1144.96   475.9 1137.12   493.2 1134.94  507.121137.177
   516.2 1137.52   527.1 1135.43   533.5 1136.02   539.2 1138.51   546.4 1143.77
   575.5 1174.98   590.1 1187.65   604.6 1197.95   625.5 1208.19   639.9 1209.29
   643.4 1211.21   648.2 1216.58   653.1 1220.23   665.8 1223.09   696.4 1239.21
#Mann= 5 ,-1,0
       0      .1       0   475.9    .045       0  507.12      .1       0
   519.5     .06       0   569.5      .1       0
#XS Ineff= 2 , 0
          307.48 1165.44
Permanent Ineff=
       F       F
Bank Sta=475.9,507.12
XS Rating Curve= 0 ,0
Exp/Cntr=0.3,0.1

Type RM Length L Ch R = 1 ,14293   ,417.7,413.8,392
XS GIS Cut Line= 4
 2148490.8259742646774.4124789942148352.48177451646949.941076634
2148155.13805982647060.6120840892148024.14043037647239.334790716
#Sta/Elev= 30
       0 1242.45    13.7 1235.74    30.1 1229.97    64.6  1212.9    79.9 1206.89
   100.3 1197.11   115.6 1187.51   130.8 1181.49   180.4 1151.89   197.5 1144.59
   223.2 1139.02   260.5 1138.18   274.3  1135.1   283.5 1131.66  295.14  1130.7
   301.8 1128.91   324.7 1128.58   347.7 1130.68     366 1130.62   388.9  1134.9
   411.2  1141.2   425.6 1143.08     510 1146.94   552.4 1163.55   564.5 1165.47
   569.5 1167.64   583.3 1176.35   595.4 1179.47     634 1193.58   671.3 1209.22
#Mann= 4 ,-1,0
       0      .1       0  295.14    .045       0   347.7     .06       0
  443.49      .1       0
Bank Sta=295.14,347.7
XS Rating Curve= 0 ,0
Exp/Cntr=0.3,0.1

Type RM Length L Ch R = 1 ,13879   ,441.6,428,405.6
XS GIS Cut Line= 3
2148187.38379292646459.3349675822147950.05879292646790.521967583
2147715.79207663647040.952462785
#Sta/Elev= 30
       0 1291.65      22 1280.61    56.4 1261.24    71.2 1254.02    83.9 1246.36
    94.8 1237.98   105.6 1234.01   159.7 1198.65   194.2 1181.77   211.5 1168.95
   218.4 1162.79     233 1144.81   238.7 1135.61   243.4 1129.71   248.3 1127.31
  257.251125.645   287.4 1123.19   297.5 1123.39  311.991125.646   346.7 1128.66
   361.5 1133.82   376.3 1136.85   403.8 1136.67   416.3 1140.73   461.6 1145.08
   527.3 1149.59   563.5 1154.69   656.9 1170.29   723.3 1185.62   750.4 1194.39
#Mann= 5 ,-1,0
       0      .1       0  257.25    .045       0  311.99      .1       0
     320     .06       0  437.44      .1       0
Bank Sta=257.25,311.99
XS Rating Curve= 0 ,0
Exp/Cntr=0.3,0.1

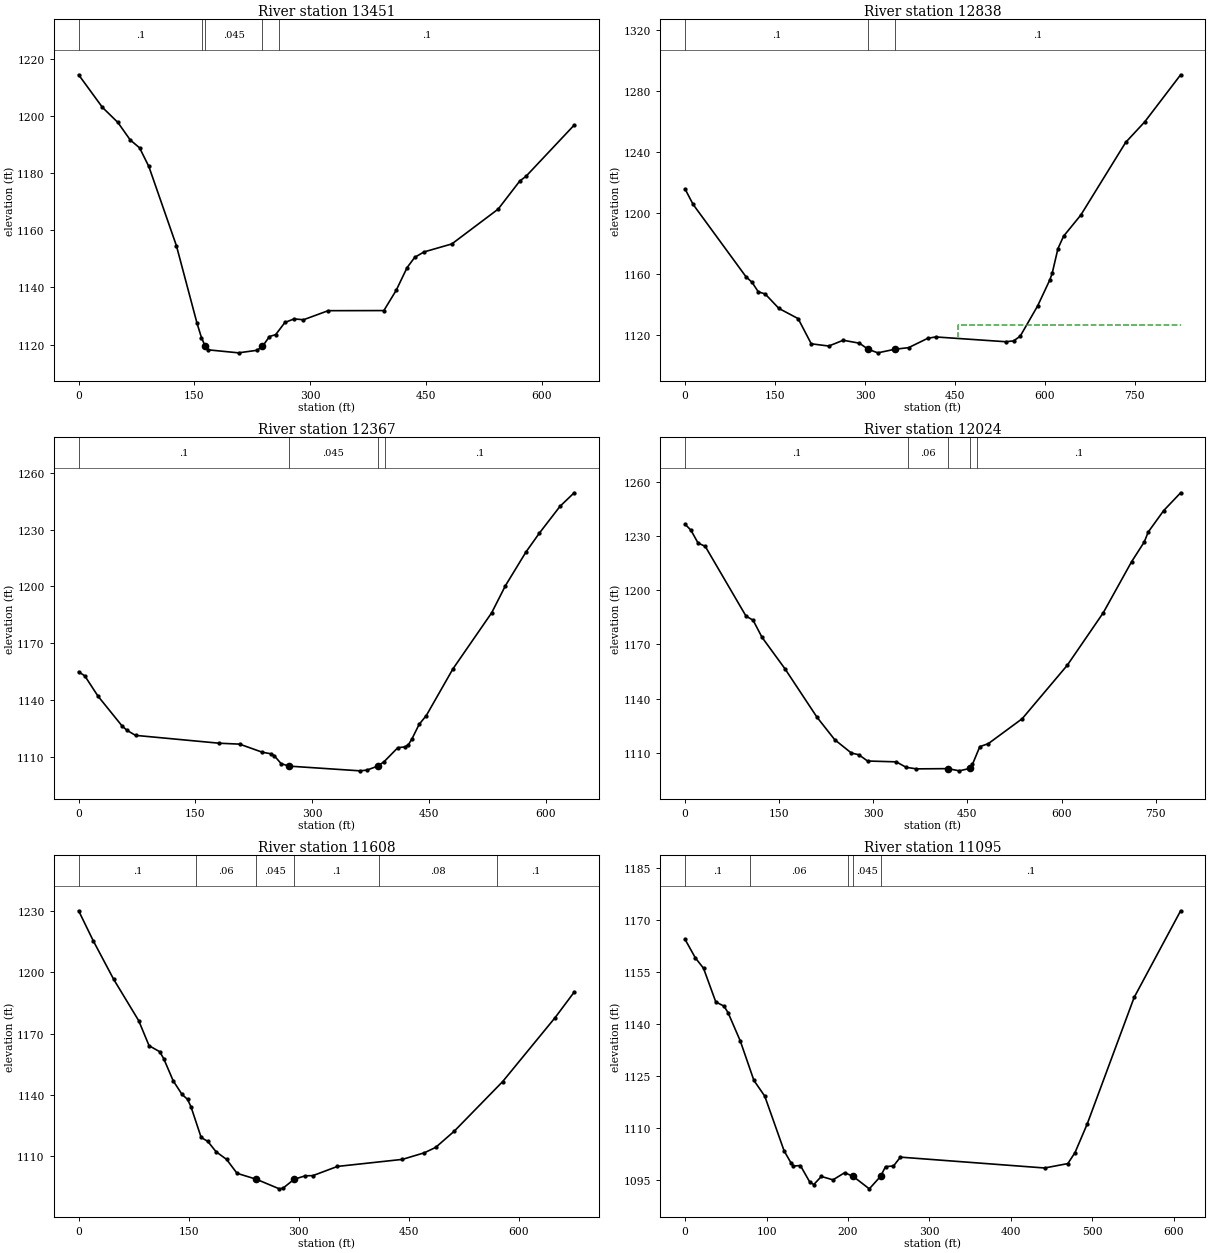
Type RM Length L Ch R = 1 ,13451   ,578.6,612.7,612.2
XS GIS Cut Line= 3
2147633.95590936646358.4077560932147617.43449162646700.019406836
     2147620.665      646999.623
#Sta/Elev= 30
       0 1214.45    30.8 1203.04    50.8 1197.76    66.8 1191.63    78.9 1188.87
    90.9 1182.34   126.6  1154.6   153.3 1127.44     159 1122.45  163.981119.338
     167 1118.16     207 1117.09     231 1117.98  237.981119.337   247.1 1122.81
   255.1 1123.46   267.1 1127.73   279.1 1128.98   291.1 1128.67   323.1 1131.85
   395.2 1131.89   411.2    1139   425.3 1146.95   435.2 1150.54   447.2 1152.42
   483.2 1155.22   543.2 1167.42   571.2 1177.26   579.2 1178.89   641.6 1196.83
#Mann= 5 ,-1,0
       0      .1       0     160     .06       0  163.98    .045       0
  237.98     .06       0     260      .1       0
Bank Sta=163.98,237.98
XS Rating Curve= 0 ,0
Exp/Cntr=0.3,0.1

Type RM Length L Ch R = 1 ,12838   ,467,471.7,472.3
XS GIS Cut Line= 3
  2147308.495986646209.786923366  2147053.976986646529.176923366
  2146817.540986646873.879923366
#Sta/Elev= 30
       0 1215.46    13.4 1205.38   101.5    1158   111.7 1154.31     122 1148.14
   133.6 1146.67   156.4 1137.22   188.5 1130.53   210.4 1114.01   239.6 1112.55
   263.7 1116.34   290.8  1114.4  305.211110.438   321.4 1108.09  349.841110.439
   372.8  1111.5   404.9 1117.67   418.1 1118.51   534.5 1115.38   547.8 1115.91
   558.8 1118.98   587.9 1138.84   608.2 1155.88   612.1 1160.11   621.8 1176.43
   631.2 1184.58     660 1198.46   734.8 1246.11   766.5 1259.52   826.4 1290.39
#Mann= 3 ,-1,0
       0      .1       0  305.21    .045       0  349.84      .1       0
#XS Ineff= 2 , 0
                          455.79         1126.63
Permanent Ineff=
       F       F
Bank Sta=305.21,349.84
XS Rating Curve= 0 ,0
Exp/Cntr=0.3,0.1

Type RM Length L Ch R = 1 ,12367   ,307,342.5,345.4
XS GIS Cut Line= 4
2146848.43500661646098.2690722252146707.67063452646259.153448073
2146620.83272511646445.1542372922146511.97856004646633.716943984
#Sta/Elev= 30
       0 1154.91     7.9 1152.77    24.9 1142.05    56.1 1126.18    62.3 1123.98
    73.1 1121.35   180.8  1117.2   206.9 1116.72     236 1112.45   246.9 1111.64
   251.3 1110.65   260.2 1106.43   270.51105.106   361.7 1102.62   370.5 1103.02
  384.281105.104   392.5 1107.44   410.2 1114.86   419.1 1115.24   423.7 1116.35
   428.3 1119.46   437.5 1127.12   446.8 1131.83     481 1156.46   530.8 1186.09
   548.4 1200.34   574.7 1218.07   592.1 1228.15   618.7 1242.33   636.8 1249.44
#Mann= 4 ,-1,0
       0      .1       0   270.5    .045       0  384.28     .06       0
  393.77      .1       0
Bank Sta=270.5,384.28
XS Rating Curve= 0 ,0
Exp/Cntr=0.3,0.1

Type RM Length L Ch R = 1 ,12024   ,409.5,416.5,405.3
XS GIS Cut Line= 4
     2146754.993      645898.6642146566.63550085646085.248741897
2146375.02423985646192.0107842232146183.85994199646430.235387759
#Sta/Elev= 30
       0 1236.61     9.3 1233.28    20.7 1226.17    32.1 1224.36    97.1 1185.69
   108.4 1183.41   122.6 1173.95   159.3 1156.45   210.2 1129.68   238.5  1117.2
     265 1109.82   277.1 1108.83   290.8 1105.39   336.6 1104.92   352.2 1101.92
   368.7 1101.03   419.1 1101.16   437.1 1099.94  453.931101.304     458 1103.49
   469.8 1113.37   483.2 1114.98   537.3 1128.82   609.1 1158.41   666.6 1187.57
   711.6 1215.76   731.9 1226.78   738.3 1232.33   762.9 1244.18   789.9 1254.04
#Mann= 5 ,-1,0
       0      .1       0  355.13     .06       0   419.1    .045       0
  453.93     .06       0  465.13      .1       0
Bank Sta=419.1,453.93
XS Rating Curve= 0 ,0
Exp/Cntr(USF)=0,0
Exp/Cntr=0.3,0.1

Type RM Length L Ch R = 1 ,11608   ,496.3,512.7,499
XS GIS Cut Line= 2
2146415.90888356645673.9527140822145883.26859025646089.162918956
#Sta/Elev= 30
       0 1230.24    19.9 1215.55    47.7  1196.7    81.9 1176.37      96 1164.13
   110.4  1161.2   115.9 1157.83   128.9 1146.92   140.9 1140.26   148.4 1137.86
   153.2 1134.14     167 1119.17     176 1117.25   187.3 1112.18   201.6 1108.43
   215.9  1101.6  242.241098.687   273.5 1093.99   278.6 1094.31  293.691098.686
     309 1100.38   319.2 1100.45   352.7 1104.97   441.2 1108.42   471.3 1111.67
   486.6  1114.3   511.9 1122.22   577.8 1146.49   649.4 1177.88   675.4 1190.38
#Mann= 6 ,-1,0
       0      .1       0     160     .06       0  242.24    .045       0
  293.69      .1       0     410     .08       0     570      .1       0
Bank Sta=242.24,293.69
XS Rating Curve= 0 ,0
Exp/Cntr=0.3,0.1

Type RM Length L Ch R = 1 ,11095   ,461.4,465.2,454.7
XS GIS Cut Line= 2
2146062.24828812645356.8935630182145576.62217389645723.577949169
#Sta/Elev= 30
       0 1164.38    12.6 1159.07    22.6 1156.09    37.7 1146.36    47.7 1145.17
    52.7 1143.31    67.8  1135.1    84.5 1123.74    97.8 1119.22   121.6 1103.43
   130.2  1099.9   133.1 1099.07   141.6  1099.2     153 1094.48     158 1093.72
   167.3 1096.06   181.6 1095.08   195.9 1097.14   206.3 1096.09   226.2 1092.49
   240.1 1096.11   246.1  1098.9   255.9 1099.08   264.4 1101.63   441.5  1098.5
     470 1099.77   478.8 1102.94   493.8  1111.2   551.4 1147.67   608.5 1172.65
#Mann= 5 ,-1,0
       0      .1       0      80     .06       0     200      .1       0
   206.3    .045       0   240.1      .1       0
Bank Sta=206.3,240.1
XS Rating Curve= 0 ,0
Exp/Cntr=0.3,0.1