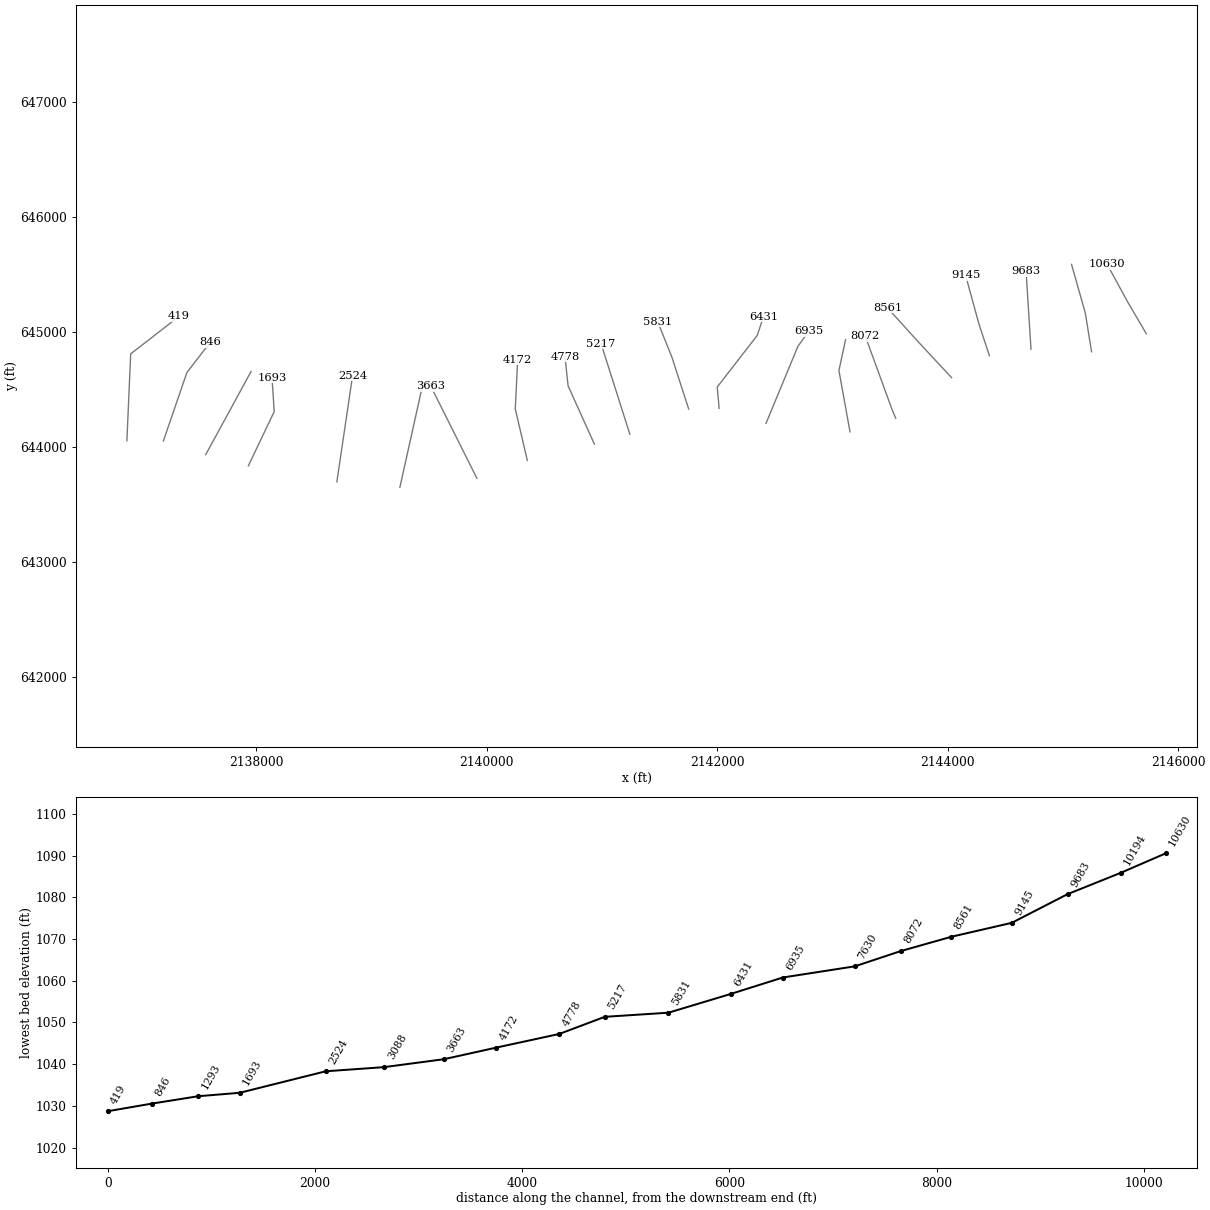
HEC-RAS study LIKANARV.prj: LIKANARV

--- LIKANARV.g01 (geometry) --- (continued)

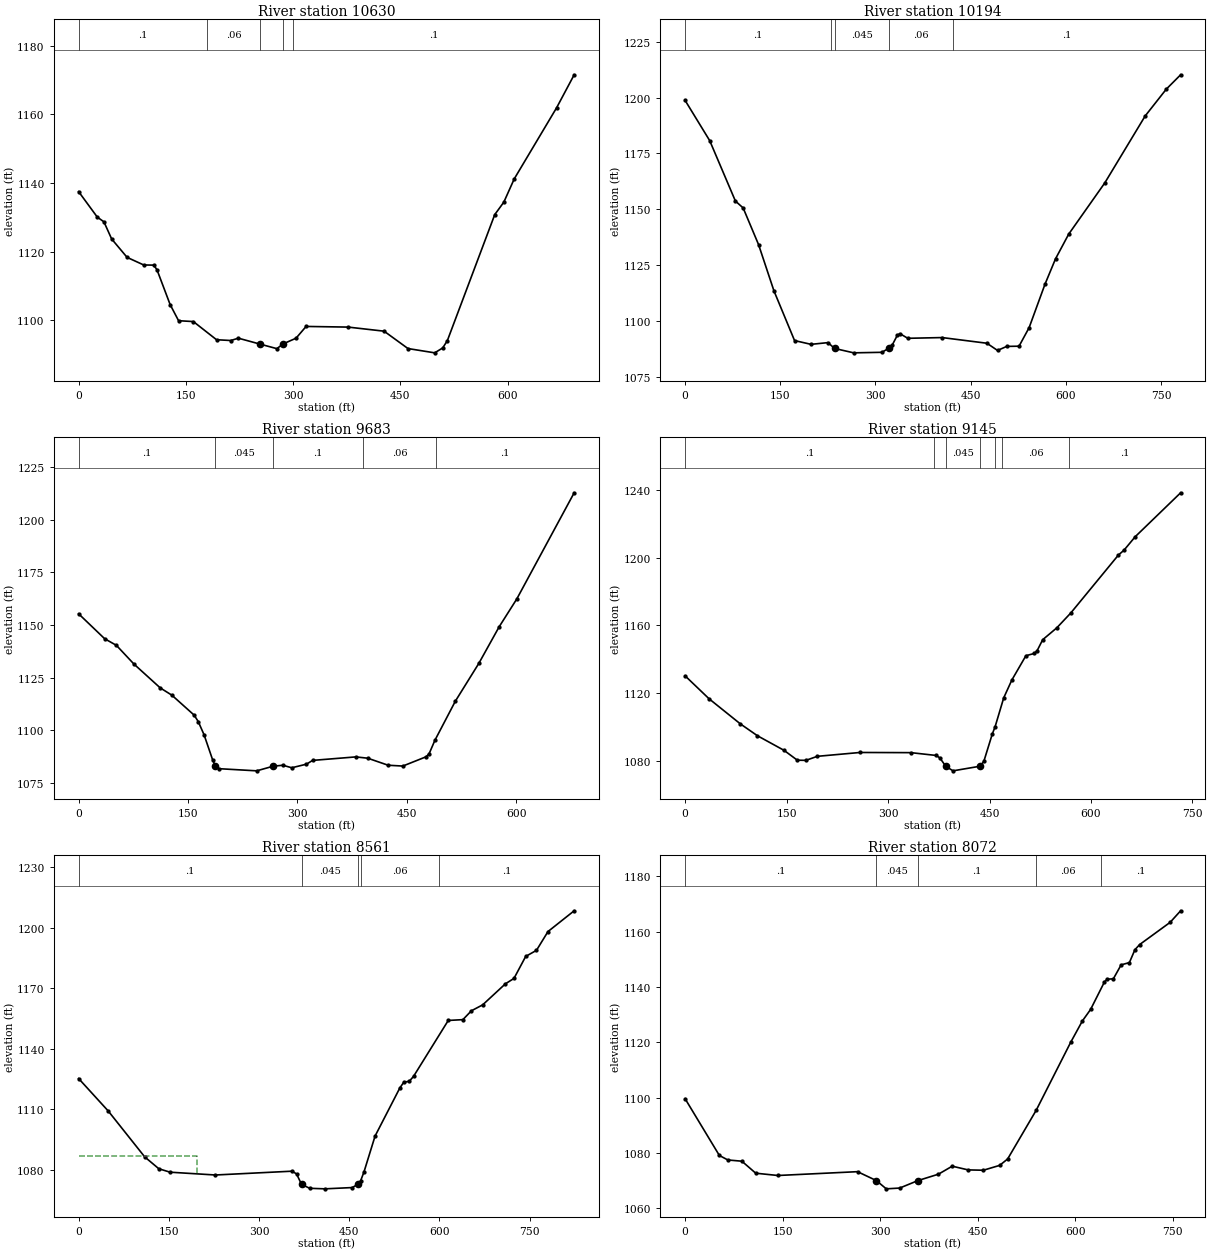
Type RM Length L Ch R = 1 ,10630   ,430.6,435.1,415.2
XS GIS Cut Line= 3
2145724.89653942644982.6404443722145562.17783714645261.083760503
2145385.16379292645586.799776712
#Sta/Elev= 30
       0 1137.49    26.1 1130.07    35.4 1128.69    46.2  1123.7    67.8 1118.34
      91 1116.13   104.9 1116.08   109.5 1114.79     128 1104.59   139.8 1099.89
   160.5 1099.64   192.9 1094.35   212.9 1094.12   223.4  1094.8   253.1 1093.11
   277.3 1091.75     286 1093.13   304.1 1094.79   318.2 1098.22     377 1098.03
   427.3 1096.84   460.7 1091.78   498.1 1090.53   509.3 1091.96   515.8 1094.09
   582.1  1130.8   594.8 1134.43   609.4 1141.22   668.6 1161.91   693.2 1171.53
#Mann= 5 ,-1,0
       0      .1       0     180     .06       0   253.1    .045       0
     286     .06       0     300      .1       0
Bank Sta=253.1,286
XS Rating Curve= 0 ,0
Exp/Cntr=0.3,0.1

Type RM Length L Ch R = 1 ,10194   ,505,511,493.2
XS GIS Cut Line= 3
2145249.46719528644826.8473397292145194.89906043645164.719386151
2145075.67039056645586.911818723
#Sta/Elev= 30
       0 1198.74    38.8 1180.73    79.3 1153.72    91.5 1150.64   115.8 1134.24
   140.1 1113.51   172.5 1091.34   198.5 1089.65   225.2 1090.42  235.61 1087.81
   265.7 1085.85   310.3 1086.09  320.621087.874   326.5 1089.36   334.6 1093.75
   338.7 1094.41     351 1092.35   405.1 1092.68   475.7 1090.14   492.4 1086.92
   506.9 1088.73   526.3 1088.82   542.2 1097.11   567.2 1116.53   583.8 1127.89
   604.6 1138.94   661.4 1161.81   725.1 1191.77   758.4 1203.77     781 1210.19
#Mann= 5 ,-1,0
       0      .1       0     230     .05       0  235.61    .045       0
  320.62     .06       0  422.25      .1       0
Bank Sta=235.61,320.62
XS Rating Curve= 0 ,0
Exp/Cntr=0.3,0.1

Type RM Length L Ch R = 1 ,9683    ,526.9,538.4,510.8
XS GIS Cut Line= 2
2144723.77766148644849.5038435922144680.93955684645527.797608505
#Sta/Elev= 30
       0 1155.35    35.7 1143.51    51.8 1140.37    75.8  1131.5   111.9 1120.16
   127.9 1116.69   158.4 1107.23     164 1104.19     172 1097.91     184 1085.75
  187.661082.995   192.1 1081.79   244.2 1080.76     267 1082.98   280.2 1083.41
   292.3 1082.22   312.4 1083.92   320.9 1085.72   380.1 1087.38   396.5 1086.76
   424.5 1083.42   444.6 1083.03   476.6 1087.45   480.6 1088.83   488.6 1095.27
   516.7 1113.88   548.8 1131.78   576.8 1149.23   600.9  1162.4   679.6 1212.84
#Mann= 5 ,-1,0
       0      .1       0  187.66    .045       0     267      .1       0
     390     .06       0     490      .1       0
Bank Sta=187.66,267
XS Rating Curve= 0 ,0
Exp/Cntr=0.3,0.1

Type RM Length L Ch R = 1 ,9145    ,564.9,584.6,594.8
XS GIS Cut Line= 3
2144363.13047109644791.5635227012144270.03198722645074.412888558
2144155.94583459645493.939645441
#Sta/Elev= 30
       0 1130.12    35.4 1116.55    81.7 1101.67     107 1094.64   146.2 1086.03
   165.9 1080.18   178.6 1080.09   195.4 1082.47   258.6 1084.75   333.8 1084.65
   371.1 1082.99   376.5 1081.57  385.221076.638     396 1073.88  436.39 1076.64
   441.7 1079.64     454 1095.58   458.2 1099.92     471 1117.11     483 1127.65
   503.8 1142.05   516.2 1143.36   520.3 1144.96   528.6 1151.51   549.4 1158.52
   570.1 1167.32   640.5 1201.62   648.8 1204.52   665.4  1212.5   732.5 1238.49
#Mann= 7 ,-1,0
       0      .1       0  367.78     .06       0  385.22    .045       0
  436.39     .06       0  457.78      .1       0  467.78     .06       0
  567.78      .1       0
Bank Sta=385.22,436.39
XS Rating Curve= 0 ,0
Exp/Cntr=0.3,0.1

Type RM Length L Ch R = 1 ,8561    ,490.4,488.2,467.8
XS GIS Cut Line= 3
     2144035.029      644601.119     2143756.056      644901.115
     2143478.092      645208.575
#Sta/Elev= 30
       0 1125.19    49.2 1109.12   109.9 1086.36   133.4 1080.48   152.1 1078.78
   227.4 1077.39   355.1 1079.28   362.5 1077.89  370.641072.774   384.2  1070.8
   409.6 1070.53   454.9 1071.16   464.41072.778   469.1 1074.61   474.5 1078.87
     493  1096.7   534.2 1120.54   540.7 1123.34   549.9 1123.84   556.9 1126.23
   614.7 1153.98     639 1154.38   653.2 1158.77   671.9  1161.7   709.8 1172.15
     724 1174.81   743.5 1185.72   761.4 1188.72   780.6 1198.05   824.1 1208.33
#Mann= 5 ,-1,0
       0      .1       0  370.64    .045       0   464.4      .1       0
  469.66     .06       0  599.66      .1       0
#XS Ineff= 2 , 0
          196.76  1086.8
Permanent Ineff=
       F       F
Bank Sta=370.64,464.4
XS Rating Curve= 0 ,0
Exp/Cntr=0.3,0.1

Type RM Length L Ch R = 1 ,8072    ,430.9,441.9,423.1
XS GIS Cut Line= 3
2143549.90197404644248.7523957542143518.88392258644321.259946918
2143285.56278757644963.252302911
#Sta/Elev= 30
       0 1099.65    52.7 1079.15    65.7 1077.53    87.3 1077.08   108.6 1072.75
   142.6 1071.92   265.1  1073.3  294.061070.085   309.3  1067.1   329.9 1067.38
  358.021070.086   389.5 1072.39   410.7 1075.28   435.2 1073.94   458.6 1073.82
   483.6 1075.57   495.9 1077.88   539.8 1095.47   592.8    1120   610.8 1127.73
   623.5 1131.91   644.8 1141.85   649.1 1142.84   658.4 1142.94   670.4 1147.99
   683.1 1148.82   691.6 1153.47     699 1155.35   745.8 1163.36   761.9 1167.53
#Mann= 5 ,-1,0
       0      .1       0  294.06    .045       0  358.02      .1       0
  538.86     .06       0  638.86      .1       0
Bank Sta=294.06,358.02
XS Rating Curve= 0 ,0
Exp/Cntr=0.3,0.1

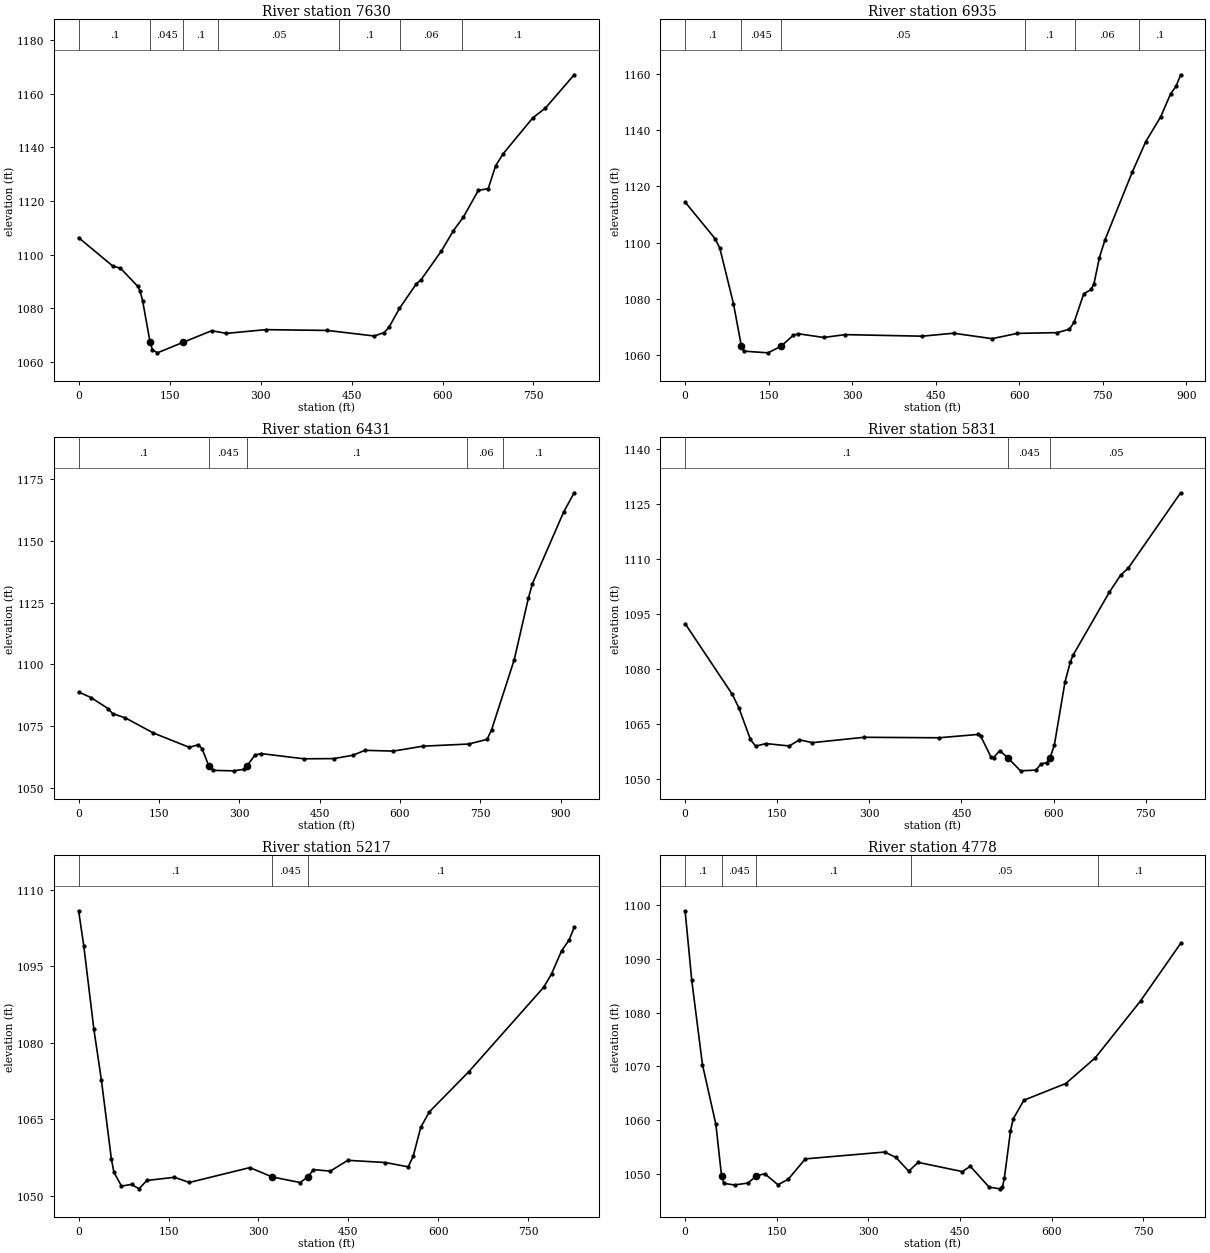
Type RM Length L Ch R = 1 ,7630    ,698.7,695.2,657.7
XS GIS Cut Line= 3
2143153.21757435644129.382450033 2143057.0126963644662.983538936
2143114.77920928644931.787298971
#Sta/Elev= 30
       0 1106.34    56.7  1095.7    68.9 1094.99    97.3 1088.27   101.4 1086.38
   105.5 1082.86  117.831067.378   121.7  1064.6   129.9 1063.45  172.411067.381
   219.3 1071.69   243.7  1070.7   308.7 1072.09   410.3 1071.79   487.5 1069.72
   503.8    1071   511.9 1073.03     529 1079.99   556.7 1089.11   564.9 1090.76
   598.3 1101.44   618.1    1109   634.5 1114.02     659 1123.94   675.4 1124.63
   687.6 1133.11   699.9 1137.56     749 1151.01   769.5 1154.56   817.1 1167.01
#Mann= 7 ,-1,0
       0      .1       0  117.83    .045       0  172.41      .1       0
     230     .05       0     430      .1       0     530     .06       0
   632.2      .1       0
Bank Sta=117.83,172.41
XS Rating Curve= 0 ,0
Exp/Cntr=0.3,0.1

Type RM Length L Ch R = 1 ,6935    ,507.6,504.7,488.2
XS GIS Cut Line= 3
2142424.35205822644203.628663252 2142701.2615114 644873.96553736
2142797.04281589645007.757268286
#Sta/Elev= 30
       0 1114.44    53.6 1101.47    62.3 1098.07    86.8 1078.31  101.171063.088
   105.5 1061.37   148.8 1060.77  172.051063.083     194 1066.96   203.2 1067.56
   249.1 1066.24   287.3 1067.25   425.8  1066.7   482.1 1067.75   551.3 1065.82
   596.7  1067.7   668.2 1067.96   690.2  1069.2   698.5 1071.64   715.8 1081.79
   729.2 1083.32   734.2 1085.41     744 1094.71   753.8 1100.91     803 1125.15
   827.1 1135.93     854 1144.81   871.9 1153.03   881.5 1155.62   889.8 1159.76
#Mann= 6 ,-1,0
       0      .1       0  101.17    .045       0  172.05     .05       0
     610      .1       0     700     .06       0  815.28      .1       0
Bank Sta=101.17,172.05
XS Rating Curve= 0 ,0
Exp/Cntr=0.3,0.1

Type RM Length L Ch R = 1 ,6431    ,562.9,599.3,632.8
XS GIS Cut Line= 4
2142017.44426986644334.1716955132142000.88046077644519.465580273
2142347.70742014644968.0763272922142402.34754445645131.248450821
#Sta/Elev= 30
       0 1088.75    23.1 1086.51    55.2 1082.01    63.3 1080.01    87.4 1078.25
   139.6 1072.14   206.7 1066.33   223.8 1067.42   230.7 1065.69  243.221058.684
   250.3    1057   289.3 1056.81   309.4 1057.45  313.781058.684   329.3  1063.2
   340.7  1063.8   420.8 1061.69   476.4 1061.77   511.8 1063.12   534.6 1065.12
   587.6 1064.81   642.7  1066.8   728.5 1067.68   762.7 1069.58   771.1 1073.51
   813.3 1101.85   839.6  1126.7     847  1132.5   905.7 1161.75   925.2 1169.49
#Mann= 5 ,-1,0
       0      .1       0  243.22    .045       0  313.78      .1       0
  726.03     .06       0  793.08      .1       0
Bank Sta=243.22,313.78
XS Rating Curve= 0 ,0
Exp/Cntr=0.3,0.1

Type RM Length L Ch R = 1 ,5831    ,617.3,614.2,619.2
XS GIS Cut Line= 3
 2141753.2147561      644327.8812141607.07512116 644780.77266798
 2141484.3406963645088.052032261
#Sta/Elev= 30
       0 1092.41      77 1073.11    87.7 1069.39   106.4 1060.86   114.8 1059.05
   131.7 1059.75   169.5  1059.1   186.2 1060.77   207.3    1060   291.4 1061.46
   413.3 1061.33   476.3 1062.23   481.5 1061.68   497.9 1056.15   502.2 1055.93
   512.3 1057.83  525.09 1055.94   546.1 1052.33   571.1 1052.53   579.7 1054.22
   589.2 1054.59  594.331055.947   601.2 1059.37   618.5 1076.49   627.1 1081.93
   631.4 1083.74   690.8 1100.98   709.3 1105.63   721.6 1107.52   806.8 1128.01
#Mann= 3 ,-1,0
       0      .1       0  525.09    .045       0  594.33     .05       0
Bank Sta=525.09,594.33
XS Rating Curve= 0 ,0
Exp/Cntr=0.3,0.1

Type RM Length L Ch R = 1 ,5217    ,418.3,439.4,426.8
XS GIS Cut Line= 2
2141242.51944798644109.0004485612140992.78522784644897.208535034
#Sta/Elev= 30
       0 1105.84     8.6 1098.95    25.4 1082.64      38 1072.64    54.7 1057.12
    58.9 1054.59    71.5 1051.88    88.3 1052.21   100.9 1051.34   113.7 1052.98
   159.6  1053.6   184.8 1052.59   285.6  1055.5   323.3 1053.66   369.4 1052.58
  382.331053.637   391.8 1055.11   419.8 1054.81   449.2 1056.93   511.8  1056.5
   549.9 1055.65   558.3 1057.77   570.8 1063.39   585.1 1066.42   650.6 1074.25
   775.9 1090.84     789 1093.46   805.8 1097.99   818.4 1100.12   826.8 1102.57
#Mann= 3 ,-1,0
       0      .1       0   323.3    .045       0  382.33      .1       0
Bank Sta=323.3,382.33
XS Rating Curve= 0 ,0
Exp/Cntr=0.3,0.1

Type RM Length L Ch R = 1 ,4778    ,605.1,605.9,593.4
XS GIS Cut Line= 3
2140934.59300487644023.2331371212140706.51430792644530.318154854
2140679.48319406644784.311471128
#Sta/Elev= 30
       0 1098.92    10.9 1085.99    28.4 1070.34    50.4 1059.21   59.611049.708
    63.5 1048.24    81.1 1047.95     103 1048.31 116.6191049.636   130.4 1050.03
   152.2 1047.99   168.8 1049.01   196.9  1052.8   326.7 1054.07   345.2 1053.07
   366.2 1050.51   381.5 1052.15   453.9 1050.44     467 1051.42   497.8 1047.55
   515.3 1047.23   519.7 1047.63   522.7 1049.16   532.8 1057.98   537.2 1060.23
   554.8 1063.71   623.3 1066.81   671.5 1071.57   745.7 1082.16   811.4 1092.85
#Mann= 5 ,-1,0
       0      .1       0   59.61    .045       0 116.619      .1       0
     370     .05       0  676.02      .1       0
Bank Sta=59.61,116.619
XS Rating Curve= 0 ,0
Exp/Cntr=0.3,0.1

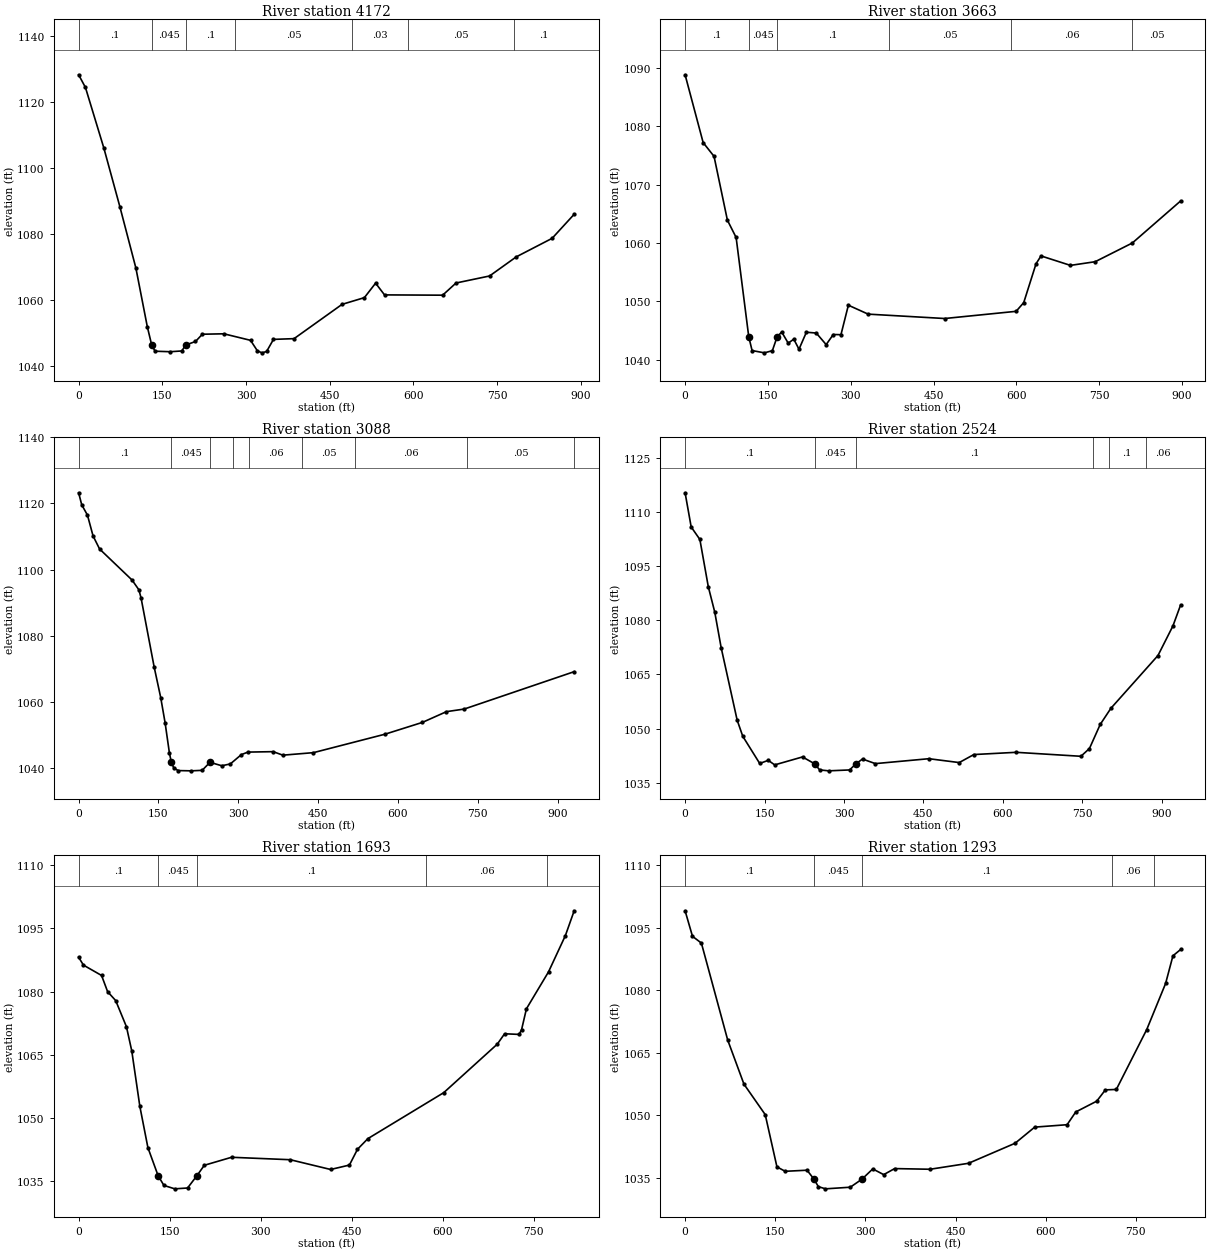
Type RM Length L Ch R = 1 ,4172    ,500.8,508.8,514.3
XS GIS Cut Line= 3
2140352.86237902 643881.272912082140248.24879732644328.871865043
2140268.97818992644756.615713194
#Sta/Elev= 30
       0 1128.23    12.2 1124.39    45.1 1106.08    73.8 1088.31   102.6 1069.66
   123.1 1051.85  130.951046.321     137 1044.46   164.2 1044.31   184.8 1044.54
   191.9 1046.34   209.4 1047.41   221.7 1049.61   260.2 1049.74     308 1047.76
   320.3 1044.58   328.5 1043.97   336.8 1044.38   349.1 1048.05     386 1048.27
     472 1058.66     512  1060.7   532.1 1065.08   548.1 1061.53   652.2 1061.44
   676.2 1065.13   736.3 1067.26   784.1 1073.05   848.4 1078.67   887.9 1085.96
#Mann= 7 ,-1,0
       0      .1       0  130.95    .045       0   191.9      .1       0
     280     .05       0  489.66     .03       0  589.66     .05       0
  779.66      .1       0
Bank Sta=130.95,191.9
XS Rating Curve= 0 ,0
Exp/Cntr=0.3,0.1

Type RM Length L Ch R = 1 ,3663    ,595.8,574.7,557.2
XS GIS Cut Line= 2
2139915.56053986643724.6534204932139514.87570112644527.406382475
#Sta/Elev= 30
       0  1088.8    32.7 1077.18    52.4 1074.83    76.6 1063.89    92.4 1060.93
  115.271043.909   121.3 1041.56   143.6 1041.17     158 1041.54  166.591043.904
   174.9 1044.74   186.7 1042.83   196.8 1043.51   206.2 1041.79   219.6  1044.7
   237.5 1044.56   255.4 1042.58   268.3 1044.31   282.2 1044.28   295.6 1049.33
   331.4  1047.8     470 1047.05   599.3 1048.28   613.1 1049.77   635.4 1056.43
   644.4 1057.77   697.7 1056.15   742.5 1056.78   809.8 1059.99   897.2 1067.19
#Mann= 6 ,-1,0
       0      .1       0  115.27    .045       0  166.59      .1       0
     370     .05       0     590     .06       0     810     .05       0
Bank Sta=115.27,166.59
XS Rating Curve= 0 ,0
Exp/Cntr=0.3,0.1

Type RM Length L Ch R = 1 ,3088    ,562,564.3,567.6
XS GIS Cut Line= 2
 2139246.9190142 643646.673007442139448.31718143644555.391346636
#Sta/Elev= 30
       0 1123.23     5.8 1119.61    16.6 1116.47    27.1  1110.2    39.4 1106.25
   100.4 1096.88   113.2 1093.93   117.3 1091.45   141.9 1070.61   154.2 1061.39
   162.4  1053.8   170.5 1044.69   174.2 1041.82   178.7 1040.17   186.9 1039.36
   211.5 1039.28     232 1039.43  246.671041.844   268.9 1040.82   284.9 1041.36
   305.7 1044.18     318 1044.94   365.4 1045.07   383.6 1044.01     441 1044.77
   575.4 1050.34   645.8 1053.91   690.9 1057.15   724.2 1057.93   930.8 1069.22
#Mann= 9 ,-1,0
       0      .1       0   174.2    .045       0  246.67      .1       0
     290     .05       0     320     .06       0     420     .05       0
     520     .06       0     730     .05       0     930     .06       0
Bank Sta=174.2,246.67
XS Rating Curve= 0 ,0
Exp/Cntr=0.3,0.1

Type RM Length L Ch R = 1 ,2524    ,827,831.2,801
XS GIS Cut Line= 2
2138699.89038851643693.8193029932138836.53707868644619.481210752
#Sta/Elev= 30
       0 1115.29    11.5 1105.82    27.9 1102.36    43.8 1089.28      56 1082.24
    68.1 1072.39    98.3 1052.32   108.9 1047.85   140.9 1040.32     157 1041.19
   169.2 1039.93   221.7 1042.13   244.61040.231   254.1 1038.54     271 1038.28
   310.7 1038.53  322.481040.219     335 1041.55   359.2 1040.28   460.3 1041.64
   517.6 1040.57   545.2 1042.79   625.1 1043.41   747.4 1042.31   763.5 1044.46
   783.8 1051.12     804  1055.6   892.9 1070.22   921.2 1078.43   935.7 1084.24
#Mann= 6 ,-1,0
       0      .1       0   244.6    .045       0  322.48      .1       0
     770     .06       0     800      .1       0     870     .06       0
Bank Sta=244.6,322.48
XS Rating Curve= 0 ,0
Exp/Cntr=0.3,0.1

Type RM Length L Ch R = 1 ,1693    ,390,399.5,383.6
XS GIS Cut Line= 3
2137931.96535422643834.0204247712138156.37657968644306.193116436
2138137.13704144644599.650693149
#Sta/Elev= 30
       0 1088.16     7.9 1086.29    37.8 1083.83    47.8 1079.97    61.1 1077.86
    78.8 1071.65    87.6  1065.9   100.9 1052.73   114.2 1042.91  131.021036.243
   140.6 1033.93   158.5 1033.12   179.6 1033.32  194.991036.242   207.2 1038.72
   252.1 1040.62   348.9 1040.04   415.4 1037.72   446.4 1038.77   459.7 1042.52
   476.8 1045.05   601.9 1055.98   690.1  1067.5   702.2 1069.97   726.2 1069.82
   730.2 1070.95   738.2 1075.91   774.6 1084.68   802.4  1093.3   816.9  1099.2
#Mann= 5 ,-1,0
       0      .1       0  131.02    .045       0  194.99      .1       0
  572.79     .06       0  772.79      .1       0
Bank Sta=131.02,194.99
XS Rating Curve= 0 ,0
Exp/Cntr=0.3,0.1

Type RM Length L Ch R = 1 ,1293    ,430.6,447.8,450.1
XS GIS Cut Line= 2
2137561.70531556643930.9156777842137955.51640977644655.130891724
#Sta/Elev= 30
       0 1099.03    12.3  1092.9    27.1 1091.28    70.9    1068    97.9 1057.43
   133.3 1050.11   152.8 1037.57   166.5 1036.51   202.9 1036.77214.27391034.646
   221.7 1032.83   233.5  1032.3   274.8 1032.69   294.31034.626   312.2 1037.08
   330.4 1035.71   348.6 1037.16   407.6    1037   471.5 1038.43     549 1043.24
   581.6 1047.11   635.5 1047.69   649.9 1050.75   684.8 1053.34   699.2 1056.05
   717.4 1056.15     768 1070.53   799.4 1081.59   811.6 1088.23   824.4 1089.74
#Mann= 5 ,-1,0
       0      .1       0214.2739    .045       0   294.3      .1       0
     710     .06       0     780      .1       0
Bank Sta=214.2739,294.3
XS Rating Curve= 0 ,0
Exp/Cntr=0.3,0.1

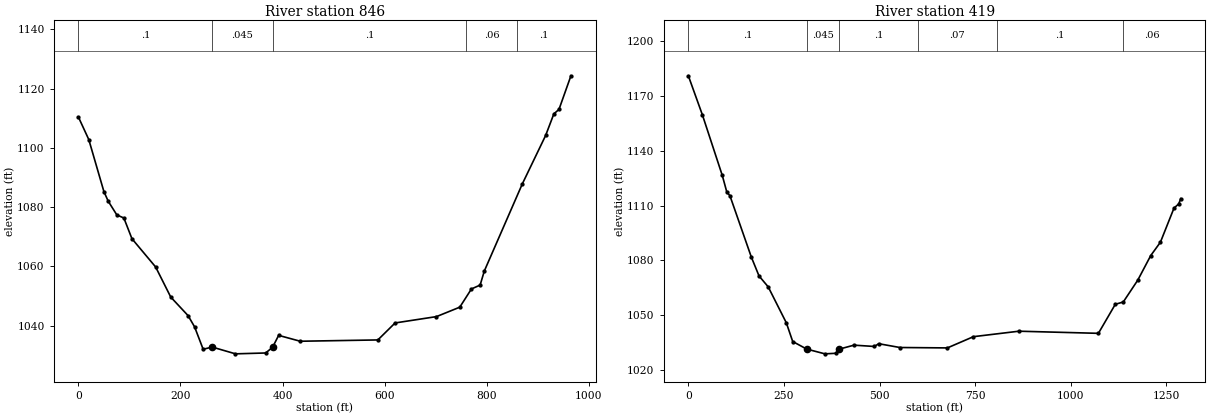
Type RM Length L Ch R = 1 ,846     ,394.2,426.5,430
XS GIS Cut Line= 3
2137194.21909351644050.0387994452137398.71696919644646.053975583
2137603.21484488644911.726429462
#Sta/Elev= 30
       0 1110.36    20.2 1102.82    49.8 1085.29    58.3 1082.02    75.2 1077.39
      89 1076.35   104.8 1069.37   151.3 1059.82   180.9 1049.68   214.8 1043.43
   227.6 1039.64   244.4 1032.08   262.2 1032.81   307.8 1030.53     367 1030.82
  380.541032.752   392.4 1036.76   434.7 1034.78   586.9 1035.22   620.7 1040.95
   701.8 1043.09   747.5 1046.27   770.3 1052.41   787.4 1053.73   795.6 1058.47
   870.1 1087.86   915.8 1104.19   931.9 1111.47     942    1113   965.4 1124.33
#Mann= 5 ,-1,0
       0      .1       0   262.2    .045       0  380.54      .1       0
  760.12     .06       0  860.12      .1       0
Bank Sta=262.2,380.54
XS Rating Curve= 0 ,0
Exp/Cntr(USF)=0,0
Exp/Cntr=0.3,0.1

Type RM Length L Ch R = 1 ,419     ,408.2,410.9,411.9
XS GIS Cut Line= 3
2136877.72033366644052.5394219972136910.73518539644807.996911464
 2137330.2180073645134.261328509
#Sta/Elev= 30
       0 1181.13    36.7 1159.74    88.7 1126.54   100.7 1117.32   108.7  1115.4
   164.8  1081.7   184.8 1071.41   208.8 1065.42   256.2 1045.71   272.9 1035.46
  309.491031.311     357  1028.7     385 1028.99  395.05 1031.31   433.1 1033.46
   486.3 1032.74   497.8 1034.25   553.2 1032.17   677.3 1031.95   745.4 1038.11
   864.4 1041.11  1072.2 1039.94  1116.4 1055.87  1137.2 1057.12  1175.1 1069.09
    1209 1082.57  1234.3 1089.89  1269.8 1108.58  1282.1 1110.89  1287.6 1113.77
#Mann= 6 ,-1,0
       0      .1       0  309.49    .045       0  395.05      .1       0
     600     .07       0  806.18      .1       0 1136.18     .06       0
Bank Sta=309.49,395.05
XS Rating Curve= 0 ,0
Exp/Cntr(USF)=0,0
Exp/Cntr=0.3,0.1