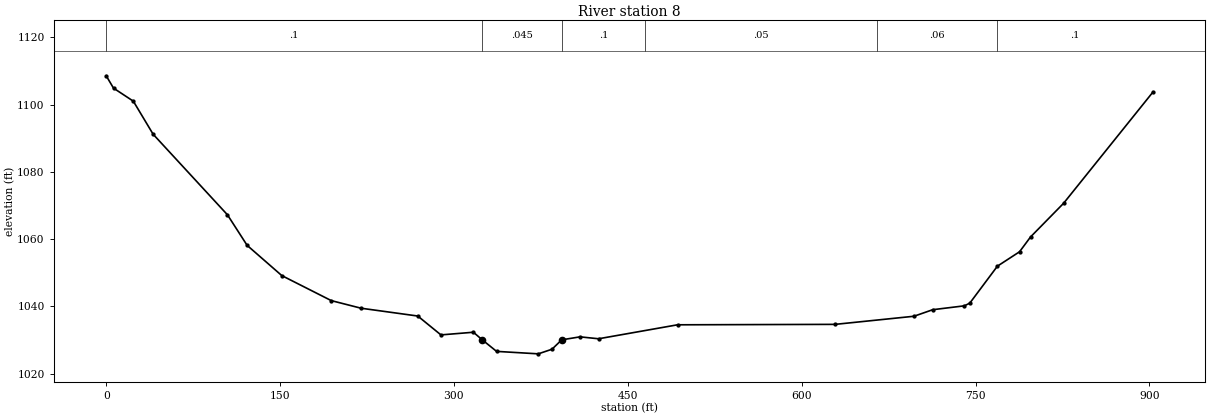
HEC-RAS study LIKANARV.prj: LIKANARV

--- LIKANARV.g01 (geometry) --- (continued)

Type RM Length L Ch R = 1 ,8       ,,,
XS GIS Cut Line= 4
2136572.67009649644099.2511189242136490.27658303644319.511583582
2136484.35301545 644802.874698712136384.24241867644958.018333922
#Sta/Elev= 30
       0 1108.57     6.3  1104.9    23.4 1101.02    40.5 1091.19   104.6 1067.25
   121.6 1058.16   151.5 1049.18   194.2 1041.74   219.9 1039.48   268.8 1037.16
   288.8 1031.55   316.8 1032.34  324.271030.138   336.8 1026.65   372.8 1025.92
   384.6 1027.29     393 1030.08   408.8 1030.97   424.8  1030.4   492.9 1034.55
   628.9 1034.68   696.9 1037.09   713.1 1039.04   740.4 1040.19   745.1    1041
   768.9 1051.98     788 1056.26   797.5 1060.67     826 1070.67   903.2 1103.78
#Mann= 6 ,-1,0
       0      .1       0  324.27    .045       0     393      .1       0
  465.17     .05       0  665.17     .06       0  768.57      .1       0
Bank Sta=324.27,393
XS Rating Curve= 0 ,0
Exp/Cntr(USF)=0,0
Exp/Cntr=0.3,0.1
LCMann Table=0

Chan Stop Cuts=-1
Use User Specified Reach Order=0
Composite Channel Slope=5